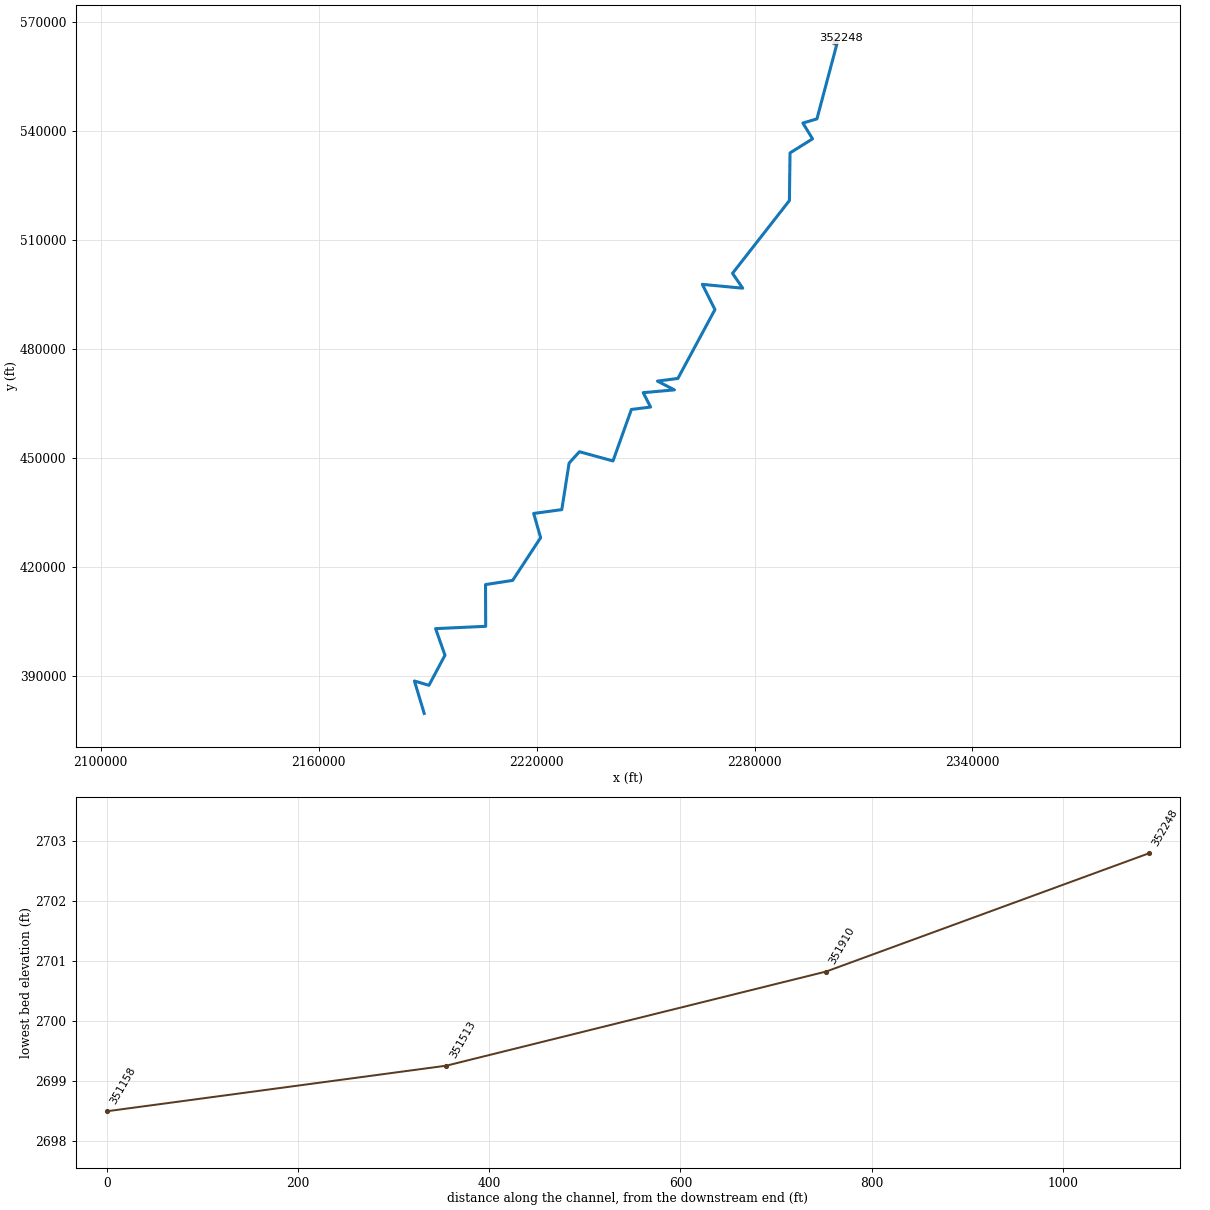
--- GRNBRRRV.prj (project) ---

Proj Title=GRNBRRRV
Current Plan=p01
Default Exp/Contr=0,0
English Units
Geom File=g01
Flow File=f01
Plan File=p01
Background Map Layer=FWY
Background Map Layer=StudyTypeAE
Background Map Layer=Inundation Boundary (01pct Value_0)
Y Axis Title=Elevation
X Axis Title(PF)=Main Channel Distance
X Axis Title(XS)=Station
BEGIN DESCRIPTION:
----------MODEL BY WOOD PLC 2021----------
Stream Name: Greenbrier River
Flood Zone: Alternating Approximate / Detailed
Pocahontas County, WV
HEC-RAS Version: RAS 6.0
Vertical Datum: NAVD88
Projection: NAD 1983 StatePlane West Virginia S FIPS 4702 (US Feet)
Terrain: 1-meter LIDAR (FEMA Region III 3DEP collected 2016-2018)
Land Use: 2019 NLCD
Hydrologic Method:
Gage-Weighted WV 2010 RRE
Model Notes:
Alternating A/AE Reach:
Zone A - 0-60017
Zone AE -  60258-123473
Zone A -123984-259092
Zone AE - 259313-266483
Zone A -   266654-350091
Zone AE- 350636- 352248
KWSEL tie in to county boundary with Greenbrier County
END DESCRIPTION:
DSS File=dss
DSS Export Rating Curves= 0
DSS Export Rating Curve Sorted= 0
DSS Export Volume Flow Curves= 0
DXF OffsetX= 0
DXF OffsetY= 0
DXF ScaleX= 0
DXF ScaleY= 0

--- GRNBRRRV.p01 (plan) ---

Plan Title=Floodplain
Program Version=6.10
Short Identifier=Floodplain
Geom File=g01
Flow File=f01
Subcritical Flow
K Sum by GR= 0
Std Step Tol= 0.01
Critical Tol= 0.01
Num of Std Step Trials= 20
Max Error Tol= 0.3
Flow Tol Ratio= 0.001
Split Flow NTrial= 30
Split Flow Tol= 0.02
Split Flow Ratio= 0.02
Log Output Level= 0
Friction Slope Method= 1
Unsteady Friction Slope Method= 2
Unsteady Bridges Friction Slope Method= 1
Parabolic Critical Depth
Global Vel Dist= 0 , 0 , 0
Global Log Level= 0
CheckData=True
Encroach Param=-1 ,0,0, 2
Encroach River=GRNBRRRV
Encroach Reach=Main
Encroach Node=352248
       1  379.21  597.55
Encroach Node=351910
       1   454.7  742.47
Encroach Node=351513
       1  410.84  651.37
Encroach Node=351158
       1   307.5     475
Encroach Node=350636
       1   431.1  648.45
Encroach Node=350091
       1   379.1   752.2
Encroach Node=349827
       1  401.58  716.41
Encroach Node=349586
       1  400.95  677.27
Encroach Node=349081
       1  266.08     510
Encroach Node=348584
       1  312.35     507
Encroach Node=348085
       1   205.4  505.95
Encroach Node=347589
       1  446.58   688.5
Encroach Node=347296
       1  315.47  557.12
Encroach Node=347005
       1     380   547.5
Encroach Node=346583
       1     372     684
Encroach Node=346069
       1   385.9  1038.8
Encroach Node=345541
       1  292.88 1038.86
Encroach Node=345218
       1   350.3 1102.65
Encroach Node=344584
       1     382  1008.8
Encroach Node=344079
       1  350.57  797.23
Encroach Node=343589
       1   415.2  666.07
Encroach Node=343051
       1   383.3     552
Encroach Node=342590
       1     480     707
Encroach Node=342091
       1   532.7     660
Encroach Node=341581
       1  333.35     542
Encroach Node=341041
       1     306  557.63
Encroach Node=340584
       1   411.8  543.65
Encroach Node=340086
       1     376  611.57
Encroach Node=339593
       1   365.9     540
Encroach Node=339241
       1  360.06  526.38
Encroach Node=339054
       1     372   508.1
Encroach Node=338588
       1   228.1     382
Encroach Node=338135
       1  283.78  653.64
Encroach Node=337608
       1  294.21     804
Encroach Node=337332
       1  205.95     715
Encroach Node=337019
       1     720 1143.39
Encroach Node=336937
       1  672.72  1173.3
Encroach Node=336587
       1  895.96 1465.61
Encroach Node=335959
       1   265.7   856.8
Encroach Node=335372
       1   306.9  611.86
Encroach Node=335002
       1     260  606.73
Encroach Node=334588
       1  375.05  703.52
Encroach Node=334091
       1  382.57     739
Encroach Node=333583
       1     446     740
Encroach Node=333085
       1   242.1   488.9
Encroach Node=332585
       1   256.1   510.7
Encroach Node=332085
       1  220.83     510
Encroach Node=331585
       1  430.08  729.01
Encroach Node=331087
       1  304.03   623.9
Encroach Node=330582
       1     388  582.49
Encroach Node=330085
       1   392.3     537
Encroach Node=329630
       1  310.57   489.2
Encroach Node=329334
       1   323.1     604
Encroach Node=329070
       1   406.3   764.7
Encroach Node=328584
       1     430     844
Encroach Node=328269
       1     499     900
Encroach Node=327953
       1  613.95     896
Encroach Node=327589
       1  324.41     657
Encroach Node=327087
       1  265.26     539
Encroach Node=326587
       1  295.11     534
Encroach Node=326087
       1   233.9     529
Encroach Node=325589
       1  276.72     653
Encroach Node=325090
       1     370     651
Encroach Node=324581
       1  285.89     664
Encroach Node=323915
       1  401.29  945.47
Encroach Node=323579
       1     529 1285.25
Encroach Node=323081
       1   411.6  1251.1
Encroach Node=322584
       1   395.5 1167.26
Encroach Node=322322
       1     447  1211.9
Encroach Node=321482
       1     283  675.18
Encroach Node=320970
       1   308.9  653.51
Encroach Node=320167
       1   179.8  647.43
Encroach Node=319485
       1      72  466.85
Encroach Node=319197
       1      96     500
Encroach Node=318841
       1     100   318.6
Encroach Node=318485
       1     258  475.05
Encroach Node=318222
       1  364.83  533.19
Encroach Node=317798
       1   421.5     773
Encroach Node=317253
       1  494.35     870
Encroach Node=316684
       1  585.35   858.7
Encroach Node=316136
       1     538  804.94
Encroach Node=315578
       1     488  1024.4
Encroach Node=315089
       1   381.8  980.42
Encroach Node=314593
       1   379.4 1093.37
Encroach Node=314078
       1   376.9 1170.68
Encroach Node=313588
       1     371 1123.12
Encroach Node=313070
       1   377.6 1076.21
Encroach Node=312598
       1   374.3  925.51
Encroach Node=311991
       1  561.75 1345.81
Encroach Node=310921
       1   363.5 1408.29
Encroach Node=310434
       1   689.2  1426.6
Encroach Node=309755
       1  372.58 1154.52
Encroach Node=309248
       1  523.13 1374.21
Encroach Node=308784
       1  373.05  1093.1
Encroach Node=308367
       1   351.7  938.05
Encroach Node=308091
       1   352.3   918.8
Encroach Node=307602
       1   374.4   820.9
Encroach Node=307111
       1   392.6   774.4
Encroach Node=306622
       1   394.4   716.5
Encroach Node=306082
       1  231.68   547.2
Encroach Node=305587
       1  250.65   516.6
Encroach Node=305085
       1  302.85     523
Encroach Node=304587
       1  269.99   520.3
Encroach Node=304087
       1   363.8     533
Encroach Node=303580
       1  696.64  872.74
Encroach Node=302732
       1   338.5   583.5
Encroach Node=302512
       1     301  454.57
Encroach Node=302146
       1  374.13  560.83
Encroach Node=301328
       1   704.4   905.6
Encroach Node=301030
       1  412.38     854
Encroach Node=300667
       1   260.8     706
Encroach Node=300426
       1  254.33     705
Encroach Node=300023
       1  384.38     742
Encroach Node=299497
       1     310     710
Encroach Node=298991
       1  451.74  875.08
Encroach Node=298585
       1  496.17  958.58
Encroach Node=298251
       1  624.26  1023.2
Encroach Node=297893
       1  547.44    1041
Encroach Node=297601
       1   429.4    1146
Encroach Node=297108
       1  655.59 1359.08
Encroach Node=296696
       1   383.1  994.25
Encroach Node=296191
       1   410.3  819.52
Encroach Node=295588
       1     282  474.43
Encroach Node=295084
       1   206.2  361.73
Encroach Node=294618
       1  319.56     608
Encroach Node=294280
       1  389.35     669
Encroach Node=294050
       1     385     666
Encroach Node=293605
       1  468.24     625
Encroach Node=293089
       1  479.98   648.4
Encroach Node=292584
       1  481.86   630.9
Encroach Node=292082
       1   391.3   587.9
Encroach Node=291584
       1  370.76  827.93
Encroach Node=291087
       1     343 1092.78
Encroach Node=290587
       1   395.1  1341.7
Encroach Node=290086
       1     352  1362.2
Encroach Node=289591
       1     362 1168.37
Encroach Node=289088
       1   630.5 1462.94
Encroach Node=288593
       1     435 1368.65
Encroach Node=288094
       1  225.96 1040.52
Encroach Node=287679
       1  205.65  984.55
Encroach Node=287055
       1   368.4   878.3
Encroach Node=286601
       1   281.4  615.33
Encroach Node=286423
       1     246  463.21
Encroach Node=286198
       1  291.39  539.99
Encroach Node=285824
       1  403.88  724.95
Encroach Node=285442
       1   355.7   655.4
Encroach Node=285064
       1  260.02  514.57
Encroach Node=284783
       1     320     536
Encroach Node=284414
       1  308.79     590
Encroach Node=284098
       1  390.28   599.2
Encroach Node=283589
       1  383.84   684.9
Encroach Node=283137
       1     693   920.3
Encroach Node=282592
       1  571.58  918.98
Encroach Node=282177
       1  558.33 1130.95
Encroach Node=281611
       1   275.3 1226.78
Encroach Node=281114
       1     493  1188.5
Encroach Node=280892
       1   508.6 1546.55
Encroach Node=280137
       1  395.13 1581.26
Encroach Node=279526
       1  340.97  1549.3
Encroach Node=278881
       1   226.6   915.8
Encroach Node=278368
       1  215.73  688.06
Encroach Node=278074
       1     200  563.39
Encroach Node=277527
       1     297  579.16
Encroach Node=277017
       1  313.85   668.2
Encroach Node=276577
       1   226.4  572.99
Encroach Node=276087
       1  291.63     515
Encroach Node=275587
       1  362.26  510.64
Encroach Node=275087
       1   377.5   513.4
Encroach Node=274587
       1     383     529
Encroach Node=274082
       1     308     535
Encroach Node=273590
       1     262     474
Encroach Node=273087
       1   456.2  674.79
Encroach Node=272591
       1   320.3   505.9
Encroach Node=272086
       1  274.76  485.93
Encroach Node=271587
       1   406.4   547.9
Encroach Node=271087
       1   375.6   522.9
Encroach Node=270587
       1   384.9     520
Encroach Node=270084
       1  348.75     515
Encroach Node=269586
       1  367.95   531.9
Encroach Node=269085
       1     338     506
Encroach Node=268550
       1   404.2  584.13
Encroach Node=268087
       1     370     517
Encroach Node=267587
       1   239.8   505.8
Encroach Node=267087
       1   93.38     525
Encroach Node=266654
       1  281.54  687.32
Encroach Node=266483
       1     287     653
Encroach Node=266165
       1     225     428
Encroach Node=265960
       1   253.5  434.91
Encroach Node=265732
       1     164     421
Encroach Node=265513
       1  242.62  463.81
Encroach Node=265345
       1     218     426
Encroach Node=265172
       1   256.8   489.4
Encroach Node=264889
       1   225.2   495.9
Encroach Node=264586
       1     261     532
Encroach Node=264389
       1  467.09    1000
Encroach Node=264296
       1  383.58     939
Encroach Node=263784
       1  260.46     685
Encroach Node=263311
       1     539    1110
Encroach Node=262777
       1     580    1231
Encroach Node=262202
       1     550  1286.9
Encroach Node=261842
       1     565    1278
Encroach Node=261409
       1  348.04   995.1
Encroach Node=261094
       1  309.93  936.65
Encroach Node=260568
       1     651 1115.99
Encroach Node=260129
       1     371     705
Encroach Node=259925
       1   467.5  863.68
Encroach Node=259586
       1  364.73     910
Encroach Node=259313
       1   305.9    1000
Encroach Node=259092
       1   263.7     970
Encroach Node=258582
       1     352     850
Encroach Node=258044
       1     265     860
Encroach Node=257184
       1     240   825.5
Encroach Node=256589
       1  176.43  515.55
Encroach Node=256143
       1     386     680
Encroach Node=255599
       1     368     650
Encroach Node=255087
       1     385     590
Encroach Node=254587
       1     375  624.39
Encroach Node=254087
       1   387.5  594.58
Encroach Node=253588
       1   382.4  570.25
Encroach Node=253087
       1   373.8  601.71
Encroach Node=252587
       1  364.28   572.7
Encroach Node=252088
       1   363.7   566.5
Encroach Node=251768
       1     300     644
Encroach Node=251373
       1     384     726
Encroach Node=251085
       1  486.05  714.91
Encroach Node=250627
       1  542.85     797
Encroach Node=250086
       1  533.79   695.7
Encroach Node=249587
       1   429.9  632.78
Encroach Node=249085
       1   362.1     630
Encroach Node=248597
       1   383.6  627.58
Encroach Node=248086
       1  345.24  611.92
Encroach Node=247588
       1   348.1  627.73
Encroach Node=247087
       1   270.5   557.7
Encroach Node=246587
       1   276.1  539.99
Encroach Node=246087
       1  316.65     580
Encroach Node=245587
       1     357   761.6
Encroach Node=245107
       1     400  855.05
Encroach Node=244621
       1     338    1010
Encroach Node=244047
       1     273  847.13
Encroach Node=243769
       1     314     720
Encroach Node=243533
       1  376.29  685.52
Encroach Node=243428
       1  417.26   706.4
Encroach Node=243087
       1   233.3  640.05
Encroach Node=242602
       1  378.27   802.4
Encroach Node=242090
       1   374.5  746.39
Encroach Node=241587
       1     350  625.74
Encroach Node=241087
       1     328     593
Encroach Node=240586
       1     341   563.4
Encroach Node=240089
       1     340  588.01
Encroach Node=239587
       1     374  640.58
Encroach Node=239087
       1     350   675.8
Encroach Node=238588
       1     194  554.05
Encroach Node=238170
       1     129   437.8
Encroach Node=237619
       1   376.4   615.3
Encroach Node=237341
       1     360     656
Encroach Node=237085
       1     361  605.81
Encroach Node=236587
       1  333.65   540.4
Encroach Node=236087
       1     360     560
Encroach Node=235587
       1  273.77  550.16
Encroach Node=235091
       1     188     549
Encroach Node=234587
       1   233.7   533.6
Encroach Node=234108
       1     378   683.7
Encroach Node=233587
       1     329  638.15
Encroach Node=233087
       1     344  667.95
Encroach Node=232587
       1   339.1  636.25
Encroach Node=232089
       1     363  608.89
Encroach Node=231588
       1   372.5  555.23
Encroach Node=231089
       1     121  339.35
Encroach Node=230589
       1  130.01  460.05
Encroach Node=230094
       1   255.4   779.6
Encroach Node=229589
       1   122.5  465.45
Encroach Node=229366
       1      82  435.64
Encroach Node=228975
       1     198  548.05
Encroach Node=228578
       1     190     610
Encroach Node=228086
       1  300.08  527.01
Encroach Node=227587
       1  258.75  539.95
Encroach Node=227087
       1  267.51  542.81
Encroach Node=226588
       1  354.85  626.46
Encroach Node=226080
       1   363.8   708.3
Encroach Node=225570
       1     391   827.4
Encroach Node=225086
       1   372.8   752.2
Encroach Node=224587
       1   372.3   741.5
Encroach Node=224087
       1     365   711.2
Encroach Node=223584
       1   382.3   797.4
Encroach Node=223085
       1   382.5   768.6
Encroach Node=222586
       1     372     783
Encroach Node=222255
       1  434.84   817.6
Encroach Node=221719
       1   351.6   620.7
Encroach Node=221363
       1     252     548
Encroach Node=220947
       1   302.4  594.43
Encroach Node=220589
       1   400.8   620.3
Encroach Node=220081
       1  379.18   659.7
Encroach Node=219587
       1     370  600.01
Encroach Node=219087
       1     372   636.3
Encroach Node=218574
       1     189  466.03
Encroach Node=218089
       1     184   397.1
Encroach Node=217589
       1     162  380.03
Encroach Node=217084
       1  151.46  528.71
Encroach Node=216442
       1  114.51     624
Encroach Node=216176
       1  125.93  575.45
Encroach Node=215812
       1  390.45   741.6
Encroach Node=215425
       1  330.15  682.29
Encroach Node=215088
       1  254.98  604.83
Encroach Node=214553
       1   459.6  690.03
Encroach Node=214086
       1  299.23  574.09
Encroach Node=213693
       1  302.11  597.89
Encroach Node=213446
       1     240  597.59
Encroach Node=213270
       1   344.4  703.62
Encroach Node=213213
       1  364.56  740.11
Encroach Node=213003
       1     379     806
Encroach Node=212702
       1  390.25     876
Encroach Node=212224
       1  323.75     736
Encroach Node=211709
       1   400.5  686.91
Encroach Node=211174
       1  337.55  621.78
Encroach Node=210595
       1  380.43     753
Encroach Node=210091
       1   313.3     737
Encroach Node=209595
       1  425.73     748
Encroach Node=209061
       1     295  701.55
Encroach Node=208615
       1     352  739.98
Encroach Node=208200
       1     267  533.82
Encroach Node=207866
       1     293  528.61
Encroach Node=207517
       1     478     668
Encroach Node=207116
       1     205  429.18
Encroach Node=206807
       1  200.17  452.18
Encroach Node=206591
       1  209.38  437.05
Encroach Node=206093
       1   203.3  444.34
Encroach Node=205592
       1  210.62   455.5
Encroach Node=205096
       1     185  420.68
Encroach Node=204594
       1     255     570
Encroach Node=203952
       1  267.34   598.2
Encroach Node=203550
       1  264.03  640.75
Encroach Node=203093
       1     195  561.25
Encroach Node=202594
       1  273.73     619
Encroach Node=202094
       1  233.05     545
Encroach Node=201597
       1  378.33  668.46
Encroach Node=201110
       1  400.15     685
Encroach Node=200577
       1   380.7  636.03
Encroach Node=200014
       1  384.78  652.98
Encroach Node=199547
       1  406.92  674.18
Encroach Node=199053
       1     365  721.85
Encroach Node=198537
       1  149.25  438.38
Encroach Node=198147
       1     180   368.3
Encroach Node=197700
       1     180  421.25
Encroach Node=197358
       1  140.08  370.35
Encroach Node=197098
       1     115  374.08
Encroach Node=196585
       1  166.06  409.78
Encroach Node=196087
       1  341.25   557.2
Encroach Node=195594
       1   275.9  523.81
Encroach Node=195094
       1  314.04  532.05
Encroach Node=194594
       1  320.11   568.8
Encroach Node=194094
       1  353.23  650.55
Encroach Node=193600
       1   351.8   644.5
Encroach Node=193089
       1     370  610.06
Encroach Node=192595
       1     151  453.95
Encroach Node=192092
       1  122.38   400.4
Encroach Node=191593
       1   395.3     660
Encroach Node=191092
       1  394.49     789
Encroach Node=190588
       1   340.9     917
Encroach Node=190097
       1     487  1052.7
Encroach Node=189590
       1  225.12  637.74
Encroach Node=189087
       1   362.1   874.5
Encroach Node=188577
       1     350  857.43
Encroach Node=188098
       1     210   597.2
Encroach Node=187594
       1     212   455.9
Encroach Node=187091
       1     370  626.65
Encroach Node=186607
       1  302.81  693.95
Encroach Node=186094
       1  305.57  803.79
Encroach Node=185594
       1  203.35   686.4
Encroach Node=185091
       1  131.96  559.46
Encroach Node=184596
       1  133.42  647.62
Encroach Node=184094
       1  187.55  528.58
Encroach Node=183594
       1  227.87  680.73
Encroach Node=183133
       1     324     784
Encroach Node=182744
       1     210     841
Encroach Node=182460
       1     400     893
Encroach Node=182094
       1  493.72     749
Encroach Node=181582
       1     310     799
Encroach Node=180997
       1   463.6  962.36
Encroach Node=180494
       1   451.5     922
Encroach Node=179998
       1  392.38  760.63
Encroach Node=179546
       1   499.1     764
Encroach Node=179094
       1     377     644
Encroach Node=178593
       1     318   588.2
Encroach Node=178098
       1   312.7  869.03
Encroach Node=177591
       1  362.29 1001.51
Encroach Node=177117
       1   354.8 1085.88
Encroach Node=176588
       1   387.7 1065.16
Encroach Node=176100
       1   382.3  948.86
Encroach Node=175631
       1   390.2   886.5
Encroach Node=175095
       1     368   789.9
Encroach Node=174600
       1   365.7  762.63
Encroach Node=174092
       1     369   675.7
Encroach Node=173598
       1  346.87  606.22
Encroach Node=173096
       1   373.4  642.66
Encroach Node=172600
       1     240     480
Encroach Node=172227
       1  321.77  532.93
Encroach Node=172092
       1     628  852.57
Encroach Node=171971
       1  619.86     828
Encroach Node=171353
       1  194.81  500.98
Encroach Node=170965
       1  185.95  599.03
Encroach Node=170590
       1     142   748.6
Encroach Node=170098
       1     163  844.75
Encroach Node=169740
       1   243.6  898.48
Encroach Node=169113
       1  217.95  960.88
Encroach Node=168596
       1  172.36  973.15
Encroach Node=168113
       1  230.29  1015.3
Encroach Node=167627
       1  223.96    1118
Encroach Node=167099
       1  231.34    1046
Encroach Node=166604
       1  313.21     943
Encroach Node=166092
       1  174.83     730
Encroach Node=165596
       1  191.83   732.5
Encroach Node=165109
       1   373.6     760
Encroach Node=164613
       1  479.63   789.3
Encroach Node=164110
       1  434.85  833.97
Encroach Node=163598
       1  353.05  723.39
Encroach Node=163091
       1  497.23  735.29
Encroach Node=162593
       1  319.79  623.63
Encroach Node=162096
       1  304.85  923.88
Encroach Node=161590
       1   358.5 1022.33
Encroach Node=161093
       1   371.5     912
Encroach Node=160603
       1   370.4  895.91
Encroach Node=160132
       1   403.5  828.24
Encroach Node=159618
       1     396  745.17
Encroach Node=159112
       1  404.08   732.7
Encroach Node=158571
       1  344.46  663.35
Encroach Node=158108
       1  404.22  723.34
Encroach Node=157593
       1  348.25   648.1
Encroach Node=157091
       1     370  588.58
Encroach Node=156596
       1  241.29     493
Encroach Node=156091
       1  383.96     707
Encroach Node=155608
       1  380.16  952.48
Encroach Node=155095
       1  387.35   983.7
Encroach Node=154591
       1  507.79  1038.7
Encroach Node=154091
       1  431.57   927.1
Encroach Node=153595
       1  359.18   982.6
Encroach Node=153098
       1   375.5  1086.1
Encroach Node=152590
       1  284.96  1147.8
Encroach Node=152092
       1   301.1  1084.7
Encroach Node=151615
       1  230.93 1069.57
Encroach Node=151093
       1  260.59   941.9
Encroach Node=150595
       1  272.69   949.9
Encroach Node=150095
       1  281.78     892
Encroach Node=149595
       1  170.01  777.74
Encroach Node=149095
       1  230.02  770.12
Encroach Node=148594
       1  106.12  859.45
Encroach Node=148093
       1  246.03 1065.55
Encroach Node=147637
       1  291.94     999
Encroach Node=147094
       1  706.29    1198
Encroach Node=146589
       1 1101.65    1542
Encroach Node=146094
       1     313  717.63
Encroach Node=145678
       1  411.55  900.58
Encroach Node=145394
       1     293     780
Encroach Node=145112
       1   208.8   715.6
Encroach Node=144623
       1     263  640.55
Encroach Node=144103
       1  350.12  714.48
Encroach Node=143722
       1   350.7  788.48
Encroach Node=143252
       1  323.11  864.83
Encroach Node=142936
       1  359.83 1005.14
Encroach Node=142587
       1   459.1  1196.8
Encroach Node=142075
       1  530.12  1176.4
Encroach Node=141591
       1  391.59    1212
Encroach Node=141102
       1  275.12 1173.76
Encroach Node=140403
       1  459.53  1213.4
Encroach Node=140091
       1   228.8     933
Encroach Node=139598
       1  242.34   798.7
Encroach Node=139087
       1   254.1     677
Encroach Node=138604
       1  522.59   813.8
Encroach Node=138228
       1  649.15   899.2
Encroach Node=137910
       1  579.26   792.2
Encroach Node=137594
       1  360.03   574.1
Encroach Node=137088
       1  343.37     686
Encroach Node=136599
       1   379.1     738
Encroach Node=136094
       1  359.68   698.5
Encroach Node=135594
       1   350.9   629.6
Encroach Node=135094
       1  330.73  647.23
Encroach Node=134594
       1  344.42  648.85
Encroach Node=134094
       1  335.24   637.5
Encroach Node=133596
       1   337.6  723.85
Encroach Node=133093
       1   340.5   863.5
Encroach Node=132593
       1   367.3   992.9
Encroach Node=132123
       1   323.5  779.42
Encroach Node=131546
       1   318.3  969.63
Encroach Node=131036
       1   460.6 1122.37
Encroach Node=130595
       1   346.8   902.4
Encroach Node=130102
       1     352 1164.35
Encroach Node=129603
       1   357.6 1292.74
Encroach Node=129094
       1     353 1341.23
Encroach Node=128591
       1     353 1358.48
Encroach Node=128089
       1     285 1228.09
Encroach Node=127751
       1     223  1038.8
Encroach Node=127082
       1  312.37 1016.31
Encroach Node=126595
       1   303.3  849.13
Encroach Node=126088
       1  260.58  1186.6
Encroach Node=125606
       1  295.78 1234.65
Encroach Node=125266
       1  316.71  1245.3
Encroach Node=124861
       1   297.3 1125.03
Encroach Node=124481
       1   208.3 1044.57
Encroach Node=123984
       1   356.2  1055.8
Encroach Node=123473
       1   185.6  901.39
Encroach Node=123097
       1   308.5 1167.55
Encroach Node=122517
       1     773    1650
Encroach Node=121988
       1     840 1709.87
Encroach Node=121517
       1     950    1709
Encroach Node=121029
       1     675  1602.4
Encroach Node=120562
       1  518.97  1665.3
Encroach Node=120183
       1     463    1637
Encroach Node=119793
       1  565.57    1940
Encroach Node=119686
       1  672.72    1946
Encroach Node=119244
       1     830    2347
Encroach Node=118514
       1  1300.2    2910
Encroach Node=118156
       1     791    1910
Encroach Node=117647
       1     750    1772
Encroach Node=116875
       1  398.93  1323.4
Encroach Node=116458
       1     339  1136.5
Encroach Node=116080
       1     362    1173
Encroach Node=115592
       1     380  1235.9
Encroach Node=115096
       1  542.88  1386.5
Encroach Node=114689
       1   791.1  1608.3
Encroach Node=114093
       1     850 1611.99
Encroach Node=113694
       1   955.5  1676.5
Encroach Node=113090
       1  775.79  1472.5
Encroach Node=112546
       1  653.88  1358.8
Encroach Node=112095
       1     622    1249
Encroach Node=111497
       1     760 1171.58
Encroach Node=111095
       1  784.43  1254.3
Encroach Node=110595
       1  508.68  1000.1
Encroach Node=110095
       1  526.88     988
Encroach Node=109594
       1  236.88  555.79
Encroach Node=109094
       1  245.36   569.7
Encroach Node=108560
       1  264.89  701.66
Encroach Node=108094
       1  260.35   649.1
Encroach Node=107621
       1   307.5  736.73
Encroach Node=107094
       1  235.06   658.7
Encroach Node=106594
       1   370.9     755
Encroach Node=106142
       1     210     540
Encroach Node=105595
       1     320     580
Encroach Node=105069
       1     201     483
Encroach Node=104604
       1     360     805
Encroach Node=104140
       1     356  918.31
Encroach Node=103596
       1   362.1     935
Encroach Node=103093
       1   357.8     870
Encroach Node=102596
       1     306     708
Encroach Node=102085
       1     313     620
Encroach Node=101594
       1  266.53  559.12
Encroach Node=101094
       1   248.1  536.64
Encroach Node=100592
       1  517.98     852
Encroach Node=100096
       1   697.8 1074.27
Encroach Node=99605
       1  757.24    1187
Encroach Node=99158
       1  862.74 1250.56
Encroach Node=98885
       1     894    1266
Encroach Node=98588
       1  867.18  1330.5
Encroach Node=98172
       1     970 1384.68
Encroach Node=97825
       1     904    1497
Encroach Node=97644
       1     840  1495.2
Encroach Node=97586
       1     940 1556.78
Encroach Node=97357
       1 1009.29    1598
Encroach Node=97026
       1  848.94  1529.5
Encroach Node=96581
       1  770.35 1515.03
Encroach Node=96092
       1  632.27 1360.03
Encroach Node=95593
       1  281.16   867.9
Encroach Node=95116
       1  287.35   885.4
Encroach Node=94615
       1  289.55  954.94
Encroach Node=94197
       1  253.43    1020
Encroach Node=93748
       1   365.3  929.91
Encroach Node=93429
       1  275.55   750.8
Encroach Node=93088
       1  314.55     600
Encroach Node=92598
       1   370.8   629.7
Encroach Node=92096
       1   359.6   643.7
Encroach Node=91594
       1   377.9  704.65
Encroach Node=91092
       1   366.1   692.7
Encroach Node=90595
       1   348.9   669.8
Encroach Node=90092
       1     345  619.45
Encroach Node=89594
       1   283.9  605.51
Encroach Node=89098
       1   199.9  705.68
Encroach Node=88588
       1  143.33  809.53
Encroach Node=88094
       1     163   882.9
Encroach Node=87743
       1     160     871
Encroach Node=87424
       1     430     898
Encroach Node=87222
       1  338.46   731.4
Encroach Node=86574
       1   359.4     660
Encroach Node=86090
       1     355  654.73
Encroach Node=85602
       1   224.1   479.5
Encroach Node=85096
       1     260  544.51
Encroach Node=84625
       1  272.53   634.8
Encroach Node=84090
       1  255.87   900.9
Encroach Node=83683
       1  297.16  1156.7
Encroach Node=83204
       1  231.83  1065.3
Encroach Node=82824
       1   251.7    1015
Encroach Node=82603
       1  169.35   835.2
Encroach Node=82366
       1  480.66    1000
Encroach Node=82087
       1   362.6   816.1
Encroach Node=81605
       1  260.34  590.51
Encroach Node=81094
       1     300  604.13
Encroach Node=80593
       1   333.8  853.72
Encroach Node=80103
       1   374.2 1214.73
Encroach Node=79574
       1  389.19 1245.15
Encroach Node=79194
       1   320.1  1131.3
Encroach Node=78647
       1   297.9  1004.6
Encroach Node=78207
       1   232.1   830.4
Encroach Node=77737
       1   200.8     708
Encroach Node=77329
       1   220.3  600.64
Encroach Node=77004
       1  378.58   808.3
Encroach Node=76591
       1  671.44 1108.28
Encroach Node=76069
       1  779.95  1210.9
Encroach Node=75598
       1  618.75  1024.6
Encroach Node=74985
       1  630.85  1003.4
Encroach Node=74547
       1   569.1   996.6
Encroach Node=74265
       1     660    1060
Encroach Node=74035
       1  797.23  1083.6
Encroach Node=73941
       1     734  1012.6
Encroach Node=73493
       1  352.03  693.44
Encroach Node=73157
       1     210  489.65
Encroach Node=72638
       1     314     540
Encroach Node=72286
       1     285  513.96
Encroach Node=71758
       1   262.9  530.93
Encroach Node=71294
       1     220  562.98
Encroach Node=70803
       1  279.75   809.5
Encroach Node=70397
       1  332.64     843
Encroach Node=70061
       1  303.63   826.2
Encroach Node=69543
       1   204.2  975.62
Encroach Node=69091
       1  278.05 1092.78
Encroach Node=68603
       1   353.7    1241
Encroach Node=68270
       1  419.06 1236.81
Encroach Node=68092
       1   447.2  1172.7
Encroach Node=67434
       1     472    1142
Encroach Node=67141
       1  641.27 1426.31
Encroach Node=66419
       1  827.68 1838.45
Encroach Node=65845
       1  826.52 1869.74
Encroach Node=65344
       1  665.08  1733.3
Encroach Node=64735
       1  691.05  1590.3
Encroach Node=64261
       1  727.15  1368.1
Encroach Node=63731
       1  626.44 1297.58
Encroach Node=63168
       1   538.1 1471.03
Encroach Node=62740
       1   506.9  1372.5
Encroach Node=62182
       1  422.44  1253.6
Encroach Node=61774
       1   346.6  1123.9
Encroach Node=61273
       1     445     912
Encroach Node=61050
       1  350.09   836.4
Encroach Node=60964
       1  356.59   843.7
Encroach Node=60721
       1  260.15  753.66
Encroach Node=60342
       1     245     849
Encroach Node=60258
       1  237.49     855
Encroach Node=60017
       1  279.58     938
Encroach Node=59590
       1  222.93  878.22
Encroach Node=59080
       1  202.86   913.9
Encroach Node=58598
       1   191.5  766.86
Encroach Node=58094
       1  139.96  592.09
Encroach Node=57792
       1   424.3  861.95
Encroach Node=57523
       1  331.83  783.69
Encroach Node=57102
       1  341.14  814.84
Encroach Node=56567
       1  194.76  752.45
Encroach Node=56086
       1  145.31   663.6
Encroach Node=55592
       1  210.87  681.19
Encroach Node=55143
       1  241.78     805
Encroach Node=54813
       1   295.4  908.81
Encroach Node=54405
       1  390.93  980.08
Encroach Node=54191
       1     323   874.8
Encroach Node=53857
       1     315     956
Encroach Node=53535
       1     374  864.16
Encroach Node=53091
       1  432.08  778.41
Encroach Node=52594
       1   414.4  732.95
Encroach Node=52093
       1   349.2  685.14
Encroach Node=51590
       1  403.83  751.22
Encroach Node=51167
       1   420.3  722.89
Encroach Node=50618
       1  320.51   683.1
Encroach Node=50090
       1  124.25  415.15
Encroach Node=49592
       1  319.94     596
Encroach Node=49103
       1  335.82   732.5
Encroach Node=48593
       1   306.2  760.85
Encroach Node=48096
       1     310  836.85
Encroach Node=47594
       1   308.5  804.93
Encroach Node=47095
       1   298.3  756.13
Encroach Node=46592
       1   325.7  787.98
Encroach Node=46086
       1  318.38   783.3
Encroach Node=45593
       1   309.8   714.4
Encroach Node=45098
       1  270.02  742.26
Encroach Node=44710
       1  205.17  800.33
Encroach Node=44012
       1   375.8  1142.2
Encroach Node=43591
       1  313.55  892.97
Encroach Node=43094
       1  279.78     740
Encroach Node=42593
       1  554.98 1089.45
Encroach Node=42103
       1  906.58 1421.53
Encroach Node=41601
       1  775.33 1665.55
Encroach Node=41429
       1   785.4    1712
Encroach Node=41094
       1  805.55    1761
Encroach Node=40588
       1   454.7 1515.14
Encroach Node=40081
       1  422.55 1444.81
Encroach Node=39590
       1  538.88 1494.82
Encroach Node=39074
       1  329.52 1537.63
Encroach Node=38546
       1  319.55 1629.39
Encroach Node=38087
       1  246.05    1672
Encroach Node=37630
       1  276.85 1565.66
Encroach Node=37100
       1  229.97 1324.71
Encroach Node=36477
       1  209.33 1128.01
Encroach Node=36095
       1  179.84 1039.92
Encroach Node=35592
       1   216.1   989.7
Encroach Node=35093
       1  192.85  836.26
Encroach Node=34591
       1   298.7  814.61
Encroach Node=34094
       1  295.93  789.77
Encroach Node=33591
       1   311.1  775.53
Encroach Node=33095
       1  379.76  801.58
Encroach Node=32593
       1   387.3  808.34
Encroach Node=32099
       1  444.69  815.15
Encroach Node=31601
       1   423.2  877.29
Encroach Node=31127
       1  682.23 1079.34
Encroach Node=30591
       1  530.54     877
Encroach Node=30097
       1  477.86   838.9
Encroach Node=29604
       1  911.09 1406.99
Encroach Node=28961
       1  294.18  798.93
Encroach Node=28594
       1  171.63  733.55
Encroach Node=28093
       1  210.65  866.65
Encroach Node=27590
       1  288.97 1358.41
Encroach Node=27063
       1   368.8 1593.95
Encroach Node=26683
       1  378.27 1775.42
Encroach Node=26094
       1   270.8 1533.58
Encroach Node=25602
       1  256.33 1446.85
Encroach Node=25280
       1   398.3  1527.7
Encroach Node=24863
       1   306.3 1370.94
Encroach Node=24220
       1   317.4 1199.08
Encroach Node=23598
       1   299.2 1095.33
Encroach Node=23095
       1   269.2  996.12
Encroach Node=22561
       1     361    1201
Encroach Node=22094
       1   334.7  1318.5
Encroach Node=21600
       1   337.5  1586.6
Encroach Node=21089
       1  275.69 1601.55
Encroach Node=20604
       1  185.87 1648.75
Encroach Node=19966
       1  444.69  1374.6
Encroach Node=19598
       1   505.5  1502.6
Encroach Node=19454
       1  450.05    1442
Encroach Node=19043
       1     457    1524
Encroach Node=18605
       1  525.08  1583.3
Encroach Node=17812
       1   738.3 1762.24
Encroach Node=17573
       1   754.2 1811.99
Encroach Node=17180
       1   984.5 1791.17
Encroach Node=16814
       1    1246  2026.9
Encroach Node=16243
       1   753.6 2057.27
Encroach Node=15453
       1   851.7  1777.5
Encroach Node=15317
       1     584  1526.6
Encroach Node=14885
       1     540  1372.4
Encroach Node=14079
       1   304.5  738.03
Encroach Node=13595
       1     305  820.84
Encroach Node=13127
       1   110.4   702.3
Encroach Node=12750
       1   202.8  756.04
Encroach Node=12095
       1  486.54 1398.32
Encroach Node=11613
       1  601.86 1306.93
Encroach Node=11100
       1  644.25 1408.28
Encroach Node=10603
       1  670.17 1367.75
Encroach Node=9919
       1  848.58 1278.19
Encroach Node=9595
       1     622    1165
Encroach Node=9086
       1     535    1090
Encroach Node=8592
       1   336.3   846.1
Encroach Node=8091
       1  332.38     853
Encroach Node=7597
       1  397.59  927.64
Encroach Node=7131
       1  432.03  1001.7
Encroach Node=6597
       1   416.1  903.88
Encroach Node=6094
       1  483.89  868.22
Encroach Node=5577
       1     296  731.32
Encroach Node=5154
       1     220     672
Encroach Node=4715
       1   378.5   796.2
Encroach Node=4262
       1   178.5  639.63
Encroach Node=3883
       1  147.19   579.8
Encroach Node=3541
       1   269.5     652
Encroach Node=3236
       1     364  761.99
Encroach Node=3181
       1     441  826.58
Encroach Node=2837
       1   322.8   894.3
Encroach Node=2412
       1  300.06 1158.09
Encroach Node=1918
       1  421.58 1386.02
Encroach Node=1498
       1  360.42 1329.98
Encroach Node=1244
       1  266.57 1127.02
Encroach Node=791
       1   513.9  921.54
Encroach Node=470
       1  700.14 1151.48
Encroach Node=0
       1   752.3  1136.3
Computation Interval=0.1SEC
Output Interval=1SEC
Instantaneous Interval=Max Profile
Mapping Interval=1HOUR
Computation Time Step Use Courant=        0
Computation Time Step Use Time Series=    0
Computation Time Step Count To Double=0
Computation Time Step Max Doubling=0
Computation Time Step Max Halving=0
Computation Time Step Residence Courant=0
Run HTab= 0
Run UNet= 0
Run Sediment= 0
Run PostProcess= 0
Run WQNet= 0
Run RASMapper=-1
UNET Theta= 0
UNET Theta Warmup= 0
UNET ZTol= 0
UNET ZSATol= 0
UNET MxIter= 0
UNET Max Iter WO Improvement= 0
UNET MaxInSteps= 0
UNET DtIC= 0
UNET DtMin= 0
UNET MaxCRTS= 0
UNET WFStab= 0
UNET SFStab= 0
UNET WFX= 1
UNET SFX= 1
UNET Gravity=32.174
UNET 1D Methodology=Finite Difference
UNET DSS MLevel= 1
UNET Pardiso=0
UNET DZMax Abort= 0
UNET Use Existing IB Tables= 0
UNET Froude Reduction=False
UNET Froude Limit= 0
UNET Froude Power= 0
UNET D1 Cores= 0
UNET WindReference=Eulerian
UNET WindDragFormulation=Hsu (1988)
UNET D2 Coriolis=0
UNET D2 Cores= 0
UNET D2 Theta= 1
UNET D2 Theta Warmup= 1
UNET D2 Z Tol= 0.01
UNET D2 Volume Tol= 0.01
UNET D2 Max Iterations= 20
UNET D2 Equation= 0
UNET D2 RampUpFraction=0.1
UNET D2 TimeSlices= 1
UNET D2 Turbulence Formulation=Non-Conservative (original)
UNET D2 Eddy Viscosity=0.3
UNET D2 Transverse Eddy Viscosity=0.1
UNET D2 Smagorinsky Mixing=0
UNET D2 BCVolumeCheck=0
UNET D2 Cores=0
UNET D2 SolverType=PARDISO (Direct)
UNET D2 Minimum Iterations= 2147483647
UNET D2 Maximum Iterations= 2147483647
UNET D2 Restart Number= 10
UNET D2 Relaxation Coeff=1.3
UNET D2 SOR Precondition Iterations= 10
UNET D2 ILUT Maximum Fill= 8
UNET D2 ILUT Tolerance=1E-08
UNET D1D2 MaxIter= 0
UNET D1D2 ZTol=0.01
UNET D1D2 QTol=0.1
UNET D1D2 MinQTol=1
DSS File=dss
Write IC File= 0
Write IC File at Fixed DateTime=0
Write IC File at Sim End=0
Echo Input=False
Echo Parameters=False
Echo Output=False
Write Detailed= 0
HDF Write Warmup=0
HDF Write Time Slices=0
HDF Flush=0
HDF Compression= 1
HDF Chunk Size= 1
HDF Spatial Parts= 1
HDF Use Max Rows=0
HDF Fixed Rows= 1
Calibration Method= 0
Calibration Iterations= 20
Calibration Max Change=0.05
Calibration Tolerance=0.2
Calibration Maximum=1.5
Calibration Minimum=0.5
Calibration Optimization Method= 1
WQ AD Non Conservative
WQ ULTIMATE=-1
WQ Max Comp Step=1HOUR
WQ Output Interval=15MIN
WQ Output Selected Increments= 0
WQ Output face flow=0
WQ Output face velocity=0
WQ Output face area=0
WQ Output face dispersion=0
WQ Output cell volume=0
WQ Output cell surface area=0
WQ Output cell continuity=0
WQ Output cumulative cell continuity=0
WQ Output face conc=0
WQ Output face dconc_dx=0
WQ Output face courant=0
WQ Output face peclet=0
WQ Output face adv mass=0
WQ Output face disp mass=0
WQ Output cell mass=0
WQ Output cell source sink temp=0
WQ Output nsm pathways=0
WQ Output nsm derived pathways=0
WQ Create Restart=0
WQ Fixed Restart=0
WQ System Summary=0
WQ Write To DSS=0
Sorting and Armoring Iterations= 10
XS Update Threshold= 0.02
Bed Roughness Predictor= 0
Hydraulics Update Threshold= 0.02
Energy Slope Method= 1
Volume Change Method= 1
Sediment Retention Method= 0
Sediment TS Multiplier= 1
Warm Up Method= 0
XS Weighting Method= 0
Number of US Weighted Cross Sections= 1
Number of DS Weighted Cross Sections= 1
Upstream XS Weight=0
Main XS Weight=1
Downstream XS Weight=0
Number of DS XS's Weighted with US Boundary= 1
Upstream Boundary Weight= 1
Weight of XSs Associated with US Boundary= 0
Number of US XS's Weighted with DS Boundary= 1
Downstream Boundary Weight= 0.5
Weight of XSs Associated with DS Boundary= 0.5
Percentile Method= 0
Sediment Output Level= 3
Mass or Volume Output= 0
Output Increment Type= 1
Profile and TS Output Increment= 1
Transport Output Increment 1
XS Output Flag= 0
XS Output Increment= 10
Read HDF5 Sediment Hotstart= 0
Sediment Hotstart Type= 0
Write Gradation File= 0
Read Gradation Hotstart= 0
Write HDF5 File= 1
Write Binary Output= 1
Write DSS Sediment File= 0
DSS Sediment Output Type= 1
SV Curve= 0
Specific Gage Flag= 0
Subcell Erosion Methods= 0
Subcell Deposition Methods= 0
Advection Scheme= 1
Matrix Solver= 0
Implicit Weighting Factor= 1
Maximum Outer Loop Convergence Iterations= 5
Convergence Maximum Absolute= 0.001
Convergence RMSE= 0.0001
Grain Fractions Max Abs Error= 0.001
Max Subgrid Regions= 1
Max Subgrid Length Scale= 3.402823E+38
Initial Layer Thickness= 3.402823E+38
Min Layer Thickness= 3.402823E+38
Max Layer Thickness= 3.402823E+38
Number of Layers= 5

--- GRNBRRRV.f01 (steady flow) ---

Flow Title=Flow
Program Version=6.10
Number of Profiles= 7
Profile Names=01pct,FW,10pct,04pct,02pct,0_2pct,01plus
River Rch & RM=GRNBRRRV,Main            ,352248
   14800   14800    5110    7780   10700   31500   19100
River Rch & RM=GRNBRRRV,Main            ,351910
   23900   23900    8850   12800   17500   49800   31000
River Rch & RM=GRNBRRRV,Main            ,339054
   27300   27300   10800   15500   20500   53900   36100
River Rch & RM=GRNBRRRV,Main            ,260568
   32900   32900   15100   20600   26000   57800   41000
River Rch & RM=GRNBRRRV,Main            ,246087
   40900   40900   20800   27400   33500   65000   50000
River Rch & RM=GRNBRRRV,Main            ,157091
   45600   45600   24200   31500   38000   69300   55400
River Rch & RM=GRNBRRRV,Main            ,116458
   56800   56800   32600   41300   48700   79300   67900
River Rch & RM=GRNBRRRV,Main            ,82087
   58700   58700   34800   43600   50800   80000   69100
River Rch & RM=GRNBRRRV,Main            ,11613
   60300   60300   36700   45500   52700   80500   70100
Boundary for River Rch & Prof#=GRNBRRRV,Main            , 1
Up Type= 0
Dn Type= 1
Dn Known WS=1984.1
Boundary for River Rch & Prof#=GRNBRRRV,Main            , 2
Up Type= 0
Dn Type= 1
Dn Known WS=1985.1
Boundary for River Rch & Prof#=GRNBRRRV,Main            , 3
Up Type= 0
Dn Type= 1
Dn Known WS=1979.3
Boundary for River Rch & Prof#=GRNBRRRV,Main            , 4
Up Type= 0
Dn Type= 1
Dn Known WS=1981.2
Boundary for River Rch & Prof#=GRNBRRRV,Main            , 5
Up Type= 0
Dn Type= 1
Dn Known WS=1982.6
Boundary for River Rch & Prof#=GRNBRRRV,Main            , 6
Up Type= 0
Dn Type= 1
Dn Known WS=1987.7
Boundary for River Rch & Prof#=GRNBRRRV,Main            , 7
Up Type= 0
Dn Type= 1
Dn Known WS=1985.9
DSS Import GetInterval= 0
DSS Import GetPeak= 0
DSS Import FillOption= 0

--- GRNBRRRV.g01 (geometry) ---

Geom Title=Geometry
Program Version=6.10

River Reach=GRNBRRRV        ,Main
Reach XY= 30
2302743.24105321564208.3172752192297182.41700001 543330.51000002
2293313.03099999542191.2919999962295970.67900003537837.885000005
2289776.60999998533959.3110000042289605.17200001520851.815000013
2273944.48800002500816.5040000082276749.62200002496719.465000018
2265634.62000002497778.1580000072269105.53200004490835.468999997
2258902.60600001471879.3390000022253283.43200003471143.158000007
2257935.59900002468728.1400000012249354.27500002467960.932999998
2251386.15100002464000.9590000062246104.04400003463342.215000004
2241037.05900002449157.8470000182231801.38100003451700.728000015
2228953.18700001448576.4170000112226938.49000001435757.577000022
2219198.06099999434708.8410000062221115.44600001428032.803000018
2213411.50500001416278.2260000112205940.20500001415126.846000001
2205986.49600002403632.8369999982192198.75200003402997.251000002
2194777.12400003395671.743000001     2190360.456387386.110000014
2186371.67300002388585.215000018 2189061.2087009 379664.83233352

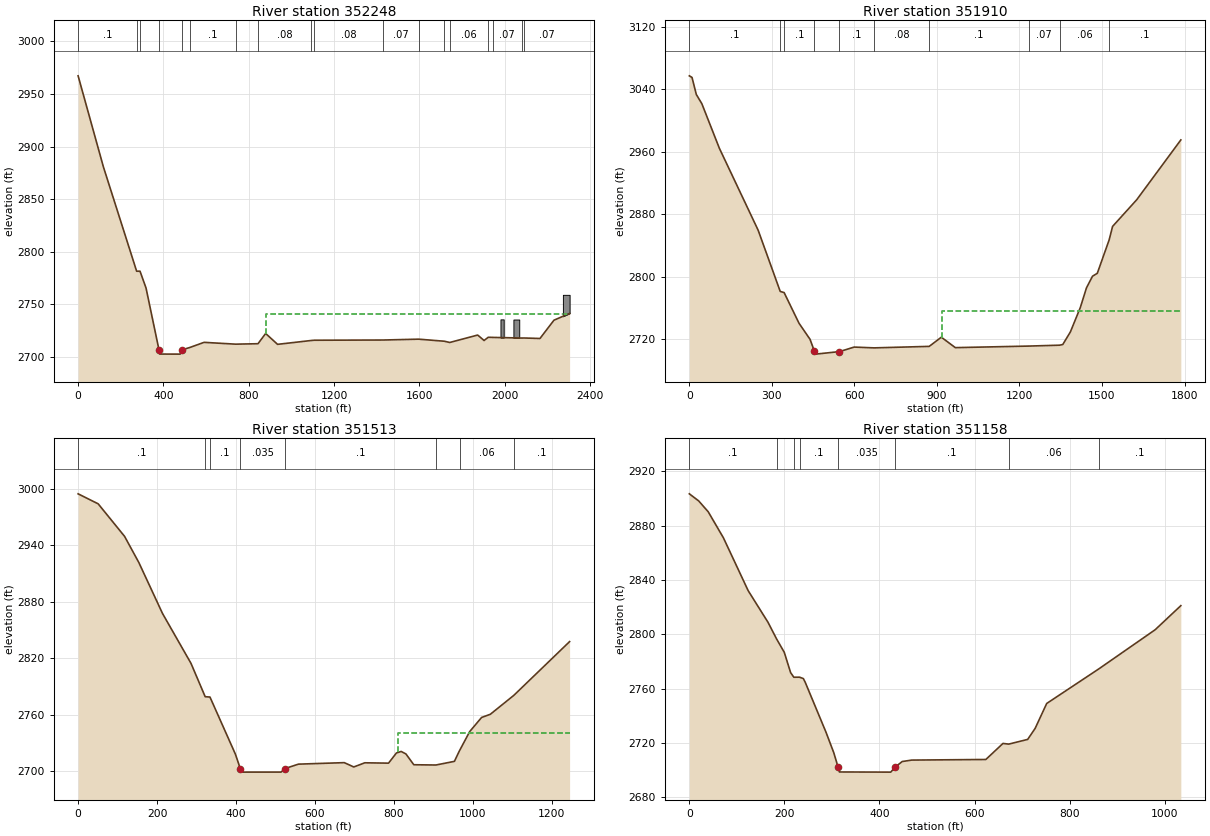
Type RM Length L Ch R = 1 ,352248  ,343,337.4,312.8
BEGIN DESCRIPTION:
channel burned 2.38':
lidar invert = 2705.18
effective invert = 2702.80
END DESCRIPTION:
XS GIS Cut Line= 3
2302745.52858504563766.8236327612302740.95700559564649.138466614
2303870.49804391565512.909186835
#Sta/Elev= 30
       0 2967.14   118.4 2880.76   274.4 2781.56   290.2 2781.57   318.4 2765.62
  379.21 2706.85   382.4 2702.86   478.4  2702.8  485.82 2706.74     525 2709.19
   590.4 2713.99   738.4 2712.27   843.4 2712.69   879.2 2722.42   935.1 2712.09
  1093.1 2715.76  1107.9    2716  1430.2  2716.2  1596.4 2717.01  1717.2 2715.05
  1742.4 2713.87  1873.3 2720.92  1903.3 2715.75  1922.8  2718.8  1943.8 2718.69
  2080.2 2718.08  2091.7 2718.11  2165.4 2717.66  2230.9 2735.03  2304.3  2741.5
#Mann= 18 ,-1,0
       0      .1       0   274.4    .016       0   290.2      .1       0
  379.21    .035       0  485.82     .08       0     525      .1       0
   738.4     .07       0   843.4     .08       0  1093.1      .1       0
  1107.9     .08       0  1430.2     .07       0  1596.4     .08       0
  1717.2     .07       0  1742.4     .06       0  1922.8    .016       0
  1943.8     .07       0  2080.2    .016       0  2091.7     .07       0
#XS Ineff= 2 , 0
                          881.69         2740.58
Permanent Ineff=
       F       F
#Block Obstruct= 3 ,-1
 1980.19 1995.29 2735.82 2040.82 2068.19 2735.67 2272.82 2304.28 2759.12
Bank Sta=379.21,485.82
XS Rating Curve= 0 ,0
Exp/Cntr=0.3,0.1

Type RM Length L Ch R = 1 ,351910  ,395.3,397.4,407
BEGIN DESCRIPTION:
channel burned 2.97':
lidar invert = 2703.8
interpolated invert = 2700.83
END DESCRIPTION:
XS GIS Cut Line= 3
 2302367.0921394563715.8402644162302439.53524422564638.589751616
2301968.49269991565359.419352612
#Sta/Elev= 30
       0 3057.48     9.7 3055.42    25.4 3033.55    45.5 3021.72   109.1 2964.69
   250.1 2859.66   330.4 2781.16   344.5 2779.73   398.6 2740.46   438.7 2719.84
   454.7 2704.54   458.7 2700.83  545.79 2704.05   599.2 2709.87   671.4 2708.84
     872 2710.76   916.1 2722.52   966.9 2709.15  1234.5 2711.15    1346 2712.29
  1357.6 2713.18  1385.1 2729.23  1421.2 2760.44  1443.6 2785.68  1465.5 2800.64
    1483 2804.41    1526 2847.09  1538.6 2864.52  1626.2 2898.62  1786.7 2975.33
#Mann= 10 ,-1,0
       0      .1       0   330.4    .016       0   344.5      .1       0
   454.7    .035       0  545.79      .1       0   671.4     .08       0
     872      .1       0  1234.5     .07       0    1346     .06       0
    1526      .1       0
#XS Ineff= 2 , 0
                          918.31         2756.33
Permanent Ineff=
       F       F
Bank Sta=454.7,545.79
XS Rating Curve= 0 ,0
Exp/Cntr(USF)=0,0
Exp/Cntr=0.3,0.1

Type RM Length L Ch R = 1 ,351513  ,353.4,355.1,361.6
BEGIN DESCRIPTION:
channel burned 3.02':
lidar invert = 2702.38
interpolated invert = 2699.26
END DESCRIPTION:
XS GIS Cut Line= 3
2301988.68700678563787.5088895482302032.29617527564700.394149935
 2301910.1905035565008.565607263
#Sta/Elev= 30
       0 2994.48    50.8 2983.88   117.8 2949.33     154  2921.5   213.9 2867.53
     286 2814.68     322 2779.26   334.1 2778.92   398.6 2718.27  410.84  2703.1
   414.1 2699.26   514.3  2699.3  524.52  2703.1   558.3 2707.73   674.4 2709.32
   698.5 2704.74   726.5 2709.16   786.6 2708.78   806.6 2719.58   818.6 2721.18
   830.6 2718.57   850.6 2707.09   906.7 2706.81   953.5 2710.69   966.4 2721.97
   992.2 2742.26  1022.3 2757.22  1044.6 2760.65  1104.1 2780.72  1245.4 2837.72
#Mann= 8 ,-1,0
       0      .1       0     322    .016       0   334.1      .1       0
  410.84    .035       0  524.52      .1       0   906.7     .08       0
   966.4     .06       0  1104.1      .1       0
#XS Ineff= 2 , 0
                          810.82          2740.7
Permanent Ineff=
       F       F
Bank Sta=410.84,524.52
XS Rating Curve= 0 ,0
Exp/Cntr(USF)=0,0
Exp/Cntr=0.3,0.1

Type RM Length L Ch R = 1 ,351158  ,514,521.5,546.3
BEGIN DESCRIPTION:
channel burn 2.76':
lidar invert = 2701.26
effective invert = 2698.50
c/e of 0.5/0.7 placed to correct drawdown in larger profiles
END DESCRIPTION:
XS GIS Cut Line= 2
2301651.08055761563917.4613347482301669.21839431564951.318026802
#Sta/Elev= 30
       0 2903.32    19.7 2898.09    39.7 2890.11    71.7 2870.93   123.7 2832.09
   165.6 2808.71   183.7 2796.41   199.7 2786.69   213.1  2771.7   219.8 2768.34
   231.8 2768.37   239.8 2767.36   243.8 2764.62   287.8 2727.61   303.8 2712.83
  313.11    2702   315.8 2698.62   423.8  2698.5   432.1 2701.95   447.8  2706.3
   467.8 2707.36   623.8 2707.81   659.8 2719.62   671.8 2719.11   711.8 2722.58
   727.5  2730.7   751.8 2749.02   861.8 2774.56     980  2803.3    1034 2821.02
#Mann= 8 ,-1,0
       0      .1       0   183.7     .06       0   219.8    .016       0
   231.8      .1       0  313.11    .035       0   432.1      .1       0
   671.8     .06       0   861.8      .1       0
Bank Sta=313.11,432.1
XS Rating Curve= 0 ,0
Exp/Cntr(USF)=0,0
Exp/Cntr=0.7,0.5