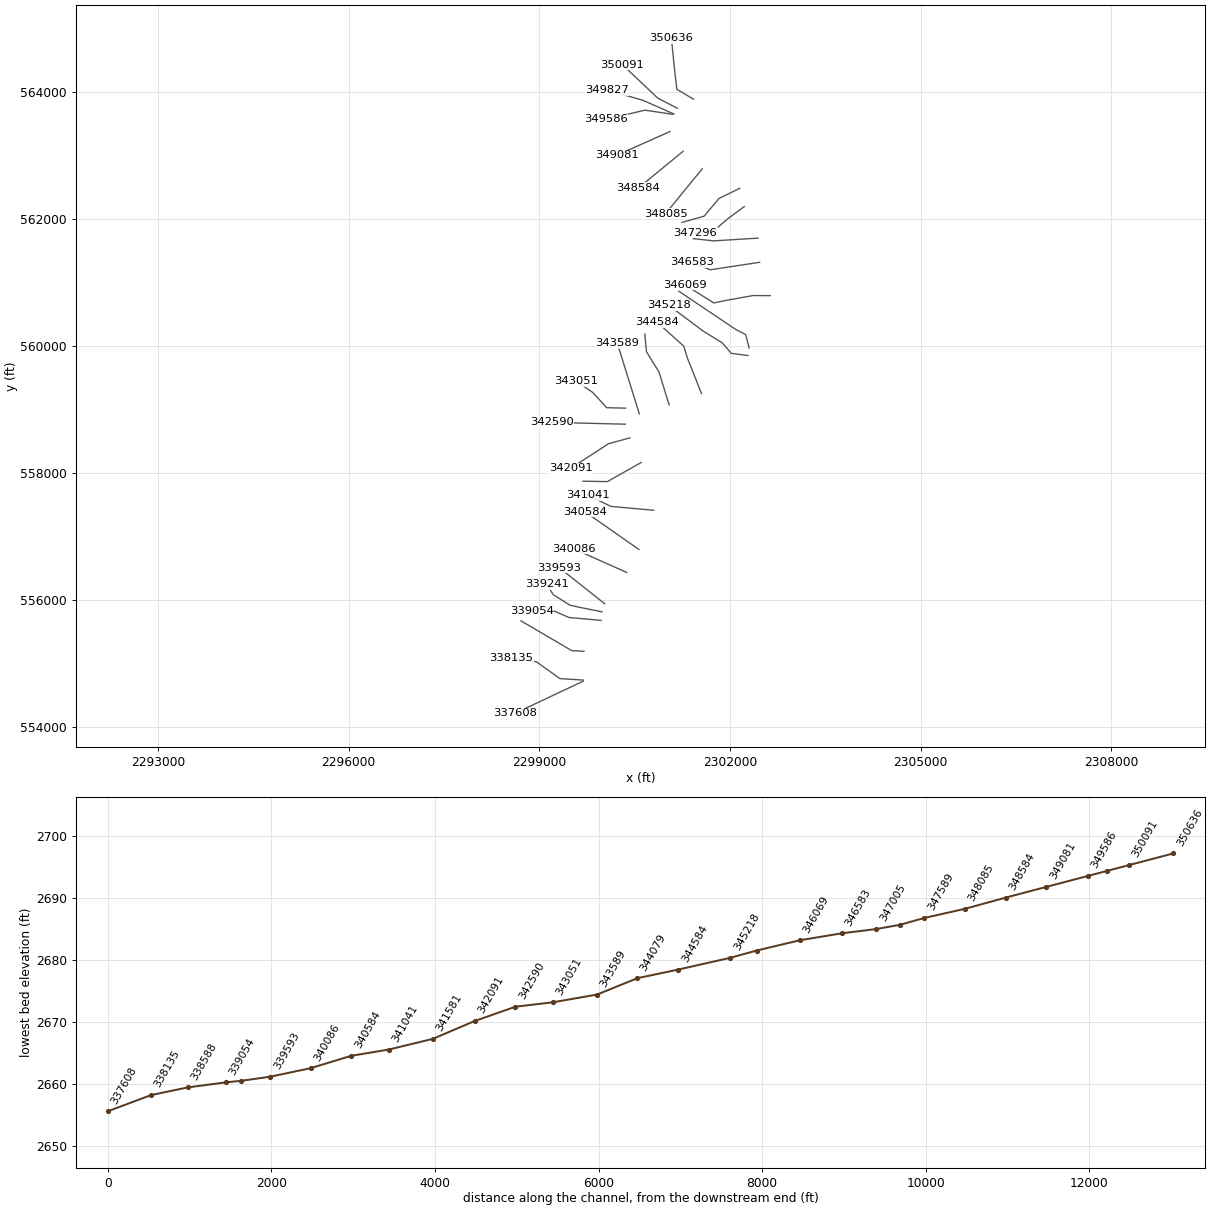
HEC-RAS study GRNBRRRV.prj: GRNBRRRV

--- GRNBRRRV.g01 (geometry) --- (continued)

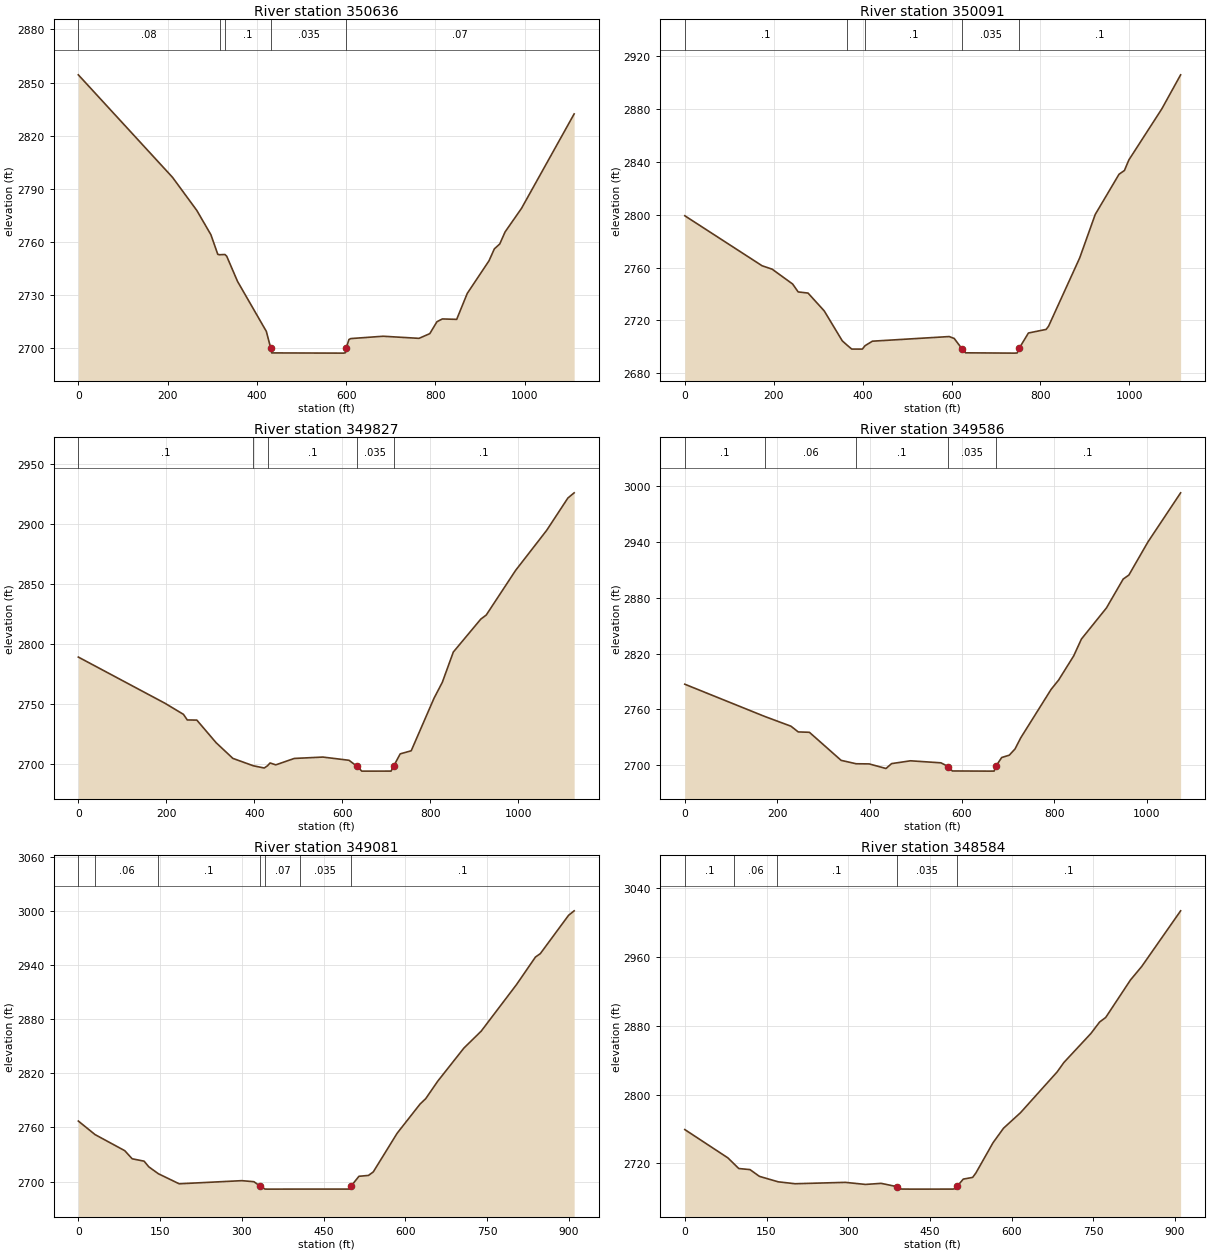
Type RM Length L Ch R = 1 ,350636  ,401.4,545.4,620.7
BEGIN DESCRIPTION:
channel burned 3.13':
lidar invert = 2700.29
interpolated invert= 2697.16
END DESCRIPTION:
XS GIS Cut Line= 6
2301424.35769156563881.1856196372301163.45827897564036.524219722
 2301148.5324558564150.9675603962301138.15222722564245.392896473
2301120.20574081564403.0913999832301076.99782197564839.104635566
#Sta/Elev= 30
       0 2854.38   211.1 2796.45   265.6 2777.72   297.1 2764.02   312.4 2752.99
   316.4 2752.74   328.5 2752.88   332.5 2751.89   356.7 2737.68   421.2 2709.46
   431.1 2699.95   433.4 2697.28   594.4 2697.16   598.4 2697.37     600 2699.95
   606.4 2704.88   610.5 2705.38   682.9  2706.7   763.3 2705.51   787.4 2708.16
   803.5  2714.9   815.5 2716.47   847.7 2716.23   871.4  2730.9   920.1 2749.32
   932.1 2756.05   944.2 2758.83   956.1 2765.62   992.9 2778.93  1110.9  2832.3
#Mann= 5 ,-1,0
       0     .08       0   316.4    .016       0   328.5      .1       0
   431.1    .035       0     600     .07       0
Bank Sta=431.1,600
XS Rating Curve= 0 ,0
Exp/Cntr(USF)=0,0
Minor Loss Coefficient=0
Exp/Cntr=0.3,0.1

Type RM Length L Ch R = 1 ,350091  ,158.3,263.9,298.2
BEGIN DESCRIPTION:
channel burned 2.5' to transition from detailed to approximate zone:
lidar = 2697.77
interpolated = 2695.27
END DESCRIPTION:
XS GIS Cut Line= 3
2301170.48497262563737.4433644662300863.52047795563896.819525945
     2300304.231      564425.141
#Sta/Elev= 30
       0  2799.3   173.9 2761.42   196.4 2758.86   242.5 2747.62     255 2741.62
   277.2 2740.75   313.6 2727.25   354.2 2704.57   365.5 2701.17   375.5 2698.34
   399.4 2698.33   405.5 2700.93     422 2704.31   594.7 2707.82     606 2706.37
  623.34 2698.62   631.5  2695.5   741.2 2695.27   747.5 2695.38   752.2    2699
   772.9 2710.51   812.7 2713.23   818.2 2715.68   888.1  2767.3   923.1 2800.26
   976.7 2830.75   988.8 2833.58   998.8 2841.58  1072.9 2880.24  1115.2 2906.02
#Mann= 5 ,-1,0
       0      .1       0   365.5    .045       0   405.5      .1       0
  623.34    .035       0   752.2      .1       0
Bank Sta=623.34,752.2
XS Rating Curve= 0 ,0
Exp/Cntr=0.3,0.1

Type RM Length L Ch R = 1 ,349827  ,126.2,240.8,271.1
BEGIN DESCRIPTION:
channel burned 2.53' to transition from detailed to approximate zone:
lidar = 2696.88
interpolated = 2694.35
END DESCRIPTION:
XS GIS Cut Line= 3
2301114.64900482563648.4696588682300627.75599648563863.658979517
2300056.09143759564026.681192129
#Sta/Elev= 30
       0 2789.21   196.5 2750.88   238.9 2741.57   247.6 2736.92   269.3 2736.79
   313.2 2717.96   351.2 2704.95   397.6 2698.81   422.5 2696.95     430 2698.84
   435.7 2701.13   448.8 2699.57   490.7  2704.9   555.9 2706.04   615.1 2703.37
   633.5 2698.34   644.2 2694.35   710.7 2694.37  716.41 2698.41   731.5 2708.71
   756.5 2711.27   808.3 2754.96   827.2 2768.22   852.2  2793.4   914.6 2820.77
     927 2824.18   993.6 2861.22  1064.3 2894.59  1112.6 2921.51  1126.8 2925.81
#Mann= 5 ,-1,0
       0      .1       0   397.6    .045       0     430      .1       0
   633.5    .035       0  716.41      .1       0
Bank Sta=633.5,716.41
XS Rating Curve= 0 ,0
Exp/Cntr(USF)=0,0
Exp/Cntr=0.3,0.1

Type RM Length L Ch R = 1 ,349586  ,470.7,505.5,517.7
BEGIN DESCRIPTION:
channel burned 2.31' to transition from detailed to approximate zone:
lidar = 2695.82
interpolated = 2693.51
END DESCRIPTION:
XS GIS Cut Line= 3
2301099.12526237563643.3048426172300659.01866824563707.906307778
     2300047.093      563563.577
#Sta/Elev= 30
       0 2787.09   172.8 2752.42   229.9 2741.87   245.6 2735.73   269.8 2735.32
   338.5  2705.1     371 2701.44   399.2 2701.28   435.6 2696.34   447.7  2701.6
   488.8 2704.63   554.6 2702.45  570.24 2698.45   579.1 2693.69   660.1 2693.51
   669.7 2693.57  673.27 2698.57   686.1 2708.16   702.5 2710.69   714.9 2717.32
   727.2 2729.24     793 2781.45   809.4 2791.62   841.9  2817.5   858.7  2835.7
   912.9 2869.22   949.1 2900.28   961.5 2904.66  1002.6 2940.16  1073.5 2993.16
#Mann= 5 ,-1,0
       0      .1       0   172.8     .06       0     371      .1       0
  570.24    .035       0  673.27      .1       0
Bank Sta=570.24,673.27
XS Rating Curve= 0 ,0
Exp/Cntr=0.3,0.1

Type RM Length L Ch R = 1 ,349081  ,467.3,496.4,513.5
BEGIN DESCRIPTION:
channel burned 0.99' to transition from detailed to approximate zone:
lidar = 2692.75
interpolated = 2691.76
END DESCRIPTION:
XS GIS Cut Line= 2
     2301054.344       563371.57     2300223.465      563000.335
#Sta/Elev= 30
       0 2767.13    30.7 2752.14    85.2 2734.33    98.8 2725.36   120.7 2722.72
   129.4  2716.4     147 2708.77   185.1 2697.66     300 2701.13   322.2 2699.99
   333.5 2695.08   342.6 2691.82     348 2691.76   406.2  2691.8   496.1 2691.81
   500.1 2694.71     515 2705.97   532.5 2706.93   541.3 2710.81   585.1 2753.61
   627.2 2785.95   637.6 2791.94   659.5 2811.16   707.7 2847.96   739.3  2866.6
   804.1 2918.12     839 2948.73   847.9 2952.49   899.8 2994.94     910 2999.87
#Mann= 7 ,-1,0
       0      .1       0    30.7     .06       0     147      .1       0
   333.5    .035       0   342.6     .07       0   406.2    .035       0
   500.1      .1       0
Bank Sta=333.5,500.1
XS Rating Curve= 0 ,0
Exp/Cntr=0.3,0.1

Type RM Length L Ch R = 1 ,348584  ,481.7,499.3,512.4
XS GIS Cut Line= 2
     2301260.722      563060.034     2300556.964      562482.871
#Sta/Elev= 30
       0 2759.34    79.2 2726.35    99.1    2714   119.7 2712.75     137 2704.89
   171.4 2698.54   202.5 2696.31   294.7  2697.9   331.8 2695.49   360.5 2696.75
   389.3 2692.91   397.5 2690.13   414.5 2690.03   492.2 2690.06     497 2690.59
   499.8 2693.19   511.2 2701.69   528.4 2703.67   534.4 2708.86   565.9 2744.09
   585.1 2760.91   616.4 2779.05   683.6 2826.48   695.9 2837.39   745.6 2871.22
   761.4 2884.45   772.7 2889.81   818.1 2933.38   838.8 2949.14   910.2 3013.88
#Mann= 5 ,-1,0
       0      .1       0      90     .06       0     170      .1       0
   389.3    .035       0   499.8      .1       0
Bank Sta=389.3,499.8
XS Rating Curve= 0 ,0
Exp/Cntr=0.3,0.1

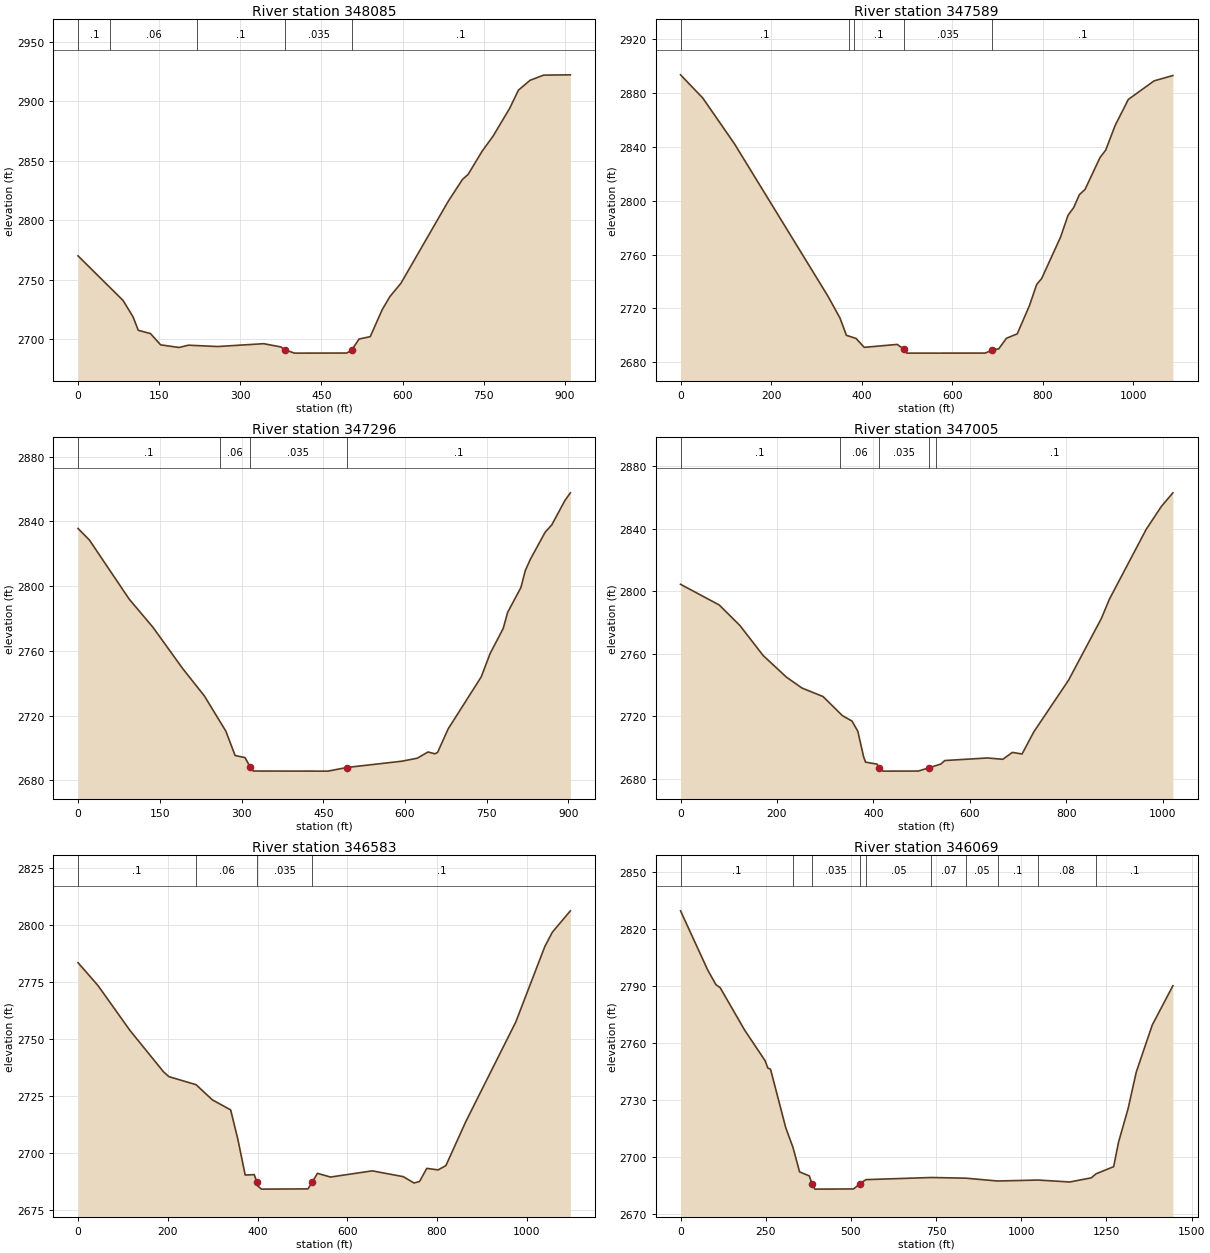
Type RM Length L Ch R = 1 ,348085  ,502.5,495.9,494.7
XS GIS Cut Line= 2
     2301560.864      562783.426     2300985.046      562078.775
#Sta/Elev= 30
       0 2770.03    83.3 2732.47   101.6  2718.8   111.4 2707.38   133.8 2704.72
   152.7 2695.16   186.9 2692.97   203.9  2694.9   257.9 2693.76   343.2 2696.15
   374.8 2693.43     383 2690.92   400.1 2688.22   496.7  2688.3  505.95 2690.88
   519.5 2700.06   540.1  2702.1   562.1 2724.67   576.3 2735.68     597 2747.12
   683.8 2815.57   710.6 2834.31   720.9 2838.43   746.9 2858.03   767.4 2870.89
   797.6  2893.9   813.9 2909.28   835.5 2917.64   860.4 2921.97     910 2922.24
#Mann= 5 ,-1,0
       0      .1       0      60     .06       0     220      .1       0
     383    .035       0  505.95      .1       0
Bank Sta=383,505.95
XS Rating Curve= 0 ,0
Exp/Cntr=0.3,0.1

Type RM Length L Ch R = 1 ,347589  ,317.7,292.7,281.1
XS GIS Cut Line= 4
2302152.26823456562477.5171776692301826.47556646 562317.92019164
2301590.07442986562038.1426997092301245.43265835561940.697239119
#Sta/Elev= 30
       0 2893.68    49.1 2876.44     119 2842.44   325.3 2729.21     352 2712.91
   366.3 2699.99   387.6 2697.68   405.6 2691.05   478.5 2693.23   492.7 2689.81
   499.9 2686.75   672.7 2686.78   688.5 2689.03   702.7 2689.95   719.7 2697.82
   743.5 2701.09   770.3 2721.96   786.5 2737.86   797.5 2742.26   839.1 2772.97
   855.7 2789.26   868.2    2795   880.7 2804.56   893.2 2808.48   926.4 2832.24
   938.8 2837.68   959.7 2856.02   988.8 2875.38  1045.7 2889.19  1087.2 2893.16
#Mann= 5 ,-1,0
       0      .1       0  372.78     .06       0  382.78      .1       0
   492.7    .035       0   688.5      .1       0
Bank Sta=492.7,688.5
XS Rating Curve= 0 ,0
Exp/Cntr=0.3,0.1

Type RM Length L Ch R = 1 ,347296  ,364.9,291.5,238.9
XS GIS Cut Line= 4
2302222.96635831562189.5301200522301964.94356374561999.489379139
2301762.54244943561824.8991049672301450.44302126561777.002658071
#Sta/Elev= 30
       0 2835.62    20.8 2828.52    93.8    2792   137.6 2774.51   192.2 2748.98
     232 2732.06   271.2  2710.4   288.3 2695.31   306.5 2694.01  315.47 2688.45
   321.5 2685.72   458.7 2685.66   492.8 2687.89   594.2 2691.79   622.5 2693.65
   642.2  2697.5   654.9 2696.38   659.8  2697.2   679.2 2711.75   739.9  2743.9
   756.1 2758.25   780.3 2773.87   788.4 2783.79   812.7 2799.11   820.8 2809.62
   829.9 2816.48   857.2 2833.32   869.4 2837.86   893.7 2853.05   903.5 2857.65
#Mann= 4 ,-1,0
       0      .1       0     260     .06       0  315.47    .035       0
   492.8      .1       0
Bank Sta=315.47,492.8
XS Rating Curve= 0 ,0
Exp/Cntr(USF)=0,0
Exp/Cntr=0.3,0.1

Type RM Length L Ch R = 1 ,347005  ,415.5,422,429.6
XS GIS Cut Line= 3
2302439.16654214561693.0182096182301744.06049131561649.924319434
2301421.14811165561684.541981744
#Sta/Elev= 30
       0  2804.5    80.3 2791.26   123.2 2778.12   171.3 2758.95   219.4 2745.16
   251.7 2738.15   295.6 2732.69   335.6 2720.51   355.7 2716.97   367.7 2710.48
   379.7 2694.19   383.7 2690.72   407.8 2689.43   411.8 2687.23   419.8 2684.97
   493.3 2685.02     516 2687.16     540 2689.51     548 2691.74   636.7 2693.39
   668.3 2692.54   688.3 2696.95   708.4 2695.94   732.5 2709.98   804.7  2743.1
   872.9 2782.65   889.4  2794.9   965.9 2839.68   997.2 2854.27  1021.2 2863.02
#Mann= 5 ,-1,0
       0      .1       0     330     .06       0   411.8    .035       0
     516     .06       0     530      .1       0
Bank Sta=411.8,516
XS Rating Curve= 0 ,0
Exp/Cntr=0.3,0.1

Type RM Length L Ch R = 1 ,346583  ,516.3,514.3,517.3
BEGIN DESCRIPTION:
c/e 0.5/0.7 placed to correct drawdown in the 500 yr
END DESCRIPTION:
XS GIS Cut Line= 3
     2302464.415      561312.4842301687.67122937561194.472588384
2301399.63484972561312.907154849
#Sta/Elev= 30
       0 2783.56    44.7 2773.48   115.5 2753.91   190.4 2735.74   202.5  2733.6
     263 2730.07   299.6 2723.38   340.1 2719.02   356.3 2706.01   372.5 2690.45
   392.7 2690.64  398.61 2687.27   400.8 2685.57   408.9 2684.28   512.4 2684.38
   522.2 2687.43   533.5 2691.21   562.6 2689.58   655.7 2692.29   724.5 2689.76
   748.7 2686.98   760.9  2687.6   777.1 2693.38   802.4 2692.71   819.7 2694.59
     864 2713.85   975.4 2757.53  1040.3  2790.7    1057 2796.94  1097.1 2806.29
#Mann= 4 ,-1,0
       0      .1       0     263     .06       0  398.61    .035       0
   522.2      .1       0
Bank Sta=398.61,522.2
XS Rating Curve= 0 ,0
Exp/Cntr=0.7,0.5

Type RM Length L Ch R = 1 ,346069  ,587.1,528.1,468.7
XS GIS Cut Line= 5
 2302632.3053599 560787.349738062302364.34237265560788.903665973
 2301947.9293614560715.1638618992301744.10746555560672.616709747
2301280.94901897560961.407527238
#Sta/Elev= 30
       0 2829.39    80.1 2798.16   104.1 2790.54   116.1 2789.08   188.1 2766.73
   248.1 2750.65   256.1 2746.81   264.1 2746.16   308.8 2715.43     330 2705.08
   349.4 2692.22   377.8 2690.12   385.9 2686.04   394.1 2683.16   507.8 2683.25
  526.16 2685.96     544 2688.15   736.3 2689.27   837.6 2688.91   930.4 2687.43
  1049.8 2687.93  1142.1 2686.91  1205.4 2689.09  1219.5 2691.21  1271.1 2694.96
  1285.5 2707.89  1313.8 2725.68  1337.4 2744.65  1384.3 2769.36  1444.9 2790.02
#Mann= 10 ,-1,0
       0      .1       0     330     .08       0   385.9    .035       0
  526.16      .1       0     544     .05       0   736.3     .07       0
   837.6     .05       0   930.4      .1       0  1049.8     .08       0
  1219.5      .1       0
Bank Sta=385.9,526.16
XS Rating Curve= 0 ,0
Exp/Cntr=0.3,0.1

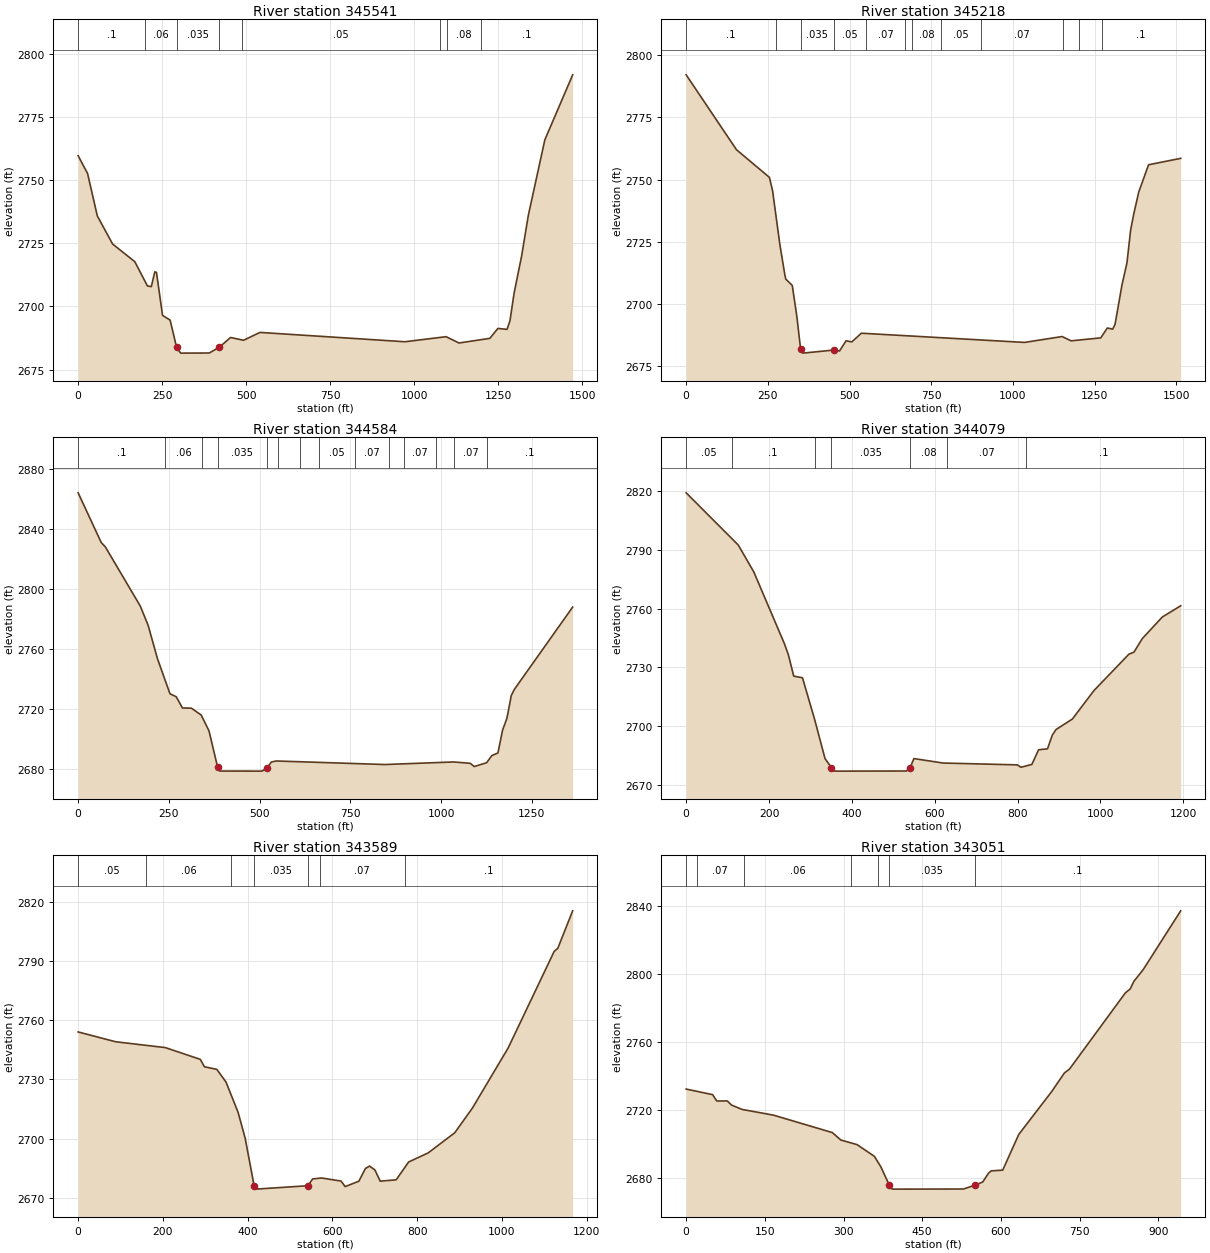
Type RM Length L Ch R = 1 ,345541  ,351.3,322.2,297.7
XS GIS Cut Line= 4
2302299.98560269559961.9232854352302245.70502347560172.757721513
2302086.64422046560256.6037261992301195.63191244560855.438011245
#Sta/Elev= 30
       0 2759.58    28.1 2752.54    57.1 2735.74   102.5 2724.66   168.6 2717.67
   206.2 2708.05   217.7 2707.83     228 2713.64     233 2713.46   251.1 2696.44
   273.7 2694.54  292.88 2683.77     305  2681.5   390.2 2681.55   419.9 2683.85
   453.5 2687.68   492.1 2686.59   540.9 2689.69   972.2    2686  1094.5    2688
    1133 2685.51  1224.6 2687.34  1248.7 2691.27  1275.9  2690.9  1284.6  2694.3
  1296.9 2705.24  1319.2  2719.9  1339.3 2736.07  1388.3 2765.86  1471.1 2791.58
#Mann= 8 ,-1,0
       0      .1       0     200     .06       0  292.88    .035       0
   419.9      .1       0  487.52     .05       0 1077.52      .1       0
 1097.52     .08       0 1197.52      .1       0
Bank Sta=292.88,419.9
XS Rating Curve= 0 ,0
Exp/Cntr=0.3,0.1

Type RM Length L Ch R = 1 ,345218  ,661,634.6,609.9
XS GIS Cut Line= 5
2302280.85481003559844.0827580952302018.54517724559878.736193295
2301878.49738438560043.1401240512301579.23034103560227.179864346
2301033.52055371 560635.70683814
#Sta/Elev= 30
       0 2792.08     154 2762.01   254.9 2750.89   264.6 2745.47   286.7 2724.04
   302.1 2711.74   304.9 2710.06   324.8  2707.5   338.9 2694.96   350.3 2681.95
   357.1 2680.33   451.7 2681.56   469.5  2681.2   489.5 2685.29     507 2684.83
   536.1 2688.33  1035.5 2684.63  1150.5 2686.99  1178.4 2685.27  1269.1 2686.46
  1289.1 2690.42  1305.4 2689.97  1312.7 2691.85    1334 2707.78  1349.2 2716.61
  1360.4 2729.77  1370.3 2736.39  1385.3 2745.05  1415.3 2755.96  1513.6 2758.54
#Mann= 12 ,-1,0
       0      .1       0  274.59     .06       0   350.3    .035       0
   451.7     .05       0  550.56     .07       0  670.56     .12       0
  690.56     .08       0  780.56     .05       0  901.88     .07       0
 1151.88      .1       0 1201.88     .08       0 1271.88      .1       0
Bank Sta=350.3,451.7
XS Rating Curve= 0 ,0
Exp/Cntr=0.3,0.1

Type RM Length L Ch R = 1 ,344584  ,513.5,504.3,502.7
XS GIS Cut Line= 4
     2301550.163      559245.9492301324.00028412559816.405193792
2301271.12166301559991.8292596652300850.57679739560370.418674164
#Sta/Elev= 30
       0 2863.98    63.7 2830.82    74.9 2827.95   171.3 2788.47   192.8 2775.71
   218.6 2753.41     253 2730.03   270.3 2728.02   287.5 2720.53   312.1 2720.42
   339.1 2715.82   360.6 2705.28384.43992680.973   390.7 2678.48   506.3 2678.44
519.69992680.473   532.7 2684.55   546.3  2685.2   845.2 2682.84  1034.2 2684.55
  1080.3 2683.66  1091.5 2681.49  1125.6 2684.06  1139.9  2688.8  1156.8 2690.56
  1169.6 2705.84  1181.5 2713.63  1193.6 2728.89  1202.1 2732.96  1362.7 2787.81
#Mann= 14 ,-1,0
       0      .1       0     240     .06       0     340    .025       0
384.4399    .035       0519.6999    .025       0     550     .05       0
     610    .025       0  663.65     .05       0  763.65     .07       0
  856.87     .08       0  896.87     .07       0  986.87      .1       0
 1036.87     .07       0 1126.87      .1       0
Bank Sta=384.4399,519.6999
XS Rating Curve= 0 ,0
Exp/Cntr=0.3,0.1

Type RM Length L Ch R = 1 ,344079  ,495.5,490.8,485.8
XS GIS Cut Line= 4
     2301040.735      559068.906 2300880.9343124559585.456674728
2300684.65166451559902.6665154852300658.44966129560181.486212266
#Sta/Elev= 30
       0 2819.14   125.9 2792.45   163.3 2778.75   237.3 2742.05   246.9 2736.35
   259.7 2725.53   280.8  2724.7   310.1 2703.46   335.2 2683.47350.57022678.825
   356.2 2677.06   368.7 2677.03     532 2677.09540.60412678.795   549.8 2683.44
   620.3 2681.16   799.1 2680.23   808.4 2679.01   834.5 2680.45   850.8 2687.93
   872.3 2688.42   883.9 2695.41   892.7 2698.24   932.3 2703.63   984.6 2718.21
  1068.9 2736.76    1081 2737.78  1101.1  2744.7  1149.3  2755.7  1193.8 2761.47
#Mann= 7 ,-1,0
       0     .05       0     110      .1       0     310     .06       0
350.5702    .035       0540.6041     .08       0   630.7     .07       0
   820.7      .1       0
Bank Sta=350.5702,540.6041
XS Rating Curve= 0 ,0
Exp/Cntr=0.3,0.1

Type RM Length L Ch R = 1 ,343589  ,500,538,584.8
XS GIS Cut Line= 2
     2300572.499      558924.7892300225.59583146560038.690225427
#Sta/Elev= 30
       0 2754.08    88.4 2749.11   205.7 2746.15   288.1 2740.19   297.9 2736.44
   327.2  2735.1   348.8 2728.71   377.5 2713.24   394.2 2700.08   415.2  2676.1
   419.4  2674.4   541.6 2676.12   553.4 2679.58   574.4 2680.04   620.3 2678.49
   629.9 2675.68   662.3 2678.42   677.8 2684.87   687.4 2686.09   700.1 2684.15
   712.6 2678.44   750.3 2679.12   779.7 2688.16   825.7 2692.75   888.6 2702.99
   930.5  2715.6  1014.3 2745.88  1123.2 2794.96  1131.6 2796.47  1166.7 2815.48
#Mann= 7 ,-1,0
       0     .05       0     160     .06       0     360    .025       0
   415.2    .035       0   541.6      .1       0     570     .07       0
     770      .1       0
Bank Sta=415.2,541.6
XS Rating Curve= 0 ,0
Exp/Cntr=0.3,0.1

Type RM Length L Ch R = 1 ,343051  ,399.3,460.2,521.7
XS GIS Cut Line= 4
2300354.59253268559015.8096893342300059.72565816 559022.66705851
 2299835.7182651 559264.960769362299572.85244673559443.252367911
#Sta/Elev= 30
       0 2732.09    50.4 2728.81    58.4 2725.06    78.4  2725.1    86.4 2722.68
   106.4 2720.12   166.5 2716.73   278.5 2706.48   294.9 2702.08   325.6  2699.4
   358.7 2692.49   370.9 2686.44     387 2675.66     391 2673.54   394.5 2673.16
   528.5 2673.23   551.2 2675.56   565.3 2677.37   576.6 2682.67   581.6 2683.92
   603.4 2684.35     634 2705.39   696.8 2730.65     721 2741.61   730.7 2743.89
     837 2788.69   846.5 2791.12   853.3 2795.53   870.9 2802.33   942.6 2837.08
#Mann= 7 ,-1,0
       0     .05       0      20     .07       0     110     .06       0
  314.95      .1       0  364.95    .025       0     387    .035       0
   551.2      .1       0
Bank Sta=387,551.2
XS Rating Curve= 0 ,0
Exp/Cntr(USF)=0,0
Exp/Cntr=0.3,0.1

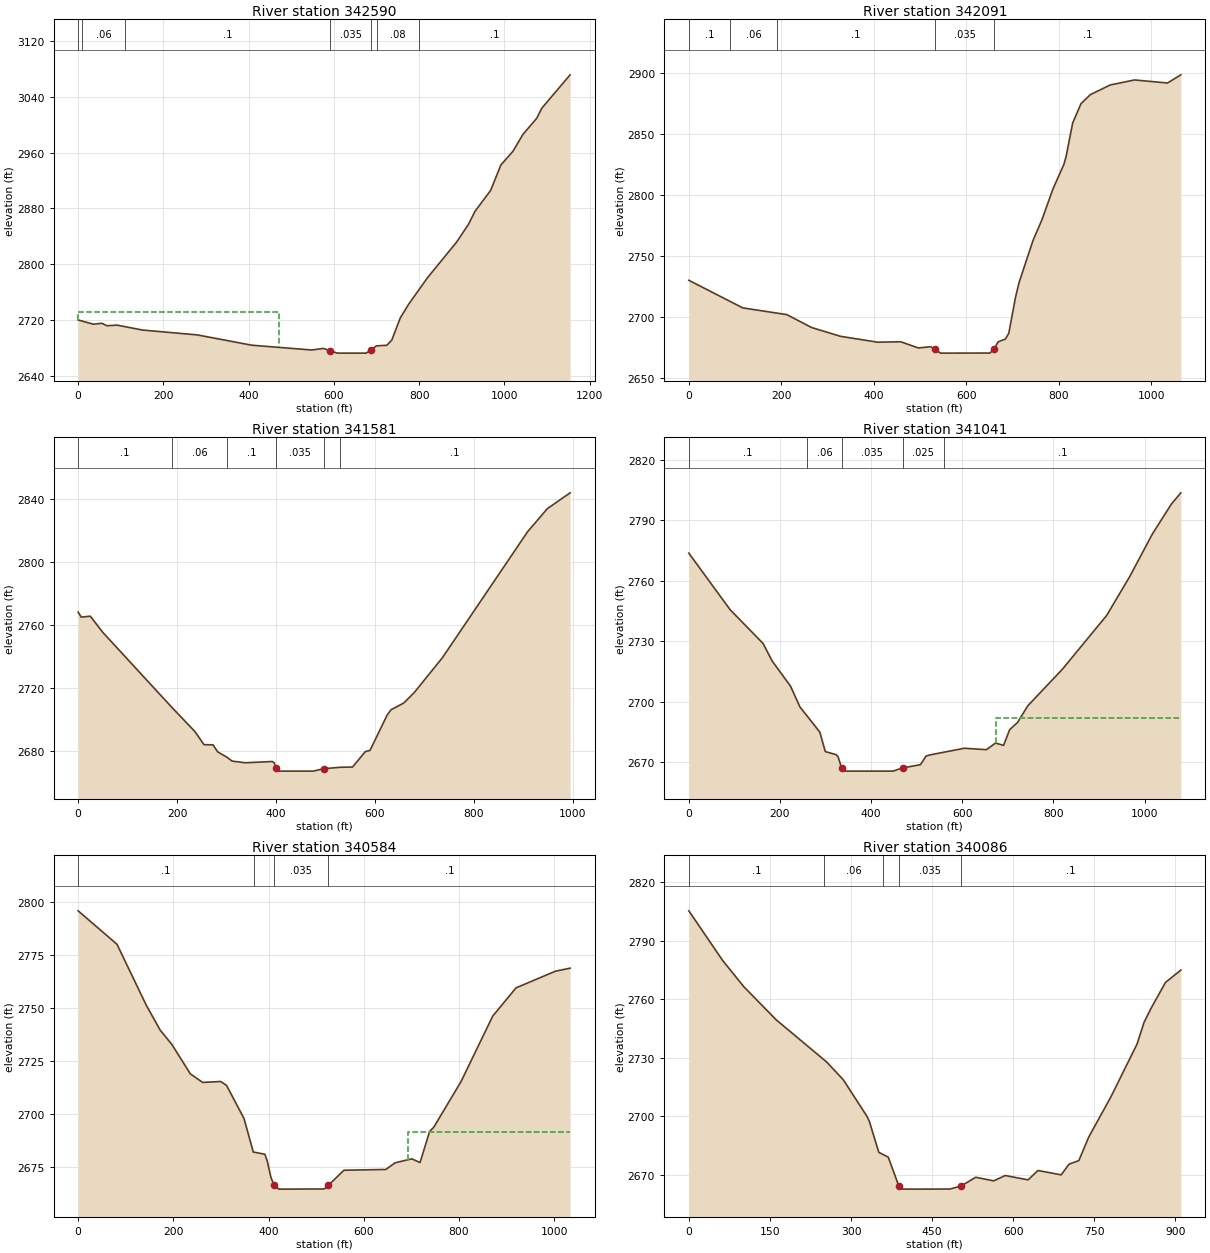
Type RM Length L Ch R = 1 ,342590  ,454.1,499.4,537.4
XS GIS Cut Line= 2
2300351.67948496558763.2278716872299197.86843297558791.422502656
#Sta/Elev= 30
       0 2720.04    35.5 2713.94    55.5 2715.21    67.5 2711.73    91.5 2712.58
   151.5 2705.51   279.6 2698.57   407.6 2683.78   547.7 2676.95   575.7 2679.19
   591.7  2675.8   607.7 2672.44   675.7 2672.44   687.7    2677   699.7 2682.88
     724 2683.66   735.7 2690.92   755.7 2722.85   775.7 2742.83   819.7 2780.67
   887.8  2831.6   915.8  2857.2     931 2875.75   967.8 2905.87   991.8 2942.28
  1019.8  2961.7  1043.8 2986.33  1075.8 3009.22  1087.8 3023.72  1154.2 3071.59
#Mann= 7 ,-1,0
       0      .1       0      10     .06       0     110      .1       0
   591.7    .035       0   687.7      .1       0     700     .08       0
     800      .1       0
#XS Ineff= 2 , 0
          470.91 2731.71
Permanent Ineff=
       F       F
Bank Sta=591.7,687.7
XS Rating Curve= 0 ,0
Exp/Cntr(USF)=0,0
Exp/Cntr=0.3,0.1

Type RM Length L Ch R = 1 ,342091  ,510.3,510,507.1
XS GIS Cut Line= 3
2300424.49078582558547.664728932 2300087.0837174558455.255748787
     2299488.031       558066.85
#Sta/Elev= 30
       0 2729.92   116.5 2707.29   211.8 2701.74   265.3 2691.17   327.8 2683.94
   408.4 2679.08   458.2 2679.45   496.3 2674.37   522.8 2675.39   532.7 2673.15
     544 2670.13   651.3  2670.2     660 2673.55   668.7 2679.38   684.5 2681.71
   691.8 2686.41   706.3 2715.84   713.9 2727.91   744.2 2762.62   763.3 2779.41
   787.2 2804.77   810.9    2825   815.7 2831.45     830  2859.1     848 2874.95
   868.3 2882.36   911.1 2890.26   963.7 2894.39    1035 2891.89  1063.8  2898.6
#Mann= 5 ,-1,0
       0      .1       0      90     .06       0     190      .1       0
   532.7    .035       0     660      .1       0
Bank Sta=532.7,660
XS Rating Curve= 0 ,0
Exp/Cntr=0.3,0.1

Type RM Length L Ch R = 1 ,341581  ,583.6,539.9,484.2
XS GIS Cut Line= 3
      2300601.64      558160.0512300069.73317526557858.830862888
2299686.13738729 557865.60906145
#Sta/Elev= 30
       0 2768.38     6.3 2765.22    24.7 2765.79    50.1 2755.42   190.2 2707.58
   236.1 2692.45   254.5 2684.09   272.9 2683.97   282.1 2679.54   300.5 2676.18
   311.3 2673.64   337.8 2672.58   392.4 2673.37   396.5 2672.61  400.38 2669.01
   406.2 2667.27   475.7 2667.26   496.2 2668.79   530.3 2669.72   554.9 2669.86
   580.9 2679.72   590.2 2680.41   624.8 2702.84   632.8  2706.3   658.4 2710.54
   679.7 2717.21   736.9  2739.5   908.9 2819.49   948.9 2834.18   994.9 2844.24
#Mann= 6 ,-1,0
       0      .1       0   190.2     .06       0   300.5      .1       0
  400.38    .035       0   496.2    .025       0   530.3      .1       0
Bank Sta=400.38,496.2
XS Rating Curve= 0 ,0
Exp/Cntr=0.3,0.1

Type RM Length L Ch R = 1 ,341041  ,493.6,457,403.3
XS GIS Cut Line= 3
2300798.45594494557407.716767373 2300126.1224372557468.443664846
2299761.76105236557644.117903965
#Sta/Elev= 30
       0  2773.7    90.6 2745.63   162.9 2728.88     183 2720.11   223.2 2707.68
   243.7 2697.41   287.4 2684.92   299.5 2675.22   323.6 2673.69   327.6 2672.56
     335  2667.3   339.7 2665.54   448.1 2665.53   468.9 2667.12   508.3 2668.73
   520.4 2672.97   528.4 2673.55   604.7 2676.88   652.9 2676.17     673 2679.46
   690.6  2678.3     704 2686.09   721.6 2689.75   743.8 2697.96   819.3 2715.98
   916.8 2742.75   967.7 2762.16  1017.5 2783.33  1059.1  2798.1  1079.6 2803.63
#Mann= 5 ,-1,0
       0      .1       0     260     .06       0     335    .035       0
   468.9    .025       0     560      .1       0
#XS Ineff= 2 , 0
                          674.94         2691.66
Permanent Ineff=
       F       F
Bank Sta=335,468.9
XS Rating Curve= 0 ,0
Exp/Cntr(USF)=0,0
Exp/Cntr=0.3,0.1

Type RM Length L Ch R = 1 ,340584  ,485.1,498.1,514.3
XS GIS Cut Line= 2
     2300565.541      556790.3682299719.07156496557382.997168541
#Sta/Elev= 30
       0 2795.89    81.6 2780.11   143.3 2751.26   172.3  2739.6     197 2732.78
   235.6 2718.96   261.5  2714.9   299.5 2715.34   311.8 2713.48   348.4 2697.85
   367.9 2682.05   392.3 2680.98   397.2 2677.81   405.1 2669.94   411.8 2666.31
   421.6 2664.53   517.1  2664.6   525.7 2666.36   558.3 2673.45   646.2 2673.81
   665.7 2676.95   700.9 2678.83   718.1 2677.06   738.3 2691.79   746.9 2693.74
   804.3 2715.33   870.8 2746.21   919.7 2759.52  1002.2 2767.37  1033.3 2768.83
#Mann= 4 ,-1,0
       0      .1       0     370     .06       0   411.8    .035       0
   525.7      .1       0
#XS Ineff= 2 , 0
                          692.28         2691.66
Permanent Ineff=
       F       F
Bank Sta=411.8,525.7
XS Rating Curve= 0 ,0
Exp/Cntr=0.3,0.1

Type RM Length L Ch R = 1 ,340086  ,514.1,492.9,475.4
XS GIS Cut Line= 2
     2300372.946      556428.713     2299542.241      556800.428
#Sta/Elev= 30
       0 2805.42    62.2 2780.05   101.6 2766.49   161.4 2749.51     255 2727.79
   285.7  2718.7   329.5 2699.92     334 2697.26   351.4 2681.41   368.9 2678.96
   388.5 2664.07   394.5 2662.56   412.8 2662.53   482.9 2662.57   503.5  2664.1
   530.7 2668.62     564 2666.77   585.2 2669.52   627.6 2667.28   645.8 2672.09
   688.8 2669.86   703.3 2675.35   721.5 2677.18   739.6 2689.18   780.9 2709.98
   829.1 2736.99   842.2 2748.24   855.4 2755.55   881.7 2768.65   910.1 2774.99
#Mann= 5 ,-1,0
       0      .1       0     250     .06       0     360      .1       0
   388.5    .035       0   503.5      .1       0
Bank Sta=388.5,503.5
XS Rating Curve= 0 ,0
Exp/Cntr=0.3,0.1

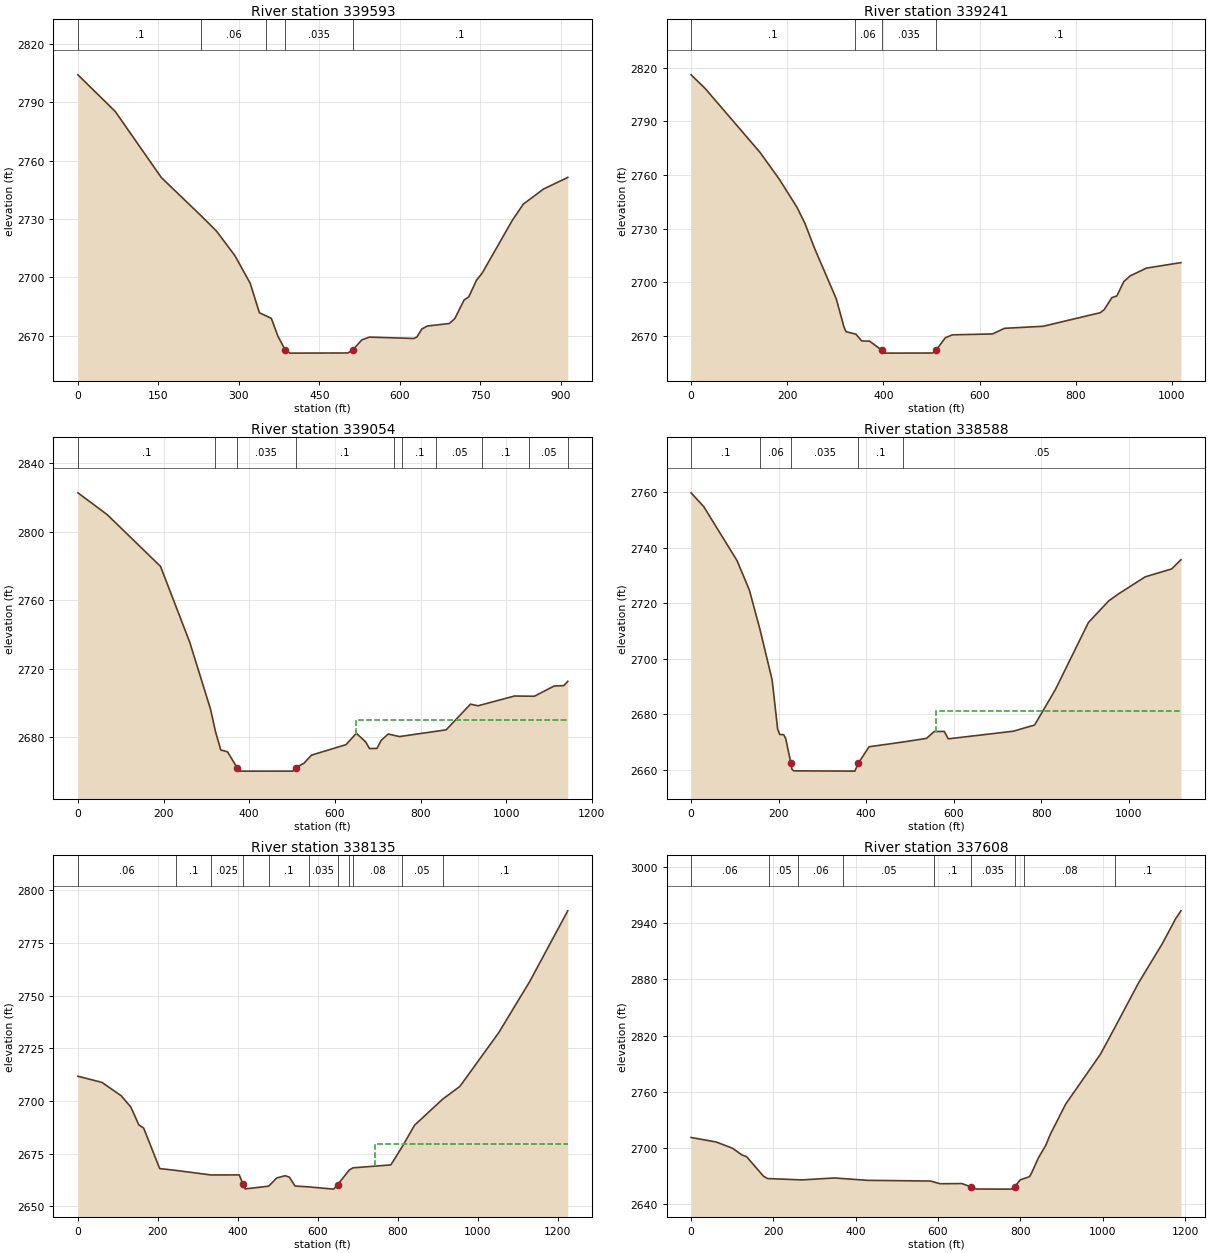
Type RM Length L Ch R = 1 ,339593  ,312.5,352.6,379.3
XS GIS Cut Line= 2
     2300026.685      555936.608     2299311.246      556503.265
#Sta/Elev= 30
       0 2804.05    69.5 2785.26   155.5 2751.29     230 2731.56   258.5 2723.72
   292.6 2711.18   321.1 2696.97   338.2 2681.87   360.4 2679.02   372.4 2670.03
   385.9 2662.92   395.1 2661.16   503.3 2661.25   511.9  2662.8   529.2 2667.98
   543.2 2669.39   625.7 2668.68   631.5 2669.41     641 2673.58   651.2 2675.08
   692.1 2676.36   702.3 2678.93   719.7 2688.49   728.3 2690.05   742.5 2698.51
   753.3 2702.28   809.4 2729.34   829.8 2737.63   867.8 2745.46   912.7 2751.36
#Mann= 5 ,-1,0
       0      .1       0     230     .06       0     350     .08       0
   385.9    .035       0   511.9      .1       0
Bank Sta=385.9,511.9
XS Rating Curve= 0 ,0
Exp/Cntr=0.3,0.1

Type RM Length L Ch R = 1 ,339241  ,177.1,186.7,195
XS GIS Cut Line= 5
2299984.29459723 555808.846705152299595.71034398  555886.5635558
  2299479.135068555913.9930325012299218.55503935556078.569892701
2299111.12292228556240.860963176
#Sta/Elev= 30
       0 2816.07    28.7 2808.63   143.2 2772.79   183.7 2757.66   220.4 2741.99
   236.7 2733.12   257.1 2718.93     302 2690.86   318.3 2674.88   322.4 2672.49
   342.8 2671.11     355 2667.29   371.3 2667.19   396.5 2662.21     404  2660.5
   502.6 2660.56     5102662.237     529 2669.14   543.7 2670.72   626.9 2671.22
     652 2674.37   732.2  2675.5   851.4 2683.12   859.6  2684.9   875.3 2691.54
   885.6 2692.46     900 2700.47   913.7 2703.73   947.3 2708.03  1018.9 2711.09
#Mann= 4 ,-1,0
       0      .1       0     340     .06       0   396.5    .035       0
     510      .1       0
Bank Sta=396.5,510
XS Rating Curve= 0 ,0
Exp/Cntr(USF)=0,0
Exp/Cntr=0.3,0.1

Type RM Length L Ch R = 1 ,339054  ,519.2,465.8,444.4
XS GIS Cut Line= 4
2299968.29406915555673.9851113752299463.13453993555719.700905875
2299072.26449695 555891.13513525 2298875.6865806 555817.98986405
#Sta/Elev= 30
       0 2822.85    68.4 2810.11   192.9 2779.87   260.9 2735.73   309.4 2696.69
   321.4 2683.23   333.5 2672.63   349.5 2671.49     372 2662.14   377.7 2660.25
   502.2 2660.25   508.1 2662.16   527.9 2664.89   545.4  2669.6     626 2675.73
   650.2 2682.35   672.1 2677.29   680.8 2673.44   698.3 2673.53   707.9 2678.15
   724.5 2681.95   750.7 2680.44   859.8 2684.37   916.7 2699.38     934 2698.42
  1019.5 2704.14  1065.8 2703.99  1111.7 2709.94  1134.7 2710.23  1143.8  2712.7
#Mann= 10 ,-1,0
       0      .1       0     320     .07       0     372    .035       0
   508.1      .1       0  737.22     .05       0  757.22      .1       0
  837.22     .05       0  944.04      .1       0 1054.04     .05       0
 1143.78     .06       0
#XS Ineff= 2 , 0
                          649.01         2690.08
Permanent Ineff=
       F       F
Bank Sta=372,508.1
XS Rating Curve= 0 ,0
Exp/Cntr(USF)=0,0
Exp/Cntr=0.3,0.1

Type RM Length L Ch R = 1 ,338588  ,475.1,453,447.7
BEGIN DESCRIPTION:
c/e of 0.5/0.7 used to correct drawdown
END DESCRIPTION:
XS GIS Cut Line= 3
2299701.04810253555186.2052436832299508.00937363555197.691462899
2298709.92996137555666.464514751
#Sta/Elev= 30
       0 2759.83    28.9 2754.86   105.1 2735.36   133.1 2724.78   157.2 2710.67
   185.2 2692.32   197.8 2674.59   202.5 2672.68   211.7 2672.57   216.3 2671.13
   228.1 2662.26   230.3 2660.14   234.9 2659.54   374.1 2659.44     3822662.283
   406.6 2668.23   484.6 2669.96   537.7 2671.24   555.3 2673.71   578.2 2673.77
   587.5 2671.09   735.9 2673.83   784.7 2676.07   832.1 2688.83   907.6 2713.04
     954 2720.85   977.2 2723.46  1037.4 2729.53  1097.8 2732.38  1118.9  2735.7
#Mann= 5 ,-1,0
       0      .1       0   157.2     .06       0   228.1    .035       0
     382      .1       0   484.6     .05       0
#XS Ineff= 2 , 0
                           559.1         2681.01
Permanent Ineff=
       F       F
Bank Sta=228.1,382
XS Rating Curve= 0 ,0
Exp/Cntr=0.7,0.5

Type RM Length L Ch R = 1 ,338135  ,401.6,527.3,595
XS GIS Cut Line= 4
2299688.32769242554733.5260751422299321.49104568554757.421456218
2298952.79202531 555022.017223782298553.76630302555085.000093399
#Sta/Elev= 30
       0 2711.78    60.3 2708.84   108.4 2702.49   132.4 2697.13   152.5 2688.68
   164.5 2687.17   204.6 2667.95   244.7 2667.09   332.9 2664.91   403.7 2664.94
  413.07 2660.41   418.5  2658.3   477.3  2659.6   497.5 2663.49   518.1 2664.55
   528.9 2663.92   543.2 2659.67   577.6 2659.25     640 2658.19   649.9 2660.38
   679.4 2667.35   688.3  2668.3   782.8 2669.69   810.3 2678.02   842.2 2688.54
   912.2 2700.85   955.7 2706.99  1052.9  2732.5  1129.8 2756.58  1225.4 2790.29
#Mann= 11 ,-1,0
       0     .06       0   244.7      .1       0   332.9    .025       0
  413.07    .035       0   477.3      .1       0   577.6    .035       0
   649.9     .08       0   679.4      .1       0   688.3     .08       0
   810.3     .05       0   912.2      .1       0
#XS Ineff= 2 , 0
                          744.24         2679.64
Permanent Ineff=
       F       F
Bank Sta=413.07,649.9
XS Rating Curve= 0 ,0
Exp/Cntr=0.3,0.1

Type RM Length L Ch R = 1 ,337608  ,268.1,275.6,282.9
XS GIS Cut Line= 2
2299691.38505232554717.862505623     2298615.272      554209.313
#Sta/Elev= 30
       0 2710.84    61.1 2706.05   100.9  2699.3   123.1 2692.28   135.1 2690.22
   176.1 2669.37   186.2  2666.9     269 2665.47   348.6 2667.53   429.5    2665
     582 2664.24   605.2 2661.36   657.9 2661.56   680.4 2657.98   693.7 2655.69
   777.8 2655.59   786.6 2658.39   799.9 2665.54     822 2668.87   825.4 2670.99
   844.1 2689.19   862.2 2702.75   872.2 2713.63   910.2 2746.61   994.6 2799.91
    1030 2828.83  1087.5  2876.5    1145 2918.29  1177.6 2945.16  1190.2 2953.44
#Mann= 9 ,-1,0
       0     .06       0     190     .05       0     260     .06       0
     370     .05       0     590      .1       0   680.4    .035       0
   786.6      .1       0     810     .08       0    1030      .1       0
Bank Sta=680.4,786.6
XS Rating Curve= 0 ,0
Exp/Cntr=0.3,0.1