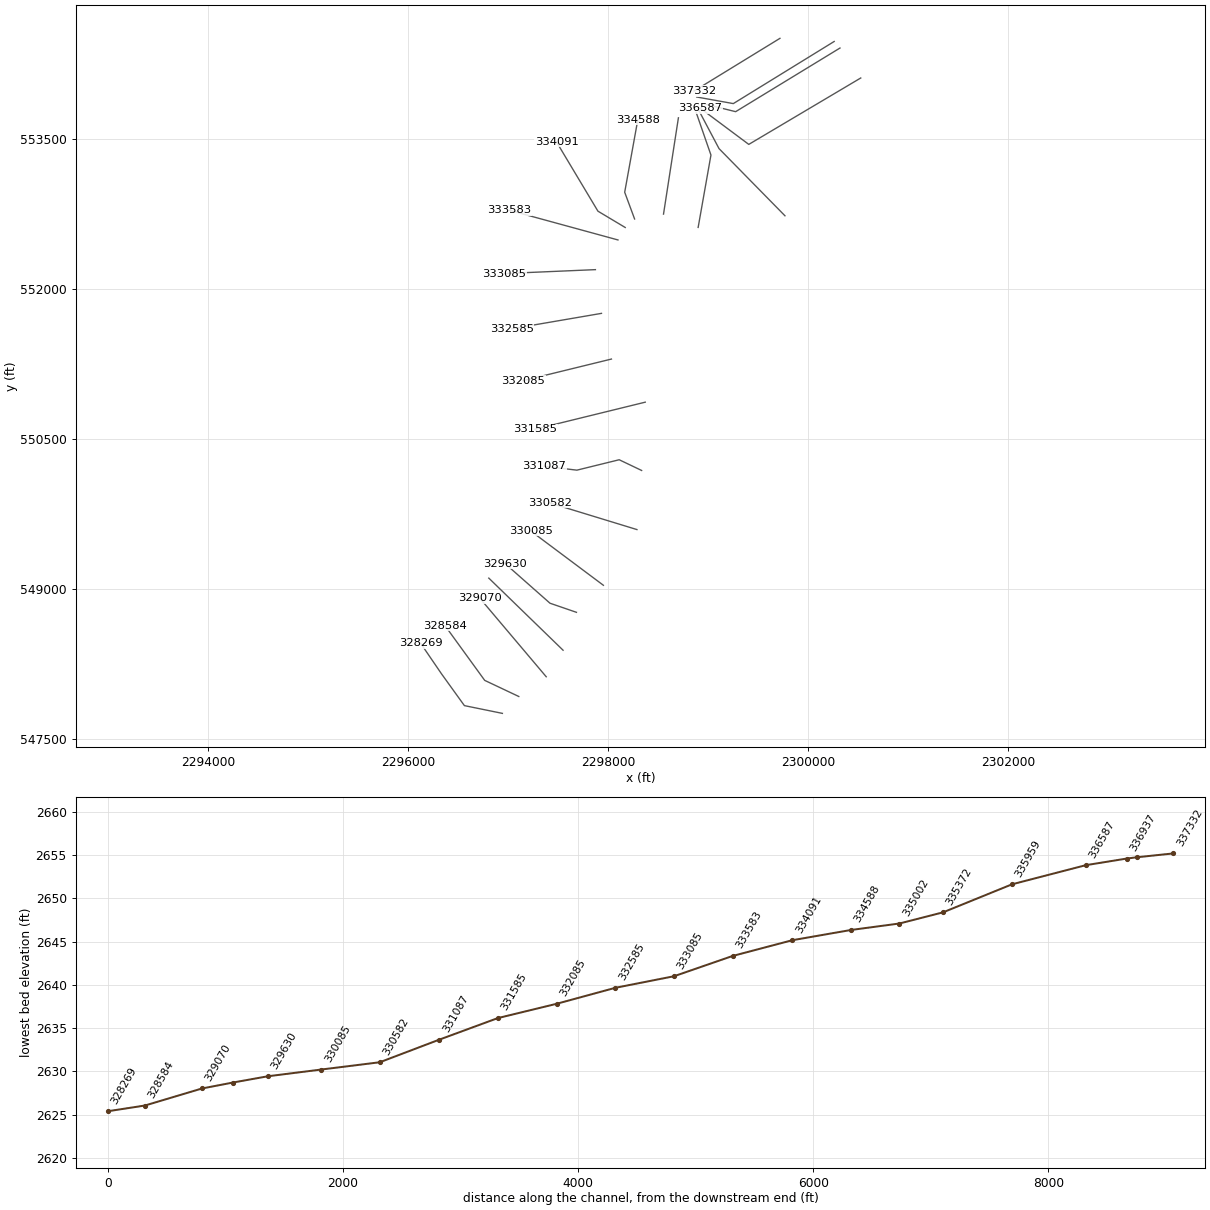
HEC-RAS study GRNBRRRV.prj: GRNBRRRV

--- GRNBRRRV.g01 (geometry) --- (continued)

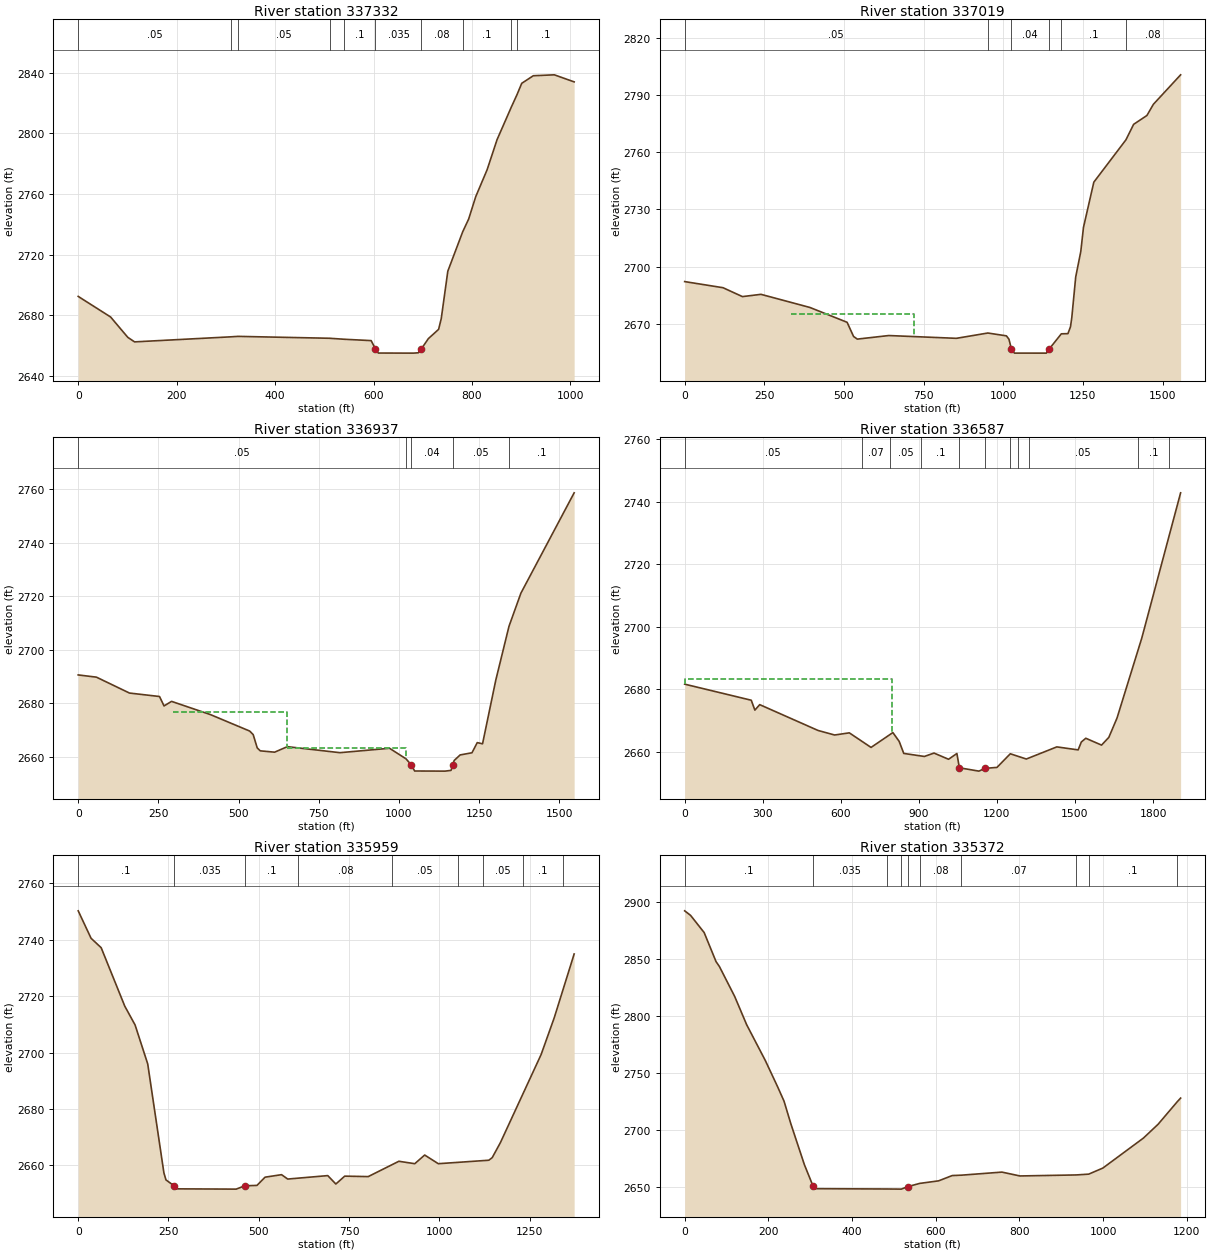
Type RM Length L Ch R = 1 ,337332  ,313.3,313.1,312.8
BEGIN DESCRIPTION:
structure xs 4
END DESCRIPTION:
XS GIS Cut Line= 2
2299720.30706124 554507.610869682298861.45522555553980.588152321
#Sta/Elev= 30
       0 2692.56    65.8    2679   100.7 2665.61   114.5  2662.6   310.2 2665.93
   324.7 2666.23   510.8 2664.98     540 2664.34   595.2 2663.43   603.9 2658.07
   609.7 2655.24   680.6 2655.19   691.1 2655.41   697.5  2658.1   711.5 2664.75
   732.3 2670.86   737.7    2678     751 2709.17   781.3 2735.18   793.3  2743.5
   807.7 2758.27   830.8 2775.96   851.1 2795.87   880.2 2817.41   891.8 2825.64
   891.8 2825.66   901.2 2832.96   924.7 2837.95   967.4 2838.55  1007.7  2833.9
#Mann= 10 ,-1,0
       0     .05       0   310.2     .06       0   324.7     .05       0
   510.8     .08       0     540      .1       0   603.9    .035       0
   697.5     .08       0   781.3      .1       0   880.2     .08       0
   891.8      .1       0
Bank Sta=603.9,697.5
XS Rating Curve= 0 ,0
Exp/Cntr(USF)=0,0
Exp/Cntr=0.5,0.3

Type RM Length L Ch R = 1 ,337019  ,81.9,81.7,81.6
BEGIN DESCRIPTION:
structure xs 3
c/e of 0.5/0.7 used to correct drawdown in the 500yr that was greater than 0.5'
END DESCRIPTION:
XS GIS Cut Line= 3
2300262.57180397554476.2361624872299254.04081313553854.542619856
2298888.08263553553920.424608149
#Sta/Elev= 30
       0  2692.2   120.3    2689   181.3 2684.34   239.4 2685.53   392.8 2678.67
   509.8 2670.89   530.1 2663.47   541.8 2662.08   640.6 2663.95   852.8 2662.49
   951.6 2665.27  1009.8 2663.78  1017.8 2662.031025.5922656.859  1034.9 2654.75
  1135.3 2654.741143.3872656.742  1182.2 2664.85  1202.9 2664.94    1211 2668.57
  1215.1 2673.42  1227.3 2694.59  1243.3 2707.99  1251.7 2720.59  1284.2 2744.28
    1385 2766.45  1409.1 2774.55  1450.8 2779.19  1471.1 2785.05  1556.6 2800.49
#Mann= 6 ,-1,0
       0     .05       0   951.6      .1       01025.592     .04       0
1143.387     .08       0  1182.2      .1       0    1385     .08       0
#XS Ineff= 3 ,-1
  332.42     720 2675.14     720    1000 2663.29    1168  1556.6 2660.06
Permanent Ineff=
       F       F       F
Bank Sta=1025.592,1143.387
XS Rating Curve= 0 ,0
Exp/Cntr=0.7,0.5

Type RM Length L Ch R = 1 ,336937  ,351.5,350.7,351.5
BEGIN DESCRIPTION:
structure xs 2
END DESCRIPTION:
XS GIS Cut Line= 3
2300320.54926362554410.6658778552299277.21759146553773.682937357
2298962.95589704553851.760376966
#Sta/Elev= 30
       0 2690.58    56.7 2689.75   159.8  2683.8   253.5 2682.51   267.6 2678.98
     291 2680.69   411.7 2675.77   534.7 2669.58   545.5 2668.27   558.1  2663.3
   567.5 2662.19   612.4 2661.69   651.9 2663.75   816.1  2661.5   970.6 2663.15
  1022.1 2659.19 1038.45 2656.92  1048.9 2654.65    1144  2654.6  1162.4 2654.88
  1167.4 2656.83  1172.1 2658.57  1190.8 2660.66  1227.6 2661.46  1244.1 2665.26
  1260.6 2664.82  1301.8 2688.59    1343 2708.74  1380.1 2721.14  1546.2 2758.69
#Mann= 5 ,-1,0
       0     .05       0  1022.1      .1       0 1038.45     .04       0
  1167.4     .05       0    1343      .1       0
#XS Ineff= 3 ,-1
  295.66     650 2676.63     650 1020.79 2663.32    1185  1546.2    2660
Permanent Ineff=
       F       F       F
Bank Sta=1038.45,1167.4
XS Rating Curve= 0 ,0
Exp/Cntr(USF)=0,0
Exp/Cntr=0.5,0.3

Type RM Length L Ch R = 1 ,336587  ,732.8,627.5,483.7
XS GIS Cut Line= 3
 2300528.2022245554110.8672647652299408.71239641553446.223382722
2298924.59739434553807.479274315
#Sta/Elev= 30
       0 2681.64   255.9  2676.5   269.8 2673.34   288.4 2675.09   512.6 2666.83
   576.3 2665.38   632.7 2666.07   716.3 2661.41   800.2 2666.16   824.4 2663.34
     842 2659.49   921.1 2658.52   958.3  2659.6  1014.1 2657.62  1046.2 2659.47
1055.6972654.896  1130.9 2653.831153.8942654.714  1200.2 2655.02  1251.4 2659.38
    1313  2657.7  1430.2 2661.58  1512.2 2660.62  1524.5 2663.15  1541.6 2664.34
  1602.1 2662.15  1630.2 2664.64  1661.7 2670.83  1756.8 2696.39    1906 2742.82
#Mann= 11 ,-1,0
       0     .05       0     680     .07       0     790     .05       0
     910      .1       01055.697    .035       01153.894     .08       0
    1250     .05       0    1280      .1       0 1321.93     .05       0
 1741.93      .1       0 1861.93     .08       0
#XS Ineff= 2 , 0
          796.62 2683.27
Permanent Ineff=
       F       F
Bank Sta=1055.697,1153.894
XS Rating Curve= 0 ,0
Exp/Cntr=0.3,0.1

Type RM Length L Ch R = 1 ,335959  ,670.2,586.9,445
XS GIS Cut Line= 3
2299770.43632343552731.7456619312299111.11572229553404.079169671
2298909.41566997553785.791096646
#Sta/Elev= 30
       0 2750.23    35.6  2740.5    63.6 2737.16   128.9 2716.47   157.5 2709.79
   192.5 2695.98   237.3 2657.38     243 2654.89   265.7 2652.78   271.3 2651.72
   437.4 2651.62   461.4  2652.8     495 2652.94   517.4 2655.85   563.1 2656.74
   580.2 2655.19   691.1 2656.41   713.5 2653.43     738 2656.22   803.1 2656.06
     888 2661.49     932 2660.63   959.5  2663.7   997.2 2660.63  1137.1 2661.86
  1146.5 2662.78  1169.1 2668.08  1281.9  2699.3  1318.4 2712.39  1373.4 2734.94
#Mann= 9 ,-1,0
       0      .1       0   265.7    .035       0   461.4      .1       0
     610     .08       0     870     .05       0 1051.67     .07       0
 1121.67     .05       0 1231.67      .1       0 1341.67     .08       0
Bank Sta=265.7,461.4
XS Rating Curve= 0 ,0
Exp/Cntr(USF)=0,0
Exp/Cntr=0.3,0.1

Type RM Length L Ch R = 1 ,335372  ,371.2,370.9,386
XS GIS Cut Line= 3
2298902.44717233552615.3194192322299030.40742058553339.704553378
2298883.08026194553764.720403096
#Sta/Elev= 30
       0 2891.86    14.1 2887.88    46.6 2872.82      75 2847.41    83.1 2843.09
   119.7 2816.82   148.1 2792.27   192.8 2760.86   222.2 2737.88   237.5 2725.33
   253.7 2705.63   286.2 2669.71   306.9 2650.99   314.7 2648.76   482.7  2648.5
   517.8 2648.38     534 2650.64   561.8 2653.39     607 2655.63   639.6 2660.26
   661.2 2660.58   758.3 2663.27   801.4  2659.9   936.1 2660.79   965.8  2661.5
   999.6 2666.82  1096.6 2693.07  1131.5  2705.1  1177.4 2724.86  1185.4 2728.02
#Mann= 10 ,-1,0
       0      .1       0   306.9    .035       0   482.7      .1       0
   517.8    .035       0     534     .07       0   561.8     .08       0
   661.2     .07       0   936.1     .05       0   965.8      .1       0
  1177.4     .08       0
Bank Sta=306.9,534
XS Rating Curve= 0 ,0
Exp/Cntr=0.3,0.1

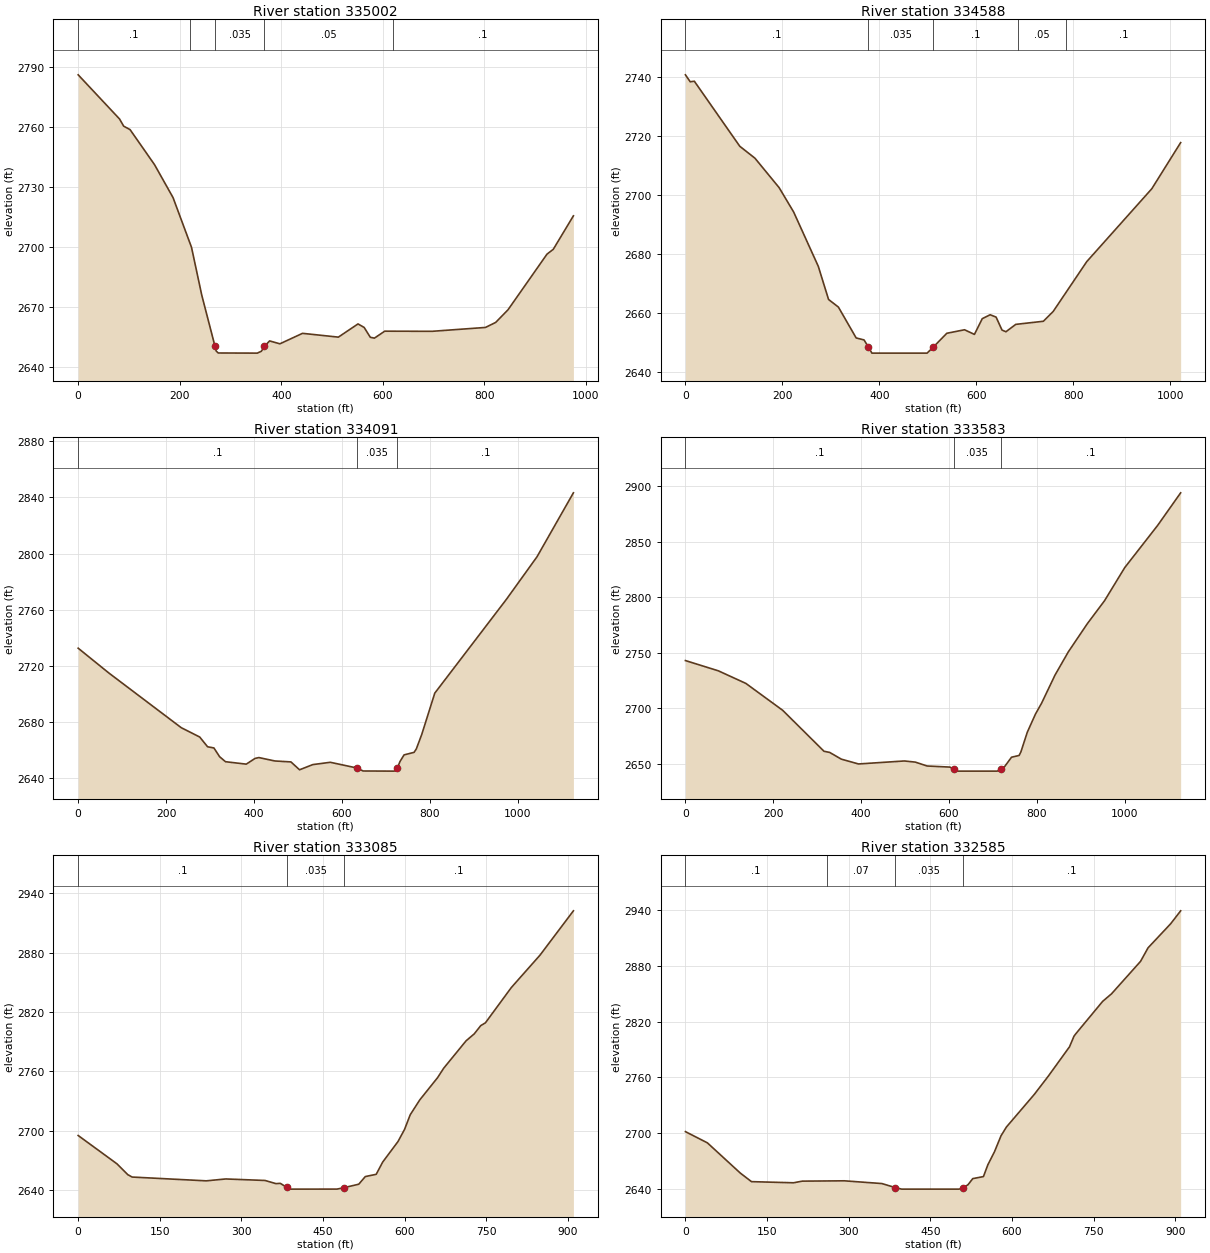
Type RM Length L Ch R = 1 ,335002  ,415.9,413.2,411.1
XS GIS Cut Line= 2
 2298556.1532802552748.587514751 2298705.1104533 553712.42277669
#Sta/Elev= 30
       0 2785.94    81.5  2763.9    89.6 2760.33   102.2  2758.6   150.4 2741.11
   186.8 2724.71   223.2 2699.89   243.4    2676  269.44 2650.52   271.8 2648.14
   275.8 2647.16   352.7 2647.09   360.8 2648.03   366.8 2650.47     377 2653.18
   397.3 2651.74   441.8 2656.96   512.4 2655.07   551.1 2661.66   563.2 2659.91
   575.3    2655   583.4 2654.57   603.7 2658.04   696.8 2657.97     802  2659.9
   822.2  2662.4   846.5 2668.71   923.4 2696.51   935.6 2698.87   975.3 2715.58
#Mann= 5 ,-1,0
       0      .1       0     220    .025       0  269.44    .035       0
   366.8     .05       0     620      .1       0
Bank Sta=269.44,366.8
XS Rating Curve= 0 ,0
Exp/Cntr=0.3,0.1

Type RM Length L Ch R = 1 ,334588  ,444,497.6,548.7
XS GIS Cut Line= 3
2298266.98356663552699.903312141 2298168.0191868552967.247667482
 2298298.9253599553691.773341646
#Sta/Elev= 30
       0 2740.69     9.9 2738.33    18.4 2738.52   112.1 2716.47   143.3 2712.44
   193.3 2702.43   223.2 2694.18     274 2675.78   295.2 2664.53   315.5 2661.95
   352.1 2651.49   368.3 2650.82  377.28 2648.43   384.6 2646.34   498.4 2646.34
   510.9 2648.35   539.1 2653.07   575.6 2654.26     596 2652.69   612.2 2658.03
   628.5 2659.35   640.7 2658.55   652.9 2654.16     661 2653.59   681.3 2656.09
   738.2 2657.14   758.4 2660.46   827.6 2677.35   961.8 2702.07  1021.3 2717.71
#Mann= 5 ,-1,0
       0      .1       0  377.28    .035       0   510.9      .1       0
  685.07     .05       0  785.07      .1       0
Bank Sta=377.28,510.9
XS Rating Curve= 0 ,0
Exp/Cntr=0.3,0.1

Type RM Length L Ch R = 1 ,334091  ,453.4,508.1,558.4
XS GIS Cut Line= 3
2298173.32305232552614.6800091282297900.45336403 552777.98075175
     2297485.747      553471.788
#Sta/Elev= 30
       0 2732.65    69.7 2715.01   234.4 2676.08   276.4 2669.44   294.3  2662.5
   308.7 2661.65   321.7  2655.4   335.1 2651.86   382.3 2650.13   402.2  2654.2
     411 2654.81   447.5 2652.38   483.9 2651.71   503.5 2646.11   533.5  2649.8
   573.4 2651.45     634 2647.39   647.9 2645.26   717.8 2645.16   722.5 2645.49
     726 2647.49   731.8 2651.92   741.1 2656.71   763.9 2658.52   769.1 2660.99
   781.4 2671.28     811 2700.66   973.9 2767.42  1043.6 2797.75  1126.3 2843.23
#Mann= 3 ,0,0
       0      .1       0     634    .035       0     726      .1       0
Bank Sta=634,726
XS Rating Curve= 0 ,0
Exp/Cntr=0.3,0.1

Type RM Length L Ch R = 1 ,333583  ,471.1,497.6,516.8
XS GIS Cut Line= 2
2298100.91632339552489.896555827     2297013.488       552787.45
#Sta/Elev= 30
       0    2743    74.9 2733.76   137.6 2722.41   221.4 2698.17   315.5 2661.24
   328.4  2660.2   354.9 2654.14     394  2649.8   498.4 2652.49   523.3 2651.47
   550.3 2647.96   602.1 2646.97   610.4 2645.24   618.7 2643.34   709.9 2643.34
   718.2 2645.38   724.8 2646.43   742.4 2655.89   759.7 2657.46   763.8 2660.75
   778.2 2678.32     797 2694.86   810.8 2704.56   841.3 2729.85   871.6 2750.79
     915 2776.27   954.1 2796.92  1000.2 2826.84  1074.9 2864.76  1127.4 2894.19
#Mann= 3 ,-1,0
       0      .1       0   610.4    .035       0   718.2      .1       0
Bank Sta=610.4,718.2
XS Rating Curve= 0 ,0
Exp/Cntr=0.3,0.1

Type RM Length L Ch R = 1 ,333085  ,488.3,500,508
XS GIS Cut Line= 2
     2297875.299      552192.865     2296966.139      552153.767
#Sta/Elev= 30
       0 2695.21    71.2 2666.61    91.2  2655.6    99.2 2653.21   235.3 2649.37
   271.3 2651.28   343.4 2649.75   363.4 2646.55   371.5 2646.84   383.5 2642.69
   391.5    2641   475.6 2641.03   488.9 2642.53   515.6 2645.97   527.6  2653.7
   547.6 2655.96   559.6  2668.4   587.7 2689.12   599.7 2701.38   610.2 2716.23
   627.7  2731.2   660.4 2753.67   671.7 2763.26   712.8 2790.93   727.8 2797.97
   739.8 2806.31   748.3 2809.11   795.9 2844.76   848.7 2877.58     910 2922.33
#Mann= 3 ,-1,0
       0      .1       0   383.5    .035       0   488.9      .1       0
Bank Sta=383.5,488.9
XS Rating Curve= 0 ,0
Exp/Cntr=0.3,0.1

Type RM Length L Ch R = 1 ,332585  ,494.9,500,505.2
XS GIS Cut Line= 2
     2297935.848       551755.23     2297038.968      551601.264
#Sta/Elev= 30
       0 2701.56    40.3 2689.53   101.1 2656.82   121.4 2647.72   198.5 2646.49
   214.8 2648.26   291.9 2648.61   360.9 2645.67   385.2 2641.41   397.4 2639.66
   502.9 2639.66   510.7 2641.29   519.2 2644.37     528 2650.97   547.6 2653.16
   555.6  2665.7   567.9  2679.9     580  2697.2   589.9 2706.58   640.9 2741.55
   666.6 2761.16   705.8 2792.96     714 2804.37     718 2807.43   766.7 2841.88
     783    2850   836.3 2884.94   850.1 2899.51   891.7 2925.47     910 2939.36
#Mann= 4 ,-1,0
       0      .1       0     260     .07       0   385.2    .035       0
   510.7      .1       0
Bank Sta=385.2,510.7
XS Rating Curve= 0 ,0
Exp/Cntr=0.3,0.1

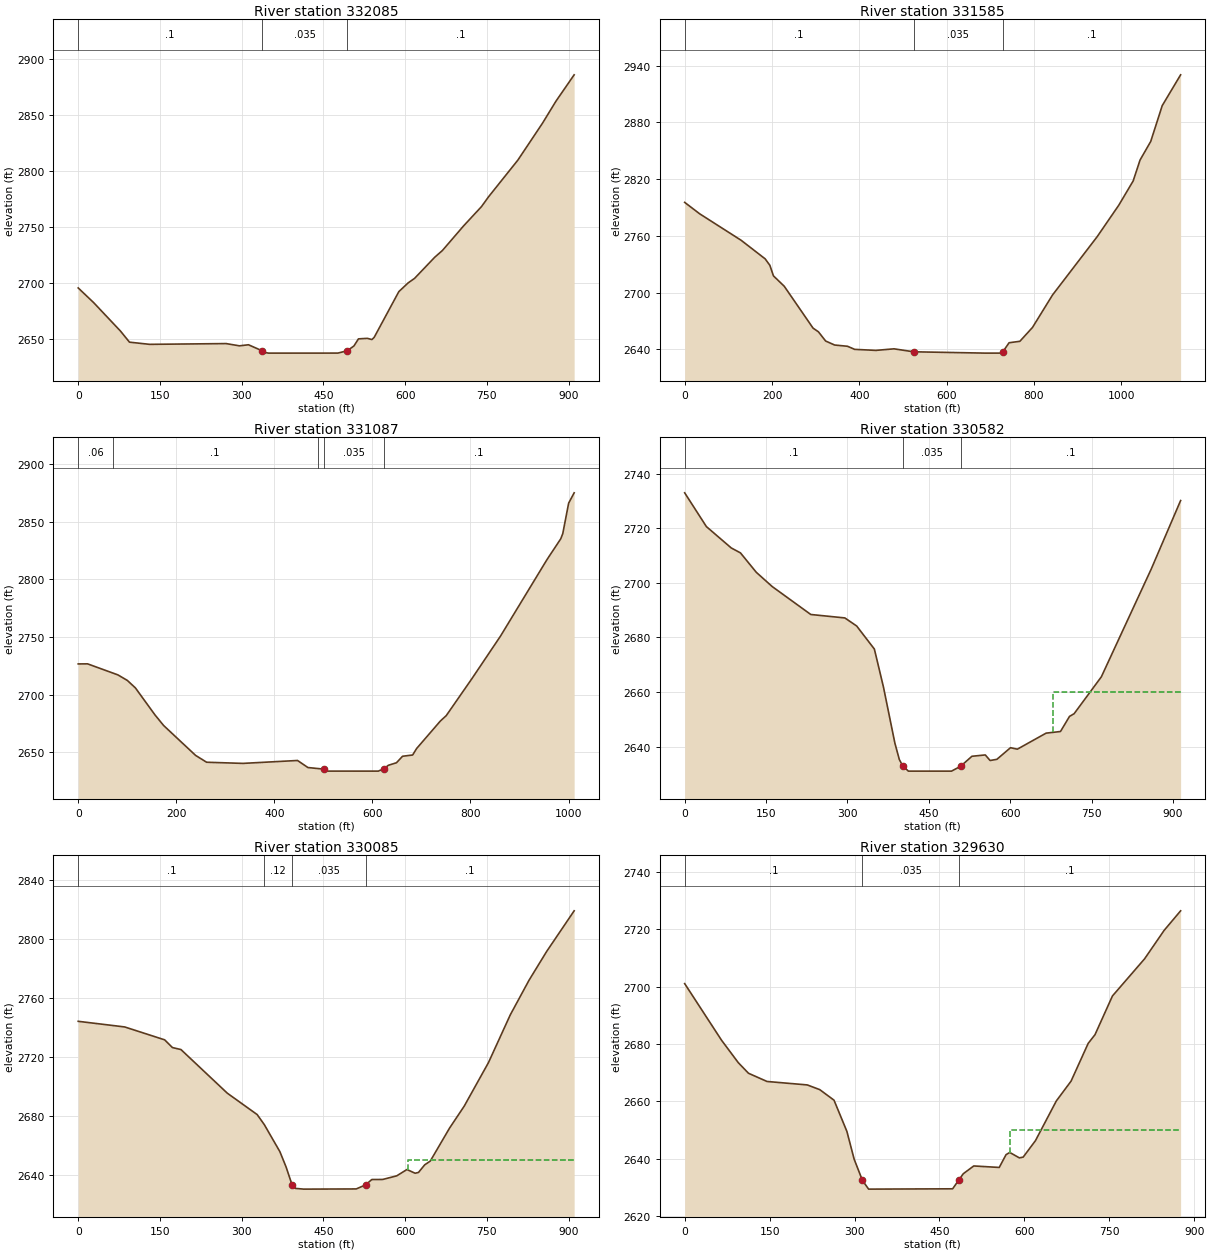
Type RM Length L Ch R = 1 ,332085  ,501.3,499.8,499.9
XS GIS Cut Line= 2
     2298035.543      551298.052     2297151.713      551081.386
#Sta/Elev= 30
       0 2695.87    28.2 2682.86    77.6 2657.44    94.1 2647.57   131.1 2645.63
   271.4 2646.31   295.9  2644.3   312.4 2645.26   337.1 2639.98   341.2 2638.47
   349.4 2637.81   476.5 2637.84   493.6 2639.93   505.9 2644.16   514.2 2650.51
   530.6 2650.97   538.9  2649.9     543  2651.8   588.3 2692.58   605.5 2700.42
   617.1 2704.35   654.2 2723.23   668.3 2729.24   707.2 2751.18     740 2768.34
     753  2777.1   806.6 2809.66   851.9  2842.6   876.7  2862.3     910 2885.71
#Mann= 3 ,0,0
       0      .1       0   337.1    .035       0   493.6      .1       0
Bank Sta=337.1,493.6
XS Rating Curve= 0 ,0
Exp/Cntr=0.3,0.1

Type RM Length L Ch R = 1 ,331585  ,513.7,497.8,499.3
XS GIS Cut Line= 2
2298373.64159446550866.651444173     2297270.761      550595.765
#Sta/Elev= 30
       0 2795.54    34.5 2783.41   129.2 2755.49   184.3 2735.83   195.1 2728.98
   203.3 2717.84     228 2706.86     294 2662.59   306.3 2658.69   322.8 2648.96
   343.4 2644.73   372.8 2643.42   389.3 2640.14   438.1 2639.05   479.3 2640.71
   524.1 2637.57   689.4 2636.16   726.4 2636.19  729.012637.813   742.9 2647.14
   767.6 2648.66   796.5 2663.32   842.3 2697.58   944.6 2759.26   994.2 2792.63
  1027.1 2818.24  1042.8  2840.3  1067.2  2859.9  1093.6 2897.83  1135.7 2930.39
#Mann= 3 ,-1,0
       0      .1       0   524.1    .035       0  729.01      .1       0
Bank Sta=524.1,729.01
XS Rating Curve= 0 ,0
Exp/Cntr=0.3,0.1

Type RM Length L Ch R = 1 ,331087  ,542.5,505.5,461.2
XS GIS Cut Line= 4
2298337.36516854550183.1176629182298112.99750518550290.346773111
2297690.07804064  550186.24352032297365.12445787550224.914523879
#Sta/Elev= 30
       0 2726.66    19.1 2726.73    81.1 2717.13   100.1 2712.38   116.6 2705.89
   156.5 2682.48   174.2 2673.25   239.4 2647.32   261.9 2641.38     336 2640.38
   447.3  2642.9   468.5 2636.79   501.6 2635.36     509 2633.69     612 2633.67
   623.9 2635.81   632.6 2638.74   649.1 2640.93   661.5 2646.57   682.1 2647.66
   690.2 2653.27   738.5 2677.07   750.6  2681.8     803 2713.91   861.4 2750.87
     956  2817.1   984.2 2835.21   988.3 2839.73  1000.3 2866.16  1011.5 2875.09
#Mann= 5 ,-1,0
       0     .06       0      70      .1       0  488.67     .07       0
   501.6    .035       0   623.9      .1       0
Bank Sta=501.6,623.9
XS Rating Curve= 0 ,0
Exp/Cntr=0.3,0.1

Type RM Length L Ch R = 1 ,330582  ,522.3,496.9,470.2
XS GIS Cut Line= 2
     2298290.427      549591.587     2297416.423       549859.07
#Sta/Elev= 30
       0 2732.97      40 2720.61      86 2712.76   102.8 2710.98     132 2703.86
   161.3 2698.65   232.4 2688.42   295.2 2687.16     317  2684.2   349.6 2675.76
   366.3 2661.89   387.4 2641.32   395.6  2635.3   401.8 2632.96   412.3 2631.06
   491.8 2631.06   508.5 2632.83   529.4  2636.5     554 2636.99   562.9 2634.95
   575.4 2635.38   600.5 2639.64   613.1  2639.1   666.1 2644.97   692.6 2645.57
   709.3 2651.11   717.7 2652.08   767.9 2665.59   859.9 2705.08     914 2730.14
#Mann= 3 ,0,0
       0      .1       0   401.8    .035       0   508.5      .1       0
#XS Ineff= 2 , 0
       0                   678.9       0    2660
Permanent Ineff=
       F       F
Bank Sta=401.8,508.5
XS Rating Curve= 0 ,0
Exp/Cntr=0.3,0.1

Type RM Length L Ch R = 1 ,330085  ,464.9,455.3,446
XS GIS Cut Line= 2
     2297955.103      549034.076     2297226.604      549579.411
#Sta/Elev= 30
       0    2744    85.3 2740.18   158.6 2731.44   172.9  2726.2   188.5 2724.86
   273.5  2695.3   328.4 2680.76   341.5 2673.93   370.1 2655.59   381.5 2645.17
   392.3 2633.24   398.6 2630.73   413.4 2630.22   510.1 2630.35   527.2 2633.06
   538.7 2636.72   558.7 2636.78   584.4 2639.22   603.2 2643.51   618.2    2641
   624.4 2641.54   635.8  2646.7     646 2649.24   681.5 2671.67   708.2 2686.43
   752.8 2716.02   792.8 2748.37   827.3  2771.9   859.6 2791.39     910 2818.91
#Mann= 4 ,-1,0
       0      .1       0   341.5     .12       0   392.3    .035       0
   527.2      .1       0
#XS Ineff= 2 , 0
       0                   604.4       0    2650
Permanent Ineff=
       F       F
Bank Sta=392.3,527.2
XS Rating Curve= 0 ,0
Exp/Cntr=0.3,0.1

Type RM Length L Ch R = 1 ,329630  ,280.1,295.4,237.3
BEGIN DESCRIPTION:
c/e of0.5/0.7 to correct drawdown in 100-500 yr events
adjusting banks/IFAs did not impact WSELs
END DESCRIPTION:
XS GIS Cut Line= 3
 2297685.7404051548763.4990652112297421.14463754548854.589411421
2296974.36817756549249.314244997
#Sta/Elev= 30
       0 2701.01    65.1  2681.3    94.7 2673.48   112.7 2669.79   145.5 2666.93
   216.5 2665.73   238.6 2664.09   263.8 2660.41   286.5 2649.56   299.4 2639.84
     314 2632.47   324.9 2629.44   473.3 2629.55     484 2632.56   492.1  2634.8
   510.6 2637.51   555.6 2636.99   567.7 2641.45   574.2 2642.21   591.2 2640.32
   597.9 2640.59   619.6 2646.32   656.4 2660.13   682.5 2667.05   712.7 2680.18
   724.8 2683.24   755.6 2696.71   812.3 2709.63   846.9 2719.55     876 2726.36
#Mann= 3 ,0,0
       0      .1       0     314    .035       0     484      .1       0
#XS Ineff= 2 , 0
       0                   574.7       0    2650
Permanent Ineff=
       F       F
Bank Sta=314,484
XS Rating Curve= 0 ,0
Exp/Cntr(USF)=0,0
Exp/Cntr=0.7,0.5

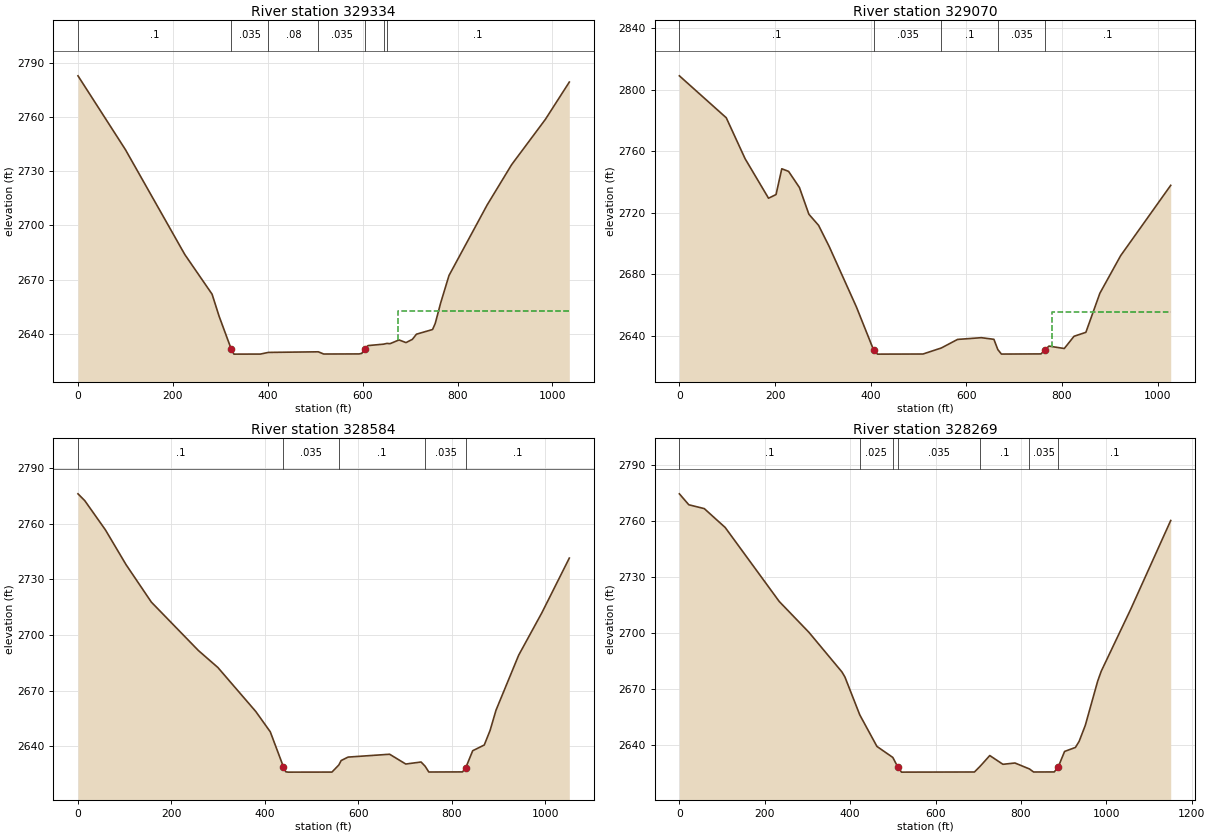
Type RM Length L Ch R = 1 ,329334  ,271.2,264.6,248.7
XS GIS Cut Line= 2
2297551.89097347548384.1924078122296809.34154191549105.883709278
#Sta/Elev= 30
       0 2782.71     100 2741.87   225.2 2683.81   282.6 2661.89   297.5 2649.62
   323.1 2631.43   328.7 2628.72   384.5 2628.75   401.2 2629.67   506.5    2630
   517.9 2628.78   592.6 2628.83   598.3 2629.16     604 2631.73   611.5 2633.45
   644.2 2634.24   651.1 2634.65   657.8 2634.51   676.6 2636.57   691.3  2635.1
   704.8 2636.91   713.3 2639.75   747.3 2642.34   752.9 2645.69   764.2 2656.89
   781.9 2672.21   862.3 2711.25   913.9 2733.54   984.9 2758.56  1035.5 2779.26
#Mann= 7 ,-1,0
       0      .1       0   323.1    .035       0   401.2     .08       0
   506.5    .035       0     604      .1       0   644.2    .025       0
   651.1      .1       0
#XS Ineff= 2 , 0
                             674         2652.49
Permanent Ineff=
       F       F
Bank Sta=323.1,604
XS Rating Curve= 0 ,0
Exp/Cntr(USF)=0,0
Exp/Cntr=0.3,0.1

Type RM Length L Ch R = 1 ,329070  ,490.9,485.7,461.7
XS GIS Cut Line= 2
     2297383.391      548118.7532296720.64564923548903.711981744
#Sta/Elev= 30
       0 2809.02      98 2781.75   137.4 2755.12   186.4 2729.42   202.1 2731.82
   214.1 2748.58   228.3 2746.88     251 2736.39   270.8 2718.99   291.1 2711.76
   313.4  2697.9   370.2 2658.67   406.3 2630.55   414.2 2628.03   509.3  2628.1
   547.6 2632.02   581.6 2637.59   631.2 2638.72   657.6 2637.67   665.8 2630.98
   673.3 2628.07   756.2 2628.17   764.7 2630.93   772.7 2633.25   804.8 2631.68
   825.1 2639.63   849.9  2642.2   879.2 2667.64   922.6 2692.06  1027.3 2737.81
#Mann= 5 ,-1,0
       0      .1       0   406.3    .035       0   547.6      .1       0
   665.8    .035       0   764.7      .1       0
#XS Ineff= 2 , 0
                          778.82         2655.28
Permanent Ineff=
       F       F
Bank Sta=406.3,764.7
XS Rating Curve= 0 ,0
Exp/Cntr=0.3,0.1

Type RM Length L Ch R = 1 ,328584  ,313.8,315,310.1
XS GIS Cut Line= 3
2297109.30270155547921.109706112 2296768.3304897548082.490286403
2296372.61710253548628.612710676
#Sta/Elev= 30
       0 2776.22    14.5 2772.55    58.8 2756.74     103 2737.97   157.1 2717.78
   257.9 2691.64   299.4 2682.53   380.6 2658.77   411.6 2647.82   439.8  2628.9
   444.8 2626.24   449.7 2626.06   543.6 2626.08   558.4 2629.93   563.3  2632.3
   578.1 2634.17   667.1 2635.71   701.6 2630.43   734.4 2631.52     743 2629.26
     751 2626.12   823.2 2626.18   830.1 2628.46   844.9 2637.61   869.6 2640.69
     882 2648.49   894.8 2659.48   943.3 2689.16   993.1 2712.12  1051.7 2741.55
#Mann= 5 ,-1,0
       0      .1       0   439.8    .035       0   558.4      .1       0
     743    .035       0   830.1      .1       0
Bank Sta=439.8,830.1
XS Rating Curve= 0 ,0
Exp/Cntr=0.3,0.1

Type RM Length L Ch R = 1 ,328269  ,247.8,316.5,319.9
XS GIS Cut Line= 4
2296945.28987761547752.2175609132296565.36442711547829.846604667
2296336.73575409 548147.554819412296127.23519593548454.445177669
#Sta/Elev= 30
       0 2774.39    22.1 2768.53    58.3 2766.48   107.3 2756.37   233.8 2716.78
   303.3 2700.28   380.8 2679.01   387.8 2676.29   422.5 2656.06   462.7 2639.16
   499.9 2633.26   511.4 2628.22   520.2  2625.4   691.1 2625.47   704.8 2628.63
     727 2634.28   757.8 2629.59     786 2630.28   819.9  2627.1   829.6 2625.47
     878  2625.5   887.3 2628.17   902.2 2636.47   927.6 2638.62   936.3 2641.88
   950.7 2650.41   979.7 2674.09     988  2679.4  1056.9 2712.51  1150.8 2760.11
#Mann= 7 ,-1,0
       0      .1       0   422.5    .025       0   499.9      .1       0
   511.4    .035       0   704.8      .1       0   819.9    .035       0
   887.3      .1       0
Bank Sta=511.4,887.3
XS Rating Curve= 0 ,0
Exp/Cntr=0.3,0.1