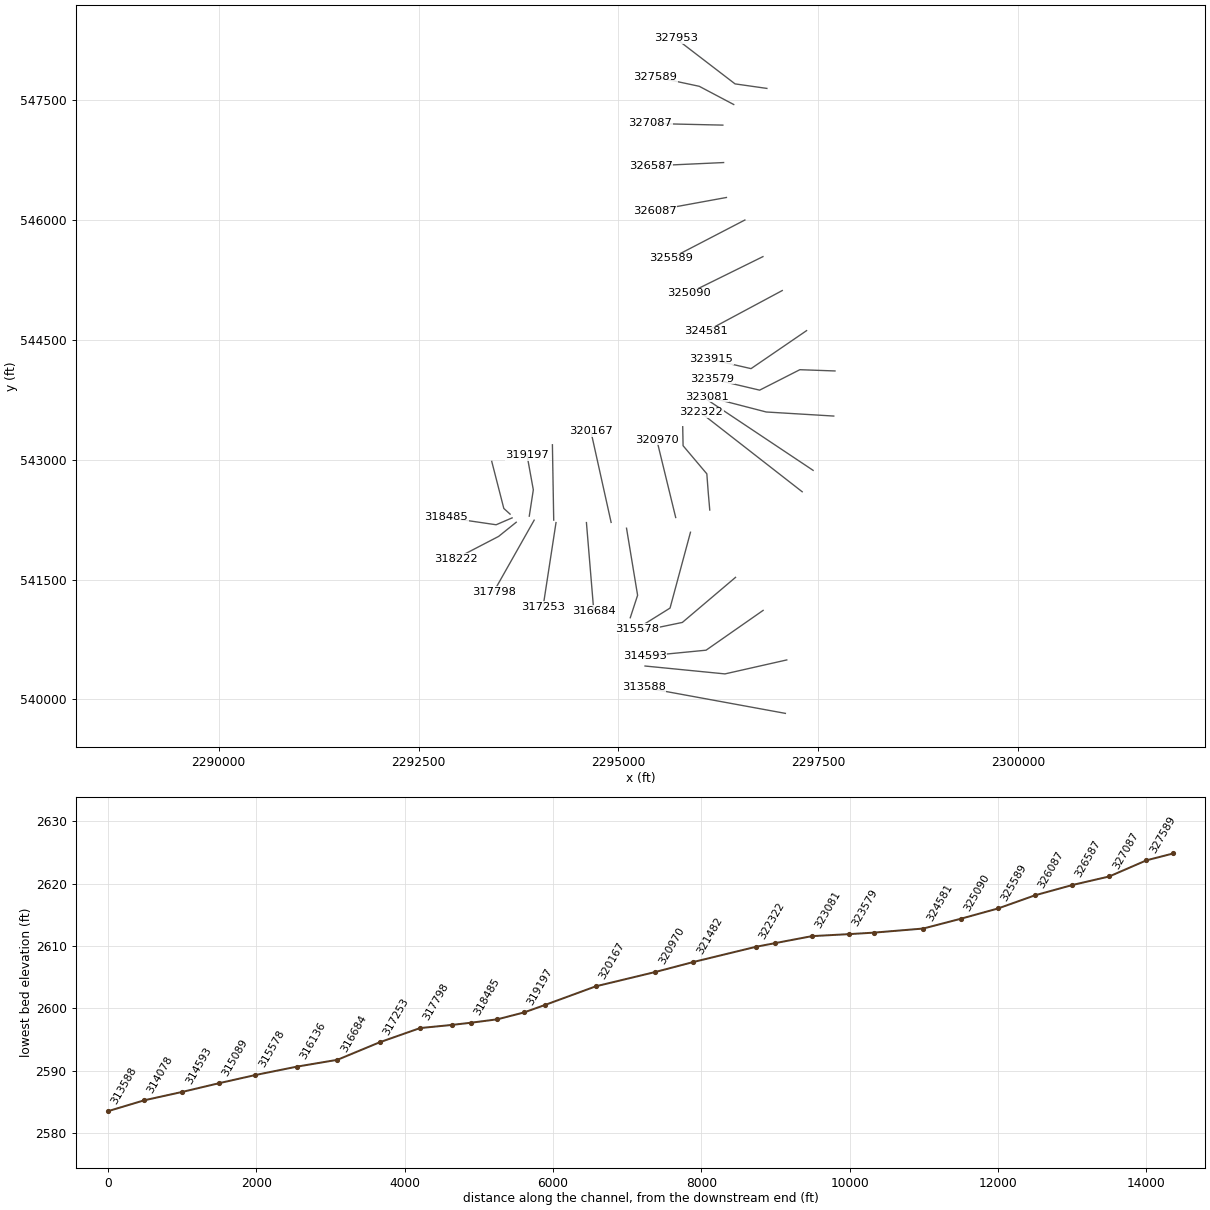
HEC-RAS study GRNBRRRV.prj: GRNBRRRV

--- GRNBRRRV.g01 (geometry) --- (continued)

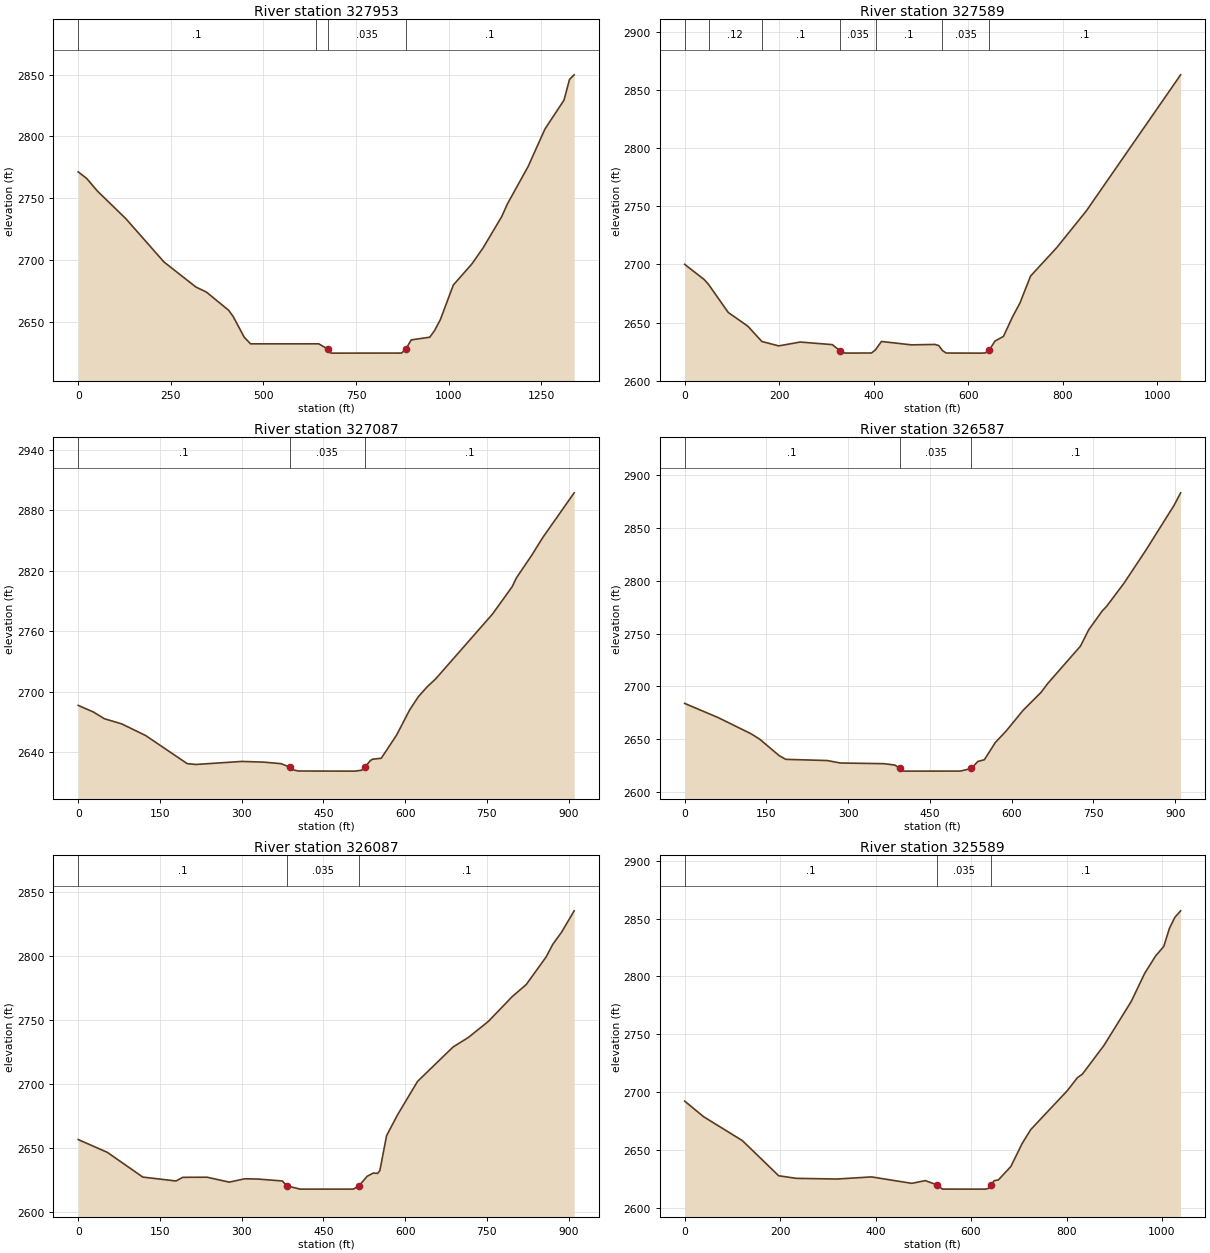
Type RM Length L Ch R = 1 ,327953  ,298.7,363.7,386.5
XS GIS Cut Line= 3
2296858.92329519547646.1577223042296460.64459698547702.809433687
2295717.30547489548272.759984571
#Sta/Elev= 30
       0 2771.33      23 2765.98    51.5 2755.92   128.9  2733.4   231.5 2698.51
   317.9 2678.24   346.2 2674.16   406.2 2659.45   418.6 2654.32   448.2 2637.73
   465.3 2632.33   649.4 2632.35   675.1 2627.88   682.3 2624.83   872.9 2624.88
  884.23 2627.97   899.2 2635.53   949.2  2637.7   962.4  2643.2   977.8 2651.94
  1012.8 2679.87  1063.2 2697.03  1093.4 2709.99  1143.2 2735.05  1158.9 2745.48
  1214.6 2775.57  1260.2 2805.96  1311.6 2829.29  1326.5 2846.06    1339 2849.75
#Mann= 4 ,-1,0
       0      .1       0  642.29    .025       0   675.1    .035       0
  884.23      .1       0
Bank Sta=675.1,884.23
XS Rating Curve= 0 ,0
Exp/Cntr(USF)=0,0
Exp/Cntr=0.3,0.1

Type RM Length L Ch R = 1 ,327589  ,456.6,501.9,516.5
XS GIS Cut Line= 3
2296444.09607058547444.6186400982296012.74070611547672.577822331
     2295464.121      547789.785
#Sta/Elev= 30
       0 2700.05    41.8  2686.8    50.7 2682.67    92.1  2658.7   133.6 2646.88
   163.2 2633.74     199 2629.94   244.2 2633.25   312.1 2631.04   328.9 2625.61
   339.2 2623.78     395 2623.81   403.6 2626.57   416.1 2633.75   479.5 2630.82
   529.4 2631.19   537.5 2630.19   545.1 2625.99   552.9 2623.81     627 2623.72
   635.7 2623.87   643.9 2626.22   656.2 2634.05   674.2  2638.1     693 2654.54
   709.3 2666.99   731.5 2689.94   787.1 2714.52   849.5 2745.98  1048.9 2862.95
#Mann= 7 ,-1,0
       0      .1       0    50.7     .12       0   163.2      .1       0
   328.9    .035       0   403.6      .1       0   545.1    .035       0
   643.9      .1       0
Bank Sta=328.9,643.9
XS Rating Curve= 0 ,0
Exp/Cntr=0.3,0.1

Type RM Length L Ch R = 1 ,327087  ,494.7,500,506.2
XS GIS Cut Line= 2
     2296308.148      547186.878     2295398.382      547207.531
#Sta/Elev= 30
       0 2686.39      28 2679.77      48 2673.16      80 2667.99     124 2656.38
     200 2628.57     216 2627.74   300.1 2630.76   340.1 2630.08   372.1 2628.53
   388.1 2625.15   396.1 2622.14   404.1 2621.24   508.1 2621.13   520.1 2622.02
   526.5 2625.37   536.1 2631.63   540.1 2632.95   556.1 2633.93   584.1 2656.84
   608.1 2681.83   624.1 2694.96   640.1 2704.72   656.1 2712.81   760.2 2777.06
   796.2 2804.13   804.2 2813.07   832.2 2835.44   852.2 2852.81     910 2897.36
#Mann= 3 ,0,0
       0      .1       0   388.1    .035       0   526.5      .1       0
Bank Sta=388.1,526.5
XS Rating Curve= 0 ,0
Exp/Cntr=0.3,0.1

Type RM Length L Ch R = 1 ,326587  ,488.1,500.1,511.3
XS GIS Cut Line= 2
     2296317.506      546718.503     2295408.469      546676.655
#Sta/Elev= 30
       0  2683.9    61.4 2670.47   121.5 2655.21   137.5 2650.06   173.5 2634.39
   185.5 2630.91   261.6 2629.78   285.6 2627.44   365.7 2626.81   385.7 2625.48
   394.6 2622.49   401.8 2619.79   405.8 2619.75   505.9  2619.8   525.9 2622.25
   537.9 2628.91   549.9 2630.55   569.9 2646.79     590 2657.82   621.2  2677.5
     654 2694.42     666 2702.67   726.2 2738.14   741.3 2753.58   766.1 2771.44
   774.2 2775.83   806.2 2797.83   846.2 2828.95   898.3 2871.79     910 2883.35
#Mann= 3 ,0,0
       0      .1       0   394.6    .035       0   525.9      .1       0
Bank Sta=394.6,525.9
XS Rating Curve= 0 ,0
Exp/Cntr=0.3,0.1

Type RM Length L Ch R = 1 ,326087  ,472.9,498,521.4
XS GIS Cut Line= 2
     2296352.764      546281.455     2295457.551      546117.885
#Sta/Elev= 30
       0 2656.81    53.5 2646.81   118.5 2627.52   179.5 2624.47   191.7 2627.32
   236.4 2627.41   277.1 2623.58   305.6 2626.18     330 2625.97   374.7 2624.47
   382.4 2620.68   407.2 2618.12   504.8 2618.11     515 2620.57   530.2 2628.14
   541.4 2630.64   549.5  2630.4   553.6 2632.76   565.8 2659.84   586.1 2676.22
   622.7 2702.22   687.8 2729.05   715.9 2736.51   752.8 2749.12   796.4 2768.41
     822 2777.76   858.6 2799.36   870.8 2809.19     887 2818.73     910 2835.35
#Mann= 3 ,0,0
       0      .1       0   382.4    .035       0     515      .1       0
Bank Sta=382.4,515
XS Rating Curve= 0 ,0
Exp/Cntr=0.3,0.1

Type RM Length L Ch R = 1 ,325589  ,505.1,498.7,497
XS GIS Cut Line= 2
2296583.53652388 545999.47871524     2295661.468      545520.471
#Sta/Elev= 30
       0 2692.14    39.8 2678.61     121 2657.92     197 2627.56   233.7 2625.33
   319.3 2624.74   391.4 2626.57   475.9    2621   504.1 2623.37   527.8 2619.83
   540.2 2616.03   630.3    2616   636.1  2616.6     642  2619.8   648.4 2623.26
   657.4 2624.02   683.5 2635.62     707  2655.4     725 2667.48   801.6 2701.13
   822.9 2712.45   833.2 2715.44   878.3 2740.19   935.7 2778.38   963.9 2802.72
   986.4 2817.52  1003.9 2826.05  1015.6 2841.52    1027 2851.11  1039.1 2856.74
#Mann= 3 ,0,0
       0      .1       0   527.8    .035       0     642      .1       0
Bank Sta=527.8,642
XS Rating Curve= 0 ,0
Exp/Cntr=0.3,0.1

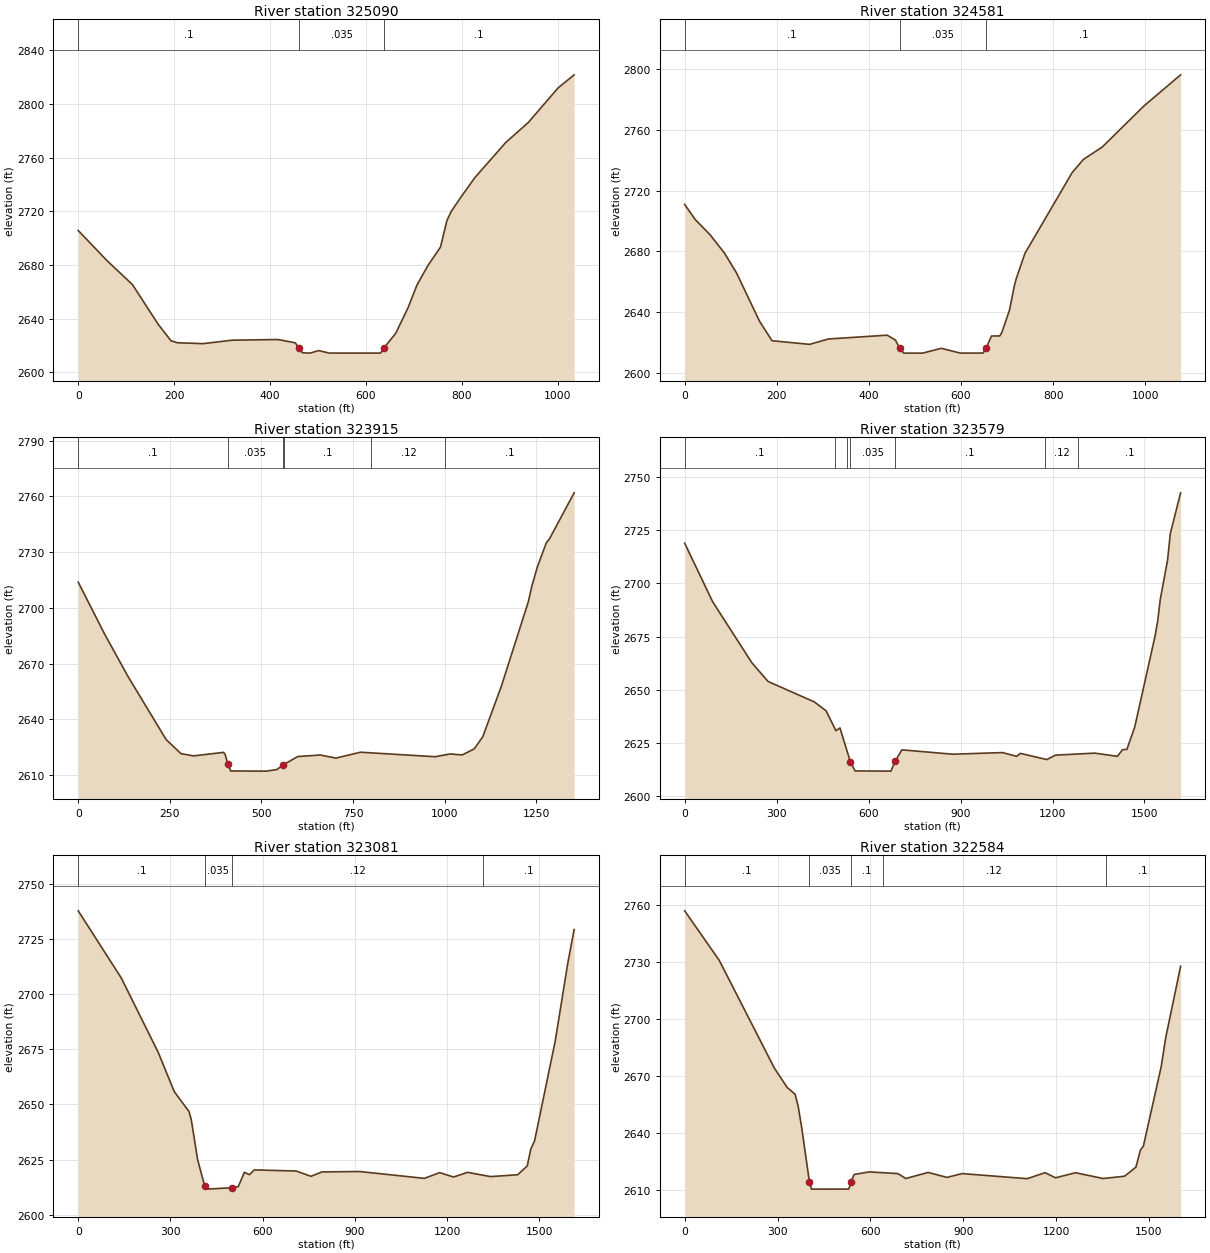
Type RM Length L Ch R = 1 ,325090  ,503.4,509.3,510.9
XS GIS Cut Line= 2
2296809.70988835545541.414897473     2295882.257      545084.055
#Sta/Elev= 30
       0  2705.8    59.7 2683.43   113.2 2665.41   166.7 2635.88   193.5 2623.58
   206.9 2622.09   260.4 2621.43   320.9 2624.01   416.6  2624.5   452.4 2622.05
   460.4 2618.32   467.3 2614.67   483.4 2614.36   501.2 2616.24   523.5  2614.4
   630.6 2614.38  637.69 2618.33   661.8 2628.95   687.9 2648.32   706.2 2664.99
   728.7 2679.38   755.4 2693.41   768.8 2713.22   777.7  2719.9   796.4 2729.83
   826.8 2745.08   891.4 2771.34   938.3 2786.23  1000.7 2812.12  1034.1 2821.83
#Mann= 3 ,0,0
       0      .1       0   460.4    .035       0  637.69      .1       0
Bank Sta=460.4,637.69
XS Rating Curve= 0 ,0
Exp/Cntr=0.3,0.1

Type RM Length L Ch R = 1 ,324581  ,636.3,666.3,665.7
XS GIS Cut Line= 2
2297051.37396805545116.956448737     2296102.193      544607.998
#Sta/Elev= 30
       0 2710.86    22.9 2700.91    55.4 2690.78    86.7 2678.65   112.6 2665.69
   162.5 2633.85   189.7 2620.96   271.4 2618.57   312.3 2622.12   439.7 2624.62
   457.5 2621.45   466.6 2616.36   475.7 2612.78   516.5 2612.78   557.4 2615.95
   598.2 2612.82   648.1 2612.81   655.1 2616.44   666.3 2624.07   684.4 2624.14
     689 2626.58   705.4 2641.14   716.2 2657.59   720.1 2661.96   738.9 2678.57
   841.3  2731.8     866 2740.61   906.8 2748.75   997.6  2775.9    1077 2796.37
#Mann= 3 ,0,0
       0      .1       0   466.6    .035       0   655.1      .1       0
Bank Sta=466.6,655.1
XS Rating Curve= 0 ,0
Exp/Cntr=0.3,0.1

Type RM Length L Ch R = 1 ,323915  ,347.8,335.3,323.3
XS GIS Cut Line= 3
2297355.63641347544615.3344217932296660.75633707544139.890158991
2296162.45417702544254.179645242
#Sta/Elev= 30
       0 2713.87      72 2685.93   136.4  2662.9     240  2629.1   280.5 2621.53
   314.4 2620.33   396.8 2622.22   401.2    2621  408.29 2615.75   416.2 2612.21
   513.1 2612.12   542.2 2612.97   557.5 2615.23   561.6 2615.75   598.8 2619.96
   660.2  2620.8   703.3 2619.14     770  2622.3   973.9 2619.88  1014.9 2621.37
  1047.8 2620.85  1080.6  2624.1  1103.9 2630.65  1154.5 2657.77  1228.3  2703.4
  1237.4 2711.45  1252.9 2722.13  1277.5 2735.17  1285.8 2737.16  1353.2 2761.97
#Mann= 6 ,-1,0
       0      .1       0  408.29    .035       0   557.5     .08       0
   561.6      .1       0     800     .12       0 1001.97      .1       0
Bank Sta=408.29,557.5
XS Rating Curve= 0 ,0
Exp/Cntr(USF)=0,0
Exp/Cntr=0.3,0.1

Type RM Length L Ch R = 1 ,323579  ,536.5,498.2,455.7
XS GIS Cut Line= 4
2297711.36014572544110.8196674822297271.49621162544126.566679571
 2296768.3304897543870.6461830762296171.45328721544011.590603585
#Sta/Elev= 30
       0  2718.9    91.2 2691.44   219.3 2662.74     272 2653.98   423.5 2644.35
   461.5 2640.17   493.2 2630.88   506.7 2632.15   540.3 2616.36   556.1 2611.97
   672.9 2611.88   686.2 2616.44   708.6 2621.87   874.7 2619.82  1036.8 2620.59
  1082.9 2618.81  1095.2 2620.21  1181.5 2617.31  1209.7 2619.38  1337.7 2620.33
  1411.7 2618.83  1428.1 2621.92  1442.7  2622.1  1468.2 2632.57    1535 2675.61
  1543.2 2682.46  1551.4 2692.38  1575.4 2711.03  1584.3 2723.46  1617.9 2742.56
#Mann= 7 ,-1,0
       0      .1       0  490.15     .12       0  530.15    .025       0
   540.3    .035       0   686.2      .1       0 1174.66     .12       0
 1284.66      .1       0
Bank Sta=540.3,686.2
XS Rating Curve= 0 ,0
Exp/Cntr=0.3,0.1

Type RM Length L Ch R = 1 ,323081  ,531.5,496.8,456.1
XS GIS Cut Line= 3
     2297696.017      543546.4522296850.74556484543597.375144446
2296108.45803896543789.438327954
#Sta/Elev= 30
       0 2737.93   140.1 2707.44   260.3 2673.65   312.4 2655.87   360.5 2646.79
   367.9 2643.05   388.5 2624.96   411.6 2612.94   416.6 2611.56   500.7 2612.19
   520.8 2612.72   540.8 2619.22   556.8 2618.12   572.9 2620.29   709.2 2619.78
   757.2 2617.39   793.3 2619.37   915.6 2619.56  1126.3 2616.44  1175.9 2619.06
  1221.3 2617.05  1266.8 2619.19  1341.1 2617.25  1429.7 2618.09    1461  2622.1
  1472.4 2629.72  1484.8 2633.51  1551.9 2678.76  1593.2 2714.48  1613.5 2729.46
#Mann= 4 ,-1,0
       0      .1       0   411.6    .035       0   500.7     .12       0
  1316.8      .1       0
Bank Sta=411.6,500.7
XS Rating Curve= 0 ,0
Exp/Cntr=0.3,0.1

Type RM Length L Ch R = 1 ,322584  ,267.3,262.2,254.3
XS GIS Cut Line= 2
     2297437.236      542867.2862296104.02865624543756.127109208
#Sta/Elev= 30
       0 2756.86   111.6 2730.83   289.7 2674.13     331 2663.97   356.9 2660.31
   366.6 2654.12   378.4 2642.46   403.1 2614.15   409.9 2610.44     530 2610.47
   537.6 2614.18   547.3 2618.12   596.3 2619.51   688.7 2618.62   714.6 2616.03
   786.7 2619.23   847.4 2616.62   896.3 2618.61    1107 2615.94  1164.4  2619.1
  1198.3  2616.4  1262.6 2619.06  1352.2 2616.03  1421.3 2617.24  1457.9 2622.02
  1472.4 2630.97    1482 2633.08  1539.7 2674.94  1554.1 2690.09  1602.3  2727.7
#Mann= 5 ,-1,0
       0      .1       0   403.1    .035       0   537.6      .1       0
     640     .12       0    1360      .1       0
Bank Sta=403.1,537.6
XS Rating Curve= 0 ,0
Exp/Cntr=0.3,0.1

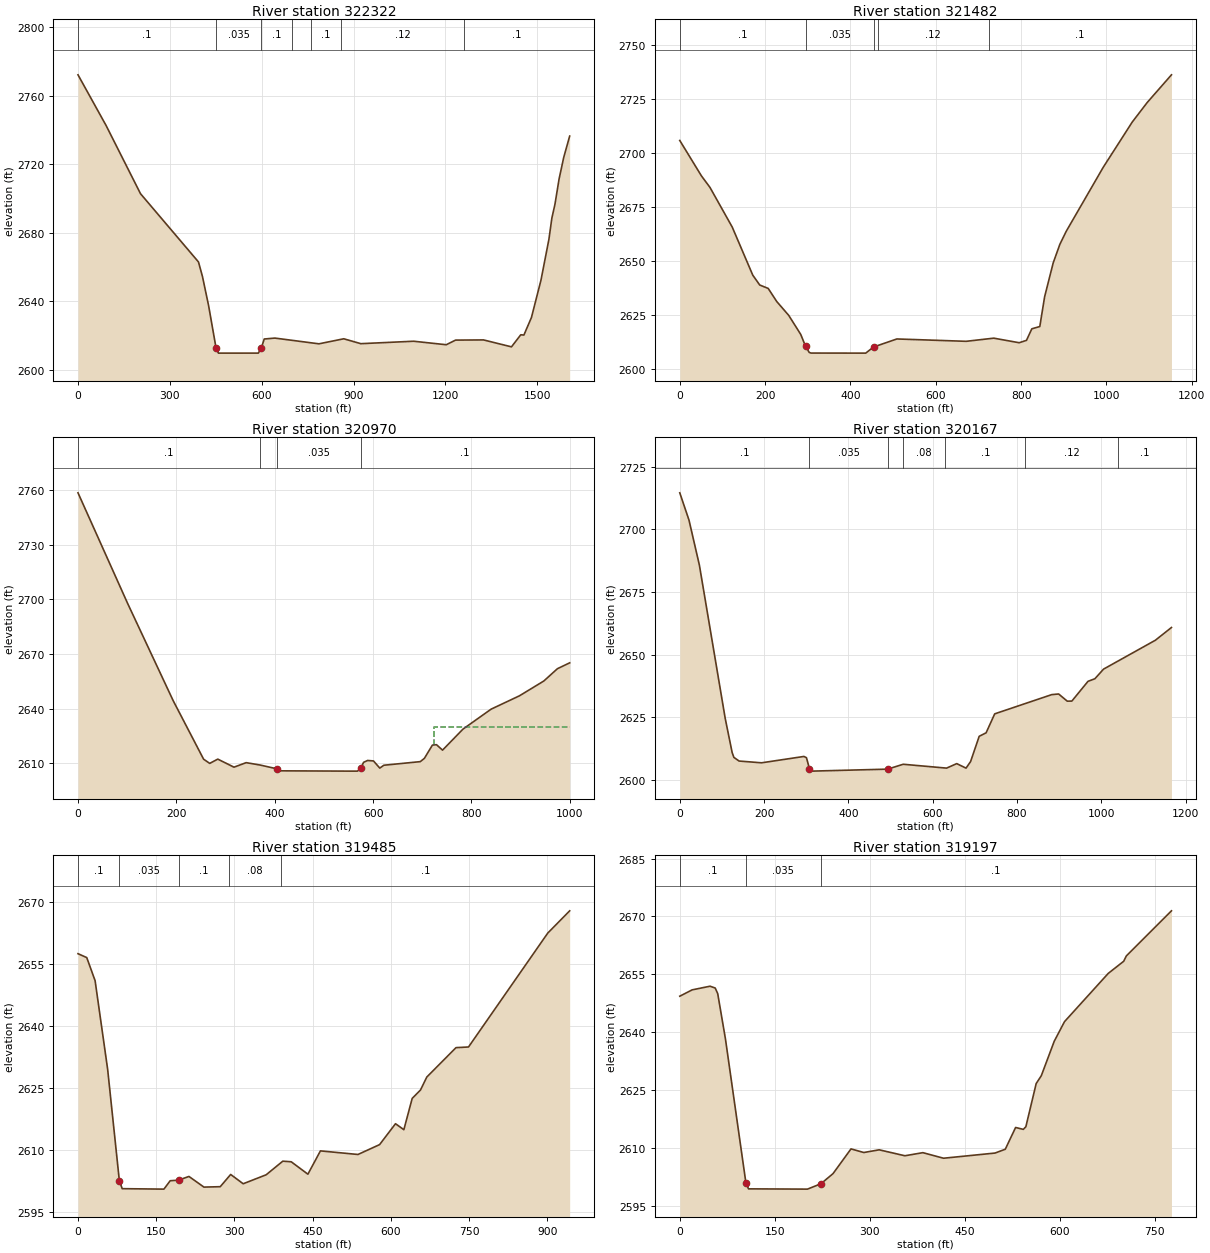
Type RM Length L Ch R = 1 ,322322  ,911.4,840.3,771.4
XS GIS Cut Line= 3
2297300.77746007542599.2678843372296057.30784967 543568.44272774
2296039.02153187 543591.30062499
#Sta/Elev= 30
       0  2772.3    92.1  2742.6   204.1 2702.92   393.5 2663.06   406.5 2654.56
   426.5 2637.62  450.61 2613.12   458.6 2609.84   589.1 2609.85   599.2 2613.08
   608.2 2618.08   643.1 2618.62   786.8 2615.27     868 2618.21   923.8 2615.36
  1096.2 2616.78  1202.7 2614.74  1233.1 2617.44  1324.4 2617.55  1415.7  2613.5
  1446.1 2620.56  1456.3 2620.39    1481 2630.68  1512.1 2652.47    1538  2676.3
  1547.6 2688.61  1557.7 2696.72  1571.2  2711.5  1586.4 2724.13  1605.8 2736.54
#Mann= 7 ,-1,0
       0      .1       0  450.61    .035       0   599.2      .1       0
     700     .12       0     760      .1       0     860     .12       0
    1260      .1       0
Bank Sta=450.61,599.2
XS Rating Curve= 0 ,0
Exp/Cntr(USF)=0,0
Exp/Cntr=0.3,0.1

Type RM Length L Ch R = 1 ,321482  ,496.4,511.8,514.2
XS GIS Cut Line= 5
2296144.16785922542370.6889118362296125.88154142542580.981566537
2296107.59522362542823.2752773872295810.44255937543175.286895038
2295805.87097992543413.009026439
#Sta/Elev= 30
       0  2705.9    50.7 2689.51    70.8 2684.15     123 2665.77   171.1 2643.52
   187.4 2638.96   207.3 2637.37   227.3 2631.31   255.4 2624.89   283.5 2616.09
   294.9 2610.54   303.5 2607.72   307.6 2607.44   435.9 2607.41   454.1 2610.24
   508.9 2613.97   671.2 2612.88     736 2614.34   795.6 2612.22   812.7 2613.33
   825.2 2618.67   843.9 2619.73   855.2 2633.51   875.3 2649.21     891 2657.83
   905.8 2663.82   992.6 2693.49  1060.7 2714.46  1095.5 2723.44  1152.5  2736.3
#Mann= 5 ,-1,0
       0      .1       0   294.9    .035       0   454.1    .025       0
  464.07     .12       0  724.07      .1       0
Bank Sta=294.9,454.1
XS Rating Curve= 0 ,0
Exp/Cntr(USF)=0,0
Exp/Cntr=0.3,0.1

Type RM Length L Ch R = 1 ,320970  ,803.6,803.2,798.5
XS GIS Cut Line= 2
  2295717.975854542277.0373588512295481.27708503543248.318514282
#Sta/Elev= 30
       0 2758.54   100.9 2697.85   193.6 2644.44   255.4 2612.36   267.8 2610.06
   284.2  2612.4   317.2 2607.98   341.9 2610.46   370.7 2609.13   403.6 2607.13
   412.1 2605.97   551.8 2605.81   568.3 2605.81   574.8 2607.35   580.7 2610.65
   588.9 2611.66   600.8  2611.4   613.6 2607.47   621.8 2609.04   695.9 2611.02
   704.2 2612.79   720.6 2620.09   728.9 2620.32   741.2 2617.33   782.8 2628.87
     840 2639.82   897.7 2647.16   947.1 2655.26   974.8 2662.02   999.7 2665.24
#Mann= 4 ,-1,0
       0      .1       0   370.7     .12       0   403.6    .035       0
   574.8      .1       0
#XS Ineff= 2 , 0
       0                   724.7       0    2630
Permanent Ineff=
       F       F
Bank Sta=403.6,574.8
XS Rating Curve= 0 ,0
Exp/Cntr(USF)=0,0
Exp/Cntr=0.3,0.1

Type RM Length L Ch R = 1 ,320167  ,694.9,682.1,675.3
XS GIS Cut Line= 2
2294909.93522889542215.8221599792294656.91240689543354.424858992
#Sta/Elev= 30
       0 2714.64    21.9 2703.73    46.5 2685.79   107.9 2624.45   124.3 2610.89
   128.4 2608.99   140.7 2607.54     194 2606.83   294.5 2609.37   300.5 2608.88
   307.7 2604.43   312.8 2603.51   493.1  2604.3     530 2606.25   632.9 2604.71
     657  2606.5   679.1 2604.71   689.9 2607.33   710.3 2617.41   726.7 2618.81
   747.1 2626.38   882.4 2634.06   898.8 2634.31   919.2 2631.45   930.1 2631.48
   968.4 2639.36   984.8 2640.41  1005.3 2644.24  1128.2 2655.77  1166.4 2660.86
#Mann= 7 ,-1,0
       0      .1       0   307.7    .035       0   493.1    .025       0
     530     .08       0     630      .1       0     820     .12       0
    1040      .1       0
Bank Sta=307.7,493.1
XS Rating Curve= 0 ,0
Exp/Cntr(USF)=0,0
Exp/Cntr=0.3,0.1

Type RM Length L Ch R = 1 ,319485  ,301.7,287.9,276.4
XS GIS Cut Line= 2
2294191.67689547542244.3892527862294175.35284243 543187.10331541
#Sta/Elev= 30
       0 2657.54    16.8  2656.6    32.8    2651    56.8 2629.61   79.29 2602.59
    84.8 2600.64   164.8 2600.53   176.8 2602.56   192.8  2602.7   212.8  2603.6
   241.5 2601.02   272.8 2601.12   292.8 2604.08   316.8 2601.83   360.8    2604
   392.8  2607.3   408.9 2607.15   440.9 2604.15   464.9 2609.79   536.9 2608.92
   578.4 2611.31   608.9 2616.37   624.9 2614.92   640.9  2622.5   656.8 2624.53
   668.9 2627.67   724.9 2634.79   748.9 2634.95   900.8 2662.52   942.9 2667.92
#Mann= 5 ,-1,0
       0      .1       0   79.29    .035       0   192.8      .1       0
     290     .08       0     390      .1       0
Bank Sta=79.29,192.8
XS Rating Curve= 0 ,0
Exp/Cntr(USF)=0,0
Exp/Cntr=0.3,0.1

Type RM Length L Ch R = 1 ,319197  ,324.9,356,404.7
XS GIS Cut Line= 3
2293885.80663572542293.9442501842293936.51306473542623.536038755
 2293857.2842694543059.294413069
#Sta/Elev= 30
       0 2649.32    19.5 2650.96    47.8 2651.91    55.9 2651.44    59.9    2650
    72.1 2638.26   104.4 2600.96   108.5 2599.38   201.6 2599.31   222.92600.702
     242 2603.33   270.4 2609.74   290.6  2608.8   314.9  2609.5   355.5 2607.96
   383.9 2608.76   416.5 2607.32   497.8 2608.66     514 2609.65   530.3 2615.29
   542.5  2614.8   546.5 2615.49   562.8 2626.68   570.9 2628.72   591.3 2637.64
   607.5 2642.72   676.6 2655.23     701 2658.38   705.1 2659.75   776.4 2671.45
#Mann= 3 ,0,0
       0      .1       0   104.4    .035       0   222.9      .1       0
Bank Sta=104.4,222.9
XS Rating Curve= 0 ,0
Exp/Cntr(USF)=0,0
Exp/Cntr=0.3,0.1

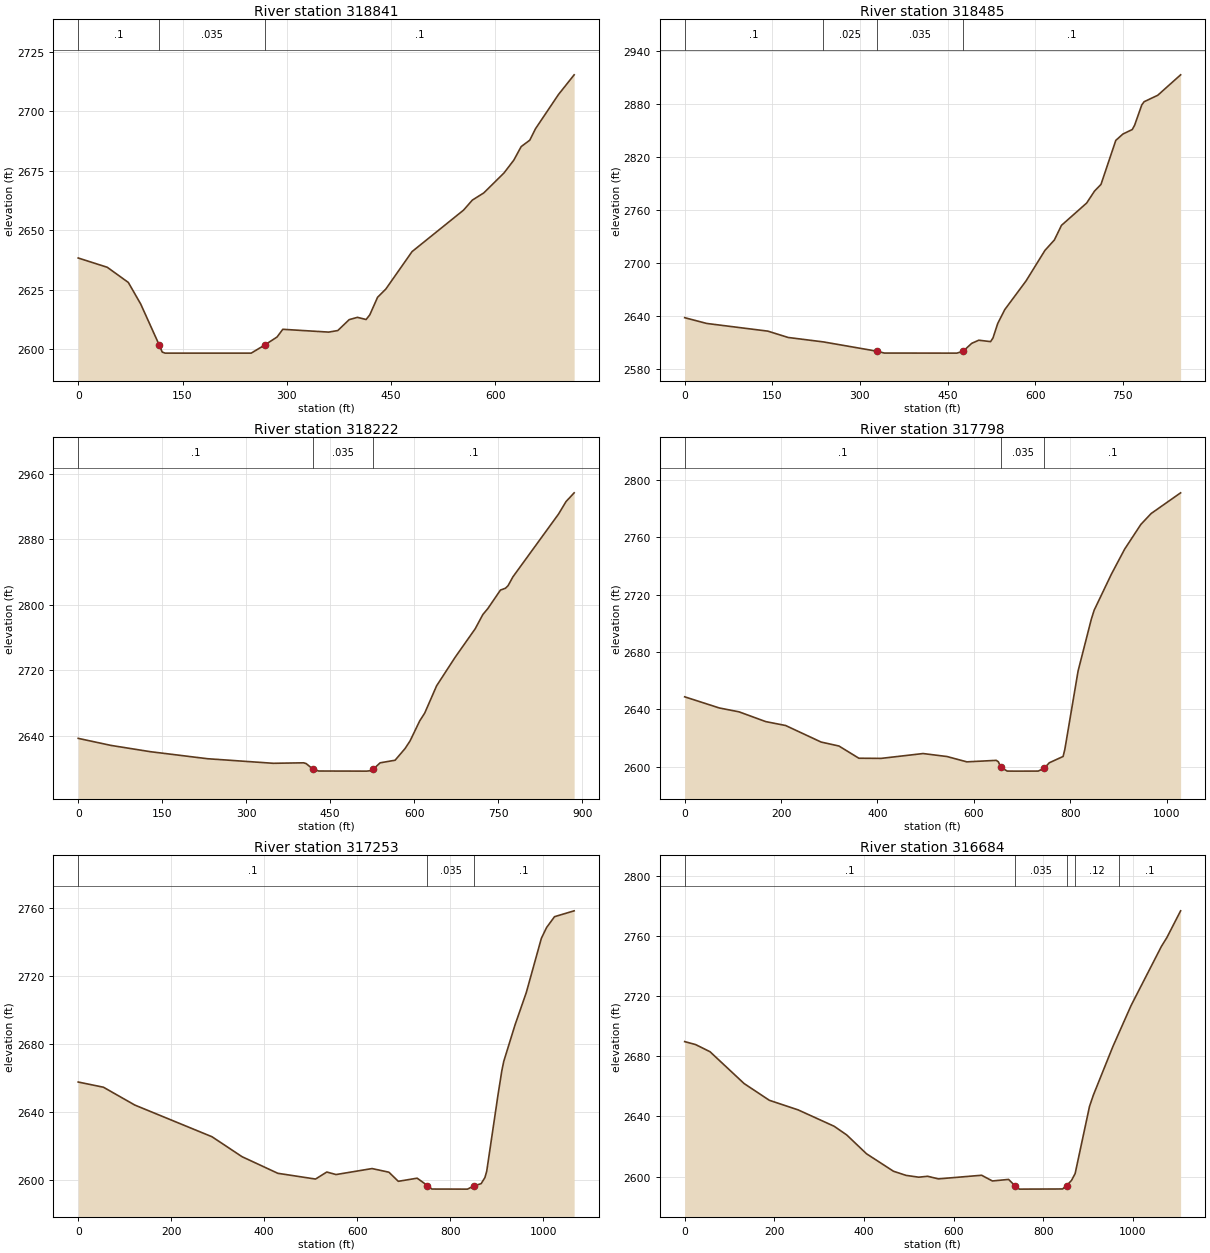
Type RM Length L Ch R = 1 ,318841  ,288.4,355.7,499.4
XS GIS Cut Line= 3
2293645.55456641542319.529137135 2293567.2576772542390.588045374
2293416.28437643542978.971639246
#Sta/Elev= 30
       0 2638.27    41.8 2634.36    72.1 2627.97    89.9 2618.87   116.2 2601.84
   120.8 2598.67   124.9 2598.22   248.8 2598.22   268.1 2601.61     286 2605.02
   294.2 2608.25   360.2 2607.07   373.3 2607.73   389.7 2612.32   401.6 2613.29
     414 2612.37   419.3 2614.32   430.5 2621.73   442.3 2625.17   480.1 2640.96
   554.1 2658.41   566.8 2662.64   583.3 2665.68   612.2 2674.03   626.4 2679.45
     637 2685.16   649.4 2687.87   657.6 2692.68   690.7 2707.11   713.2 2715.38
#Mann= 3 ,0,0
       0      .1       0   116.2    .035       0   268.1      .1       0
Bank Sta=116.2,268.1
XS Rating Curve= 0 ,0
Exp/Cntr(USF)=0,0
Exp/Cntr=0.3,0.1

Type RM Length L Ch R = 1 ,318485  ,218.9,262.7,324
XS GIS Cut Line= 3
 2293670.9370984542272.266216842 2293471.1403261542186.266203465
2292846.40070094542277.954142834
#Sta/Elev= 30
       0 2637.87    37.8 2631.32   142.4 2622.61   177.2 2615.42   237.6 2610.38
   329.7 2599.77   341.8 2597.75     466 2597.67  476.66 2599.81   491.4 2608.78
   503.5 2612.32   523.7 2610.72   527.8 2614.87   535.9  2631.3     548 2647.06
   584.4 2679.57   616.7 2714.15   632.9 2726.03     645 2742.56   688.1 2767.88
   701.6 2781.45   712.7 2789.05     738 2838.92   750.1 2846.12   766.3 2851.32
   770.3 2856.25   782.5 2879.16   786.5  2882.8   809.9 2890.15     849 2913.32
#Mann= 4 ,-1,0
       0      .1       0   237.6    .025       0   329.7    .035       0
  476.66      .1       0
Bank Sta=329.7,476.66
XS Rating Curve= 0 ,0
Exp/Cntr(USF)=0,0
Exp/Cntr=0.3,0.1

Type RM Length L Ch R = 1 ,318222  ,381.5,424.9,460.8
XS GIS Cut Line= 3
2293722.70092681542217.7657333482293501.98565485542040.338589881
2292967.37291803541762.829688329
#Sta/Elev= 30
       0 2637.24    58.4 2628.67   128.6 2621.02   230.8 2612.43   348.3 2606.86
   402.4 2607.44   406.9 2606.55418.50162600.085   429.3 2597.45   515.1 2597.31
   524.1 2598.01527.19162599.905   539.1 2607.43   565.8 2610.59   583.6 2624.84
   592.5 2634.09   609.7 2658.47   618.7 2668.08   639.9 2701.28   672.8 2735.86
   708.9 2770.89   722.4 2788.07   731.4 2795.45   753.9 2817.95   762.9 2820.22
   767.5  2823.3   776.2 2834.12   857.6  2910.6   871.1 2925.91   885.5 2936.49
#Mann= 3 ,-1,0
       0      .1       0418.5016    .035       0527.1916      .1       0
Bank Sta=418.5016,527.1916
XS Rating Curve= 0 ,0
Exp/Cntr(USF)=0,0
Exp/Cntr=0.3,0.1

Type RM Length L Ch R = 1 ,317798  ,519.9,545,569.5
XS GIS Cut Line= 2
2293947.15347286542243.8612108892293441.09768304541348.000375902
#Sta/Elev= 30
       0 2648.68      72 2640.88   112.8 2638.19   168.1 2631.38   209.4 2628.65
     283 2617.11   320.1 2614.33   361.4 2605.81   407.4  2605.7   494.6 2609.08
   544.3 2606.99   585.4 2603.28   646.3 2604.33   650.8 2603.35   655.9 2599.44
   669.2 2596.84   687.6 2596.81   733.5 2596.84   746.1 2598.89   756.5 2602.65
   785.1 2607.04   788.7 2611.99   816.2 2666.72   843.7 2702.94   849.6 2709.17
   885.1 2734.15   912.7 2751.71   946.5 2769.03   967.8 2776.62  1028.9 2791.05
#Mann= 3 ,0,0
       0      .1       0   655.9    .035       0   746.1      .1       0
Bank Sta=655.9,746.1
XS Rating Curve= 0 ,0
Exp/Cntr(USF)=0,0
Exp/Cntr=0.3,0.1

Type RM Length L Ch R = 1 ,317253  ,552.9,569,587
XS GIS Cut Line= 2
2294220.40760181542213.5125594982294058.39691462541159.467124783
#Sta/Elev= 30
       0 2657.65    54.2  2654.6   121.7 2644.08   287.7  2625.4   352.4 2613.63
   429.3 2603.85   510.3 2600.47   534.5 2604.61   554.5 2603.12   631.9 2606.65
   668.1  2604.5   688.3 2599.13   728.8 2600.98   750.9 2596.64   760.5 2594.58
     837 2594.53   851.3 2596.48   866.4 2597.76   874.5 2601.33   877.4  2604.1
   878.5 2605.26   902.8 2650.31   910.9 2664.31     915  2669.8   939.2 2691.26
   963.5  2710.4   995.9 2742.36  1007.2 2748.75  1024.2 2755.11  1066.4 2758.56
#Mann= 3 ,0,0
       0      .1       0   750.9    .035       0   851.3      .1       0
Bank Sta=750.9,851.3
XS Rating Curve= 0 ,0
Exp/Cntr(USF)=0,0
Exp/Cntr=0.3,0.1

Type RM Length L Ch R = 1 ,316684  ,541.6,547.9,557.6
XS GIS Cut Line= 2
 2294601.0351199542213.5125594982294692.77611144541110.668725027
#Sta/Elev= 30
       0 2689.76    24.4 2687.78    56.5 2683.05   132.6 2661.89     189 2650.75
   253.2 2644.38   333.5 2633.51   361.6 2627.73   405.7 2615.23   465.9 2603.61
     494 2600.86   522.3 2599.66   542.2 2600.26   566.3 2598.53   662.6 2600.94
   686.7 2597.14   722.8 2598.18   736.9    2594   746.9 2591.72   843.2 2591.82
  852.05 2593.97   863.3 2597.54   871.3 2602.04   903.4 2646.69   911.9 2654.14
   955.5 2686.44   996.3 2713.83    1064 2753.12    1076 2758.88  1106.7 2776.67
#Mann= 5 ,-1,0
       0      .1       0   736.9    .035       0  852.05    .025       0
     870     .12       0     970      .1       0
Bank Sta=736.9,852.05
XS Rating Curve= 0 ,0
Exp/Cntr(USF)=0,0
Exp/Cntr=0.3,0.1

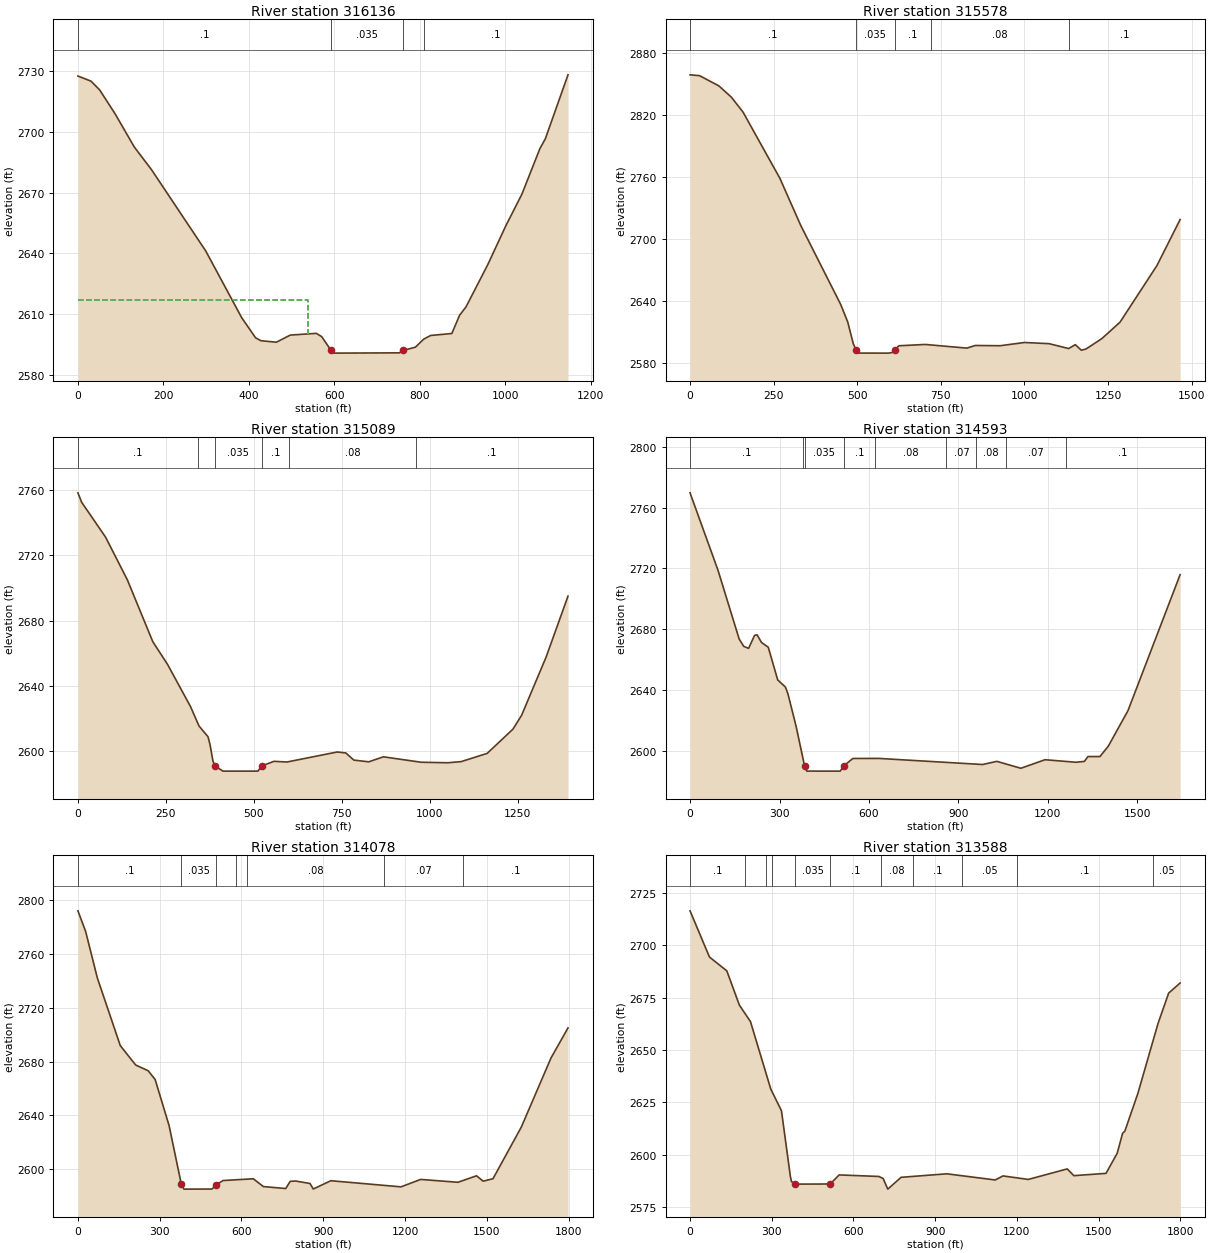
Type RM Length L Ch R = 1 ,316136  ,592.7,557.3,526.6
XS GIS Cut Line= 3
2295102.68266939 542143.242863852295241.27012469541303.910388059
2295149.52913315541022.831605468
#Sta/Elev= 30
       0 2727.66    30.5 2725.16    50.7 2720.85    87.2 2708.91   131.8 2692.59
   172.4 2681.26   298.9 2641.19   383.2 2608.12   415.6  2598.2     428 2596.77
   464.3 2596.02   496.7 2599.54   557.5  2600.4   570.3 2598.78   591.1 2592.28
   598.1 2590.62   752.1 2590.76   760.2 2591.92   789.5 2593.57   808.9 2597.54
   825.1 2599.36   874.6 2600.32   892.9 2609.39   907.7 2613.44   958.8 2634.41
  1000.8 2653.52  1038.7  2669.3  1080.8 2691.83  1093.4 2696.63  1146.4 2728.26
#Mann= 4 ,-1,0
       0      .1       0   591.1    .035       0   760.2    .025       0
     810      .1       0
#XS Ineff= 2 , 0
          537.46 2616.78
Permanent Ineff=
       F       F
Bank Sta=591.1,760.2
XS Rating Curve= 0 ,0
Exp/Cntr(USF)=0,0
Exp/Cntr=0.3,0.1

Type RM Length L Ch R = 1 ,315578  ,539.8,489.3,444.4
XS GIS Cut Line= 3
2295902.97642537542092.4925281052295647.27281066541143.851636861
2295237.36625271540888.148022143
#Sta/Elev= 30
       0 2859.12    28.3 2858.33    86.3 2848.38   123.6 2837.45   158.4 2823.03
   268.6 2758.85   330.7 2713.35   450.9 2636.23   471.6 2619.44   488.1 2598.48
   496.4 2592.41   504.7 2589.32   592.4 2589.28   604.1 2589.78   611.9 2592.52
   624.8 2596.41   703.6 2597.69   827.8 2594.14   852.7 2596.69   927.3 2596.46
  1000.3 2599.59  1073.8 2598.45  1132.3 2593.73  1152.2 2597.49    1170 2592.09
  1184.2 2593.29  1231.3  2603.3  1285.7 2619.22  1396.1 2674.07  1465.6 2718.83
#Mann= 5 ,-1,0
       0      .1       0   496.4    .035       0   611.9      .1       0
     720     .08       0  1132.5      .1       0
Bank Sta=496.4,611.9
XS Rating Curve= 0 ,0
Exp/Cntr(USF)=0,0
Exp/Cntr=0.3,0.1

Type RM Length L Ch R = 1 ,315089  ,504.8,496.3,488.8
XS GIS Cut Line= 3
     2296466.568      541528.0672295801.47575388540964.273525761
2295291.02287443540858.402560391
#Sta/Elev= 30
       0 2758.25    10.7 2752.46    78.7 2731.11   140.6 2704.99   212.9 2667.16
   254.8 2653.28     320 2627.51   344.3 2615.57   369.9 2608.99   375.5 2604.25
     384 2594.04   389.7 2591.18   412.2 2587.97   511.8 2587.97   522.3  2591.1
   557.2 2593.97   594.1 2593.55   737.3 2599.68   761.5 2599.09   784.5 2594.72
   826.8 2593.66   868.4 2596.73   975.4 2593.41  1051.6 2593.09  1089.7  2593.8
  1163.3 2598.81  1236.8 2613.67  1261.4 2622.18  1330.8 2657.66  1393.2 2695.04
#Mann= 6 ,-1,0
       0      .1       0     340    .025       0   389.7    .035       0
   522.3      .1       0     600     .08       0   961.9      .1       0
Bank Sta=389.7,522.3
XS Rating Curve= 0 ,0
Exp/Cntr=0.3,0.1

Type RM Length L Ch R = 1 ,314593  ,550.2,514.5,484.7
XS GIS Cut Line= 3
     2296811.881      541114.842 2296098.1700244540616.828919503
2295328.56538773540541.758408215
#Sta/Elev= 30
       0 2769.82    93.8 2718.81   164.7 2673.59   180.1 2668.73   196.3 2667.41
   216.5 2675.99   225.1 2676.27   239.4 2671.34   262.4 2668.12     294 2646.63
   319.9 2641.92   328.5 2637.33   355.7 2616.06  384.02 2590.05   391.7 2586.57
   503.7 2586.58   515.2 2589.96   545.9 2594.91     633 2594.94   980.8 2590.92
    1029    2593  1109.4 2588.45  1190.4 2594.08  1294.3 2592.41  1322.4 2592.98
  1334.5 2596.16  1374.7 2596.18  1402.9 2603.09  1468.7 2626.43  1643.5 2715.95
#Mann= 9 ,-1,0
       0      .1       0     380    .025       0  384.02    .035       0
   515.2      .1       0     620     .08       0     860     .07       0
  960.29     .08       0 1060.29     .07       0 1260.29      .1       0
Bank Sta=384.02,515.2
XS Rating Curve= 0 ,0
Exp/Cntr=0.3,0.1

Type RM Length L Ch R = 1 ,314078  ,527.7,490.4,459.8
XS GIS Cut Line= 3
     2297107.765      540494.8922296334.35427921540320.134648991
2295334.41399643540418.749967384
#Sta/Elev= 30
       0 2792.07    28.3  2776.8    71.3 2742.16   155.4 2691.89   211.8 2677.48
   257.9 2673.19   283.3 2666.69   334.5 2632.38  379.54 2588.67   389.1 2585.22
   491.7 2585.28   508.1 2588.55   532.7 2591.62   643.5  2592.9   680.3 2587.12
   762.3 2585.66   778.7 2591.01   799.1 2591.23   851.4  2589.4   863.4 2585.31
   927.7 2591.47    1185 2586.91  1257.3 2592.44    1394 2590.31  1462.3 2595.13
  1486.4 2591.13  1522.6 2592.96  1626.4 2631.31  1735.6  2682.8  1797.7 2705.04
#Mann= 7 ,-1,0
       0      .1       0  379.54    .035       0   508.1     .08       0
     580      .1       0     620     .08       0 1122.91     .07       0
 1412.91      .1       0
Bank Sta=379.54,508.1
XS Rating Curve= 0 ,0
Exp/Cntr=0.3,0.1

Type RM Length L Ch R = 1 ,313588  ,543.8,518.2,501.1
XS GIS Cut Line= 2
     2297090.331      539826.2062295320.45267638540150.508687188
#Sta/Elev= 30
       0 2716.45    71.3 2694.38     135 2687.77   181.1  2671.4   221.8 2663.55
   296.5 2631.26   335.7 2620.91   368.2 2589.68   372.3 2587.09   385.9 2585.86
   514.6 2585.92   547.4 2590.26   693.5 2589.52     709 2588.54     726 2583.47
   774.8 2589.11   942.7 2590.79  1120.5 2587.85  1148.9 2589.78  1241.7  2588.1
  1384.8 2593.13  1409.2 2589.91  1527.2    2591  1568.2  2600.6  1588.2 2610.17
  1596.3 2611.16  1643.8 2629.05  1718.3 2662.68  1757.2 2677.14  1799.3 2681.97
#Mann= 11 ,-1,0
       0      .1       0     200     .12       0     280      .1       0
     300     .12       0   385.9    .035       0   514.6      .1       0
     700     .08       0     820      .1       0    1000     .05       0
    1200      .1       0    1700     .05       0
Bank Sta=385.9,514.6
XS Rating Curve= 0 ,0
Exp/Cntr=0.3,0.1