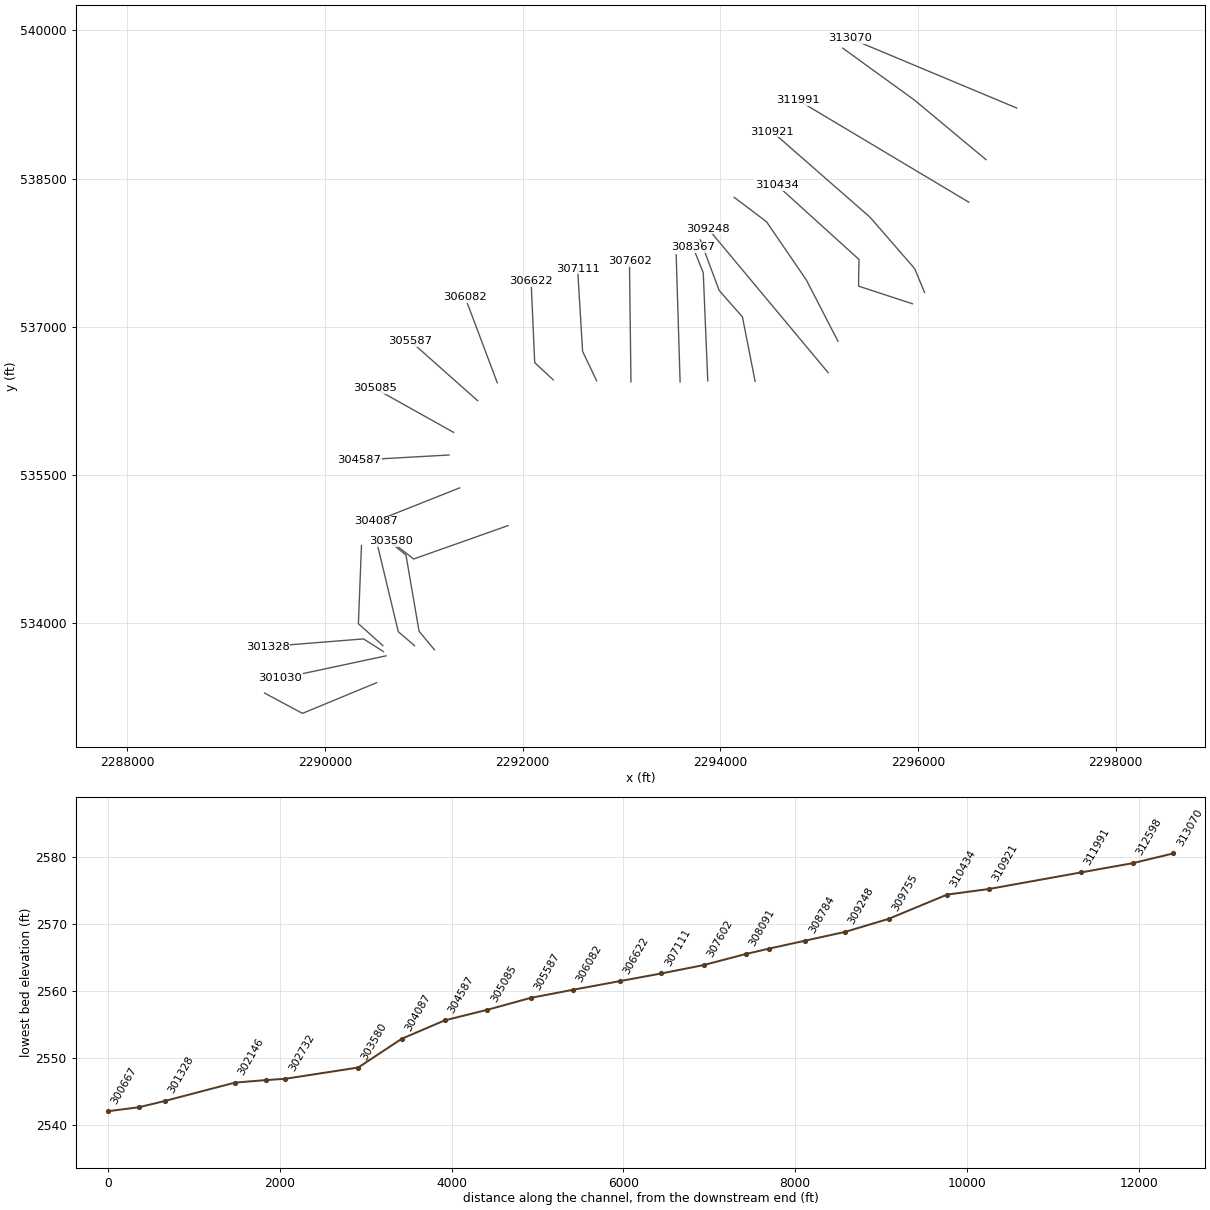
HEC-RAS study GRNBRRRV.prj: GRNBRRRV

--- GRNBRRRV.g01 (geometry) --- (continued)

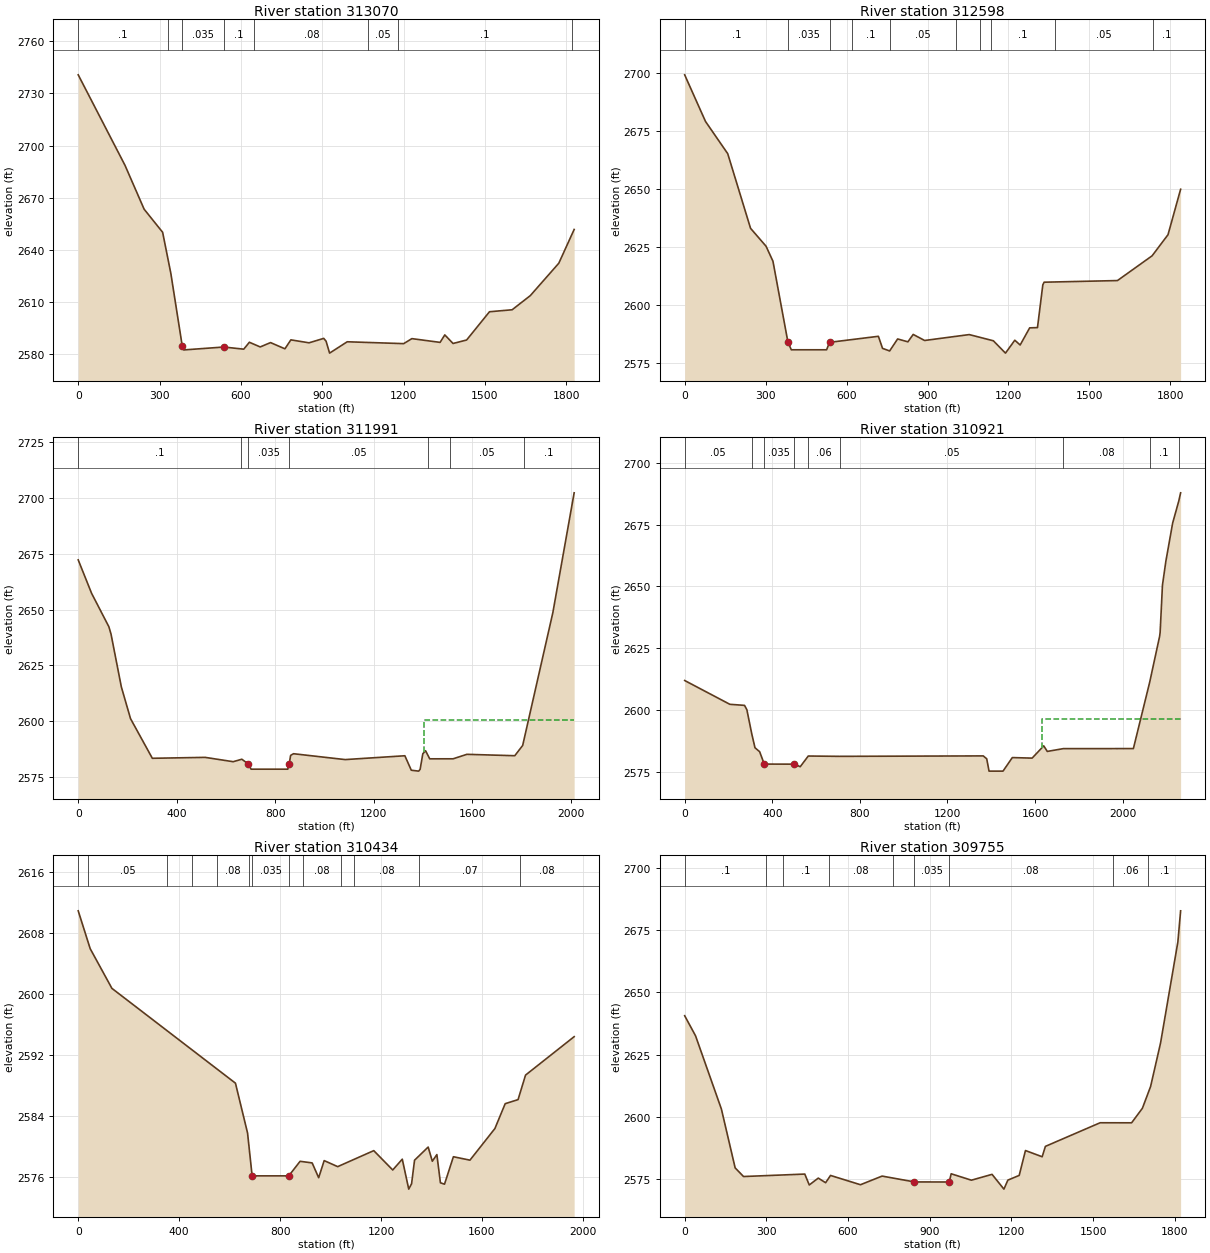
Type RM Length L Ch R = 1 ,313070  ,501.6,471.4,443.8
XS GIS Cut Line= 2
2296999.46374396539214.3316002452295312.12794812539920.529414229
#Sta/Elev= 30
       0 2740.71   172.7 2688.61   243.1 2663.41   311.4 2650.12   341.8 2626.34
   383.7 2584.75   389.5 2582.44   536.9 2584.11   610.6 2582.88   631.3 2586.85
   671.3 2584.16   709.3 2586.66   762.4 2583.09   784.4 2588.23   851.4 2586.53
   905.5 2589.08   914.2 2587.47   927.2  2580.6   992.2 2587.13  1200.4 2586.06
  1230.7 2588.94  1334.8 2586.78  1352.1 2591.09  1382.5 2586.15  1432.6 2588.15
  1516.9 2604.41  1600.4 2605.54  1667.6  2613.7  1772.7 2632.35  1829.2 2651.74
#Mann= 8 ,-1,0
       0      .1       0     330     .12       0   383.7    .035       0
   536.9      .1       0     650     .08       0    1070     .05       0
    1180      .1       0    1820     .03       0
Bank Sta=383.7,536.9
XS Rating Curve= 0 ,0
Exp/Cntr=0.3,0.1

Type RM Length L Ch R = 1 ,312598  ,575.3,607.4,611.1
XS GIS Cut Line= 3
     2296687.738       538691.962295962.32309785539296.401438385
2295238.61613169539820.900565182
#Sta/Elev= 30
       0 2699.09    77.2 2678.99   159.6  2665.1   244.1 2632.95   301.6 2625.22
   327.2 2618.75  382.48 2584.01   395.1 2580.59     526 2580.59  536.86  2583.8
   717.9  2586.4   733.3  2581.2   759.6 2580.09   789.2 2585.26   827.3 2584.02
   846.9 2587.21   889.2  2584.6  1054.6 2587.14    1144 2584.47  1188.9 2579.15
  1223.5 2584.72  1243.3 2582.65  1278.6 2590.04  1307.5 2590.15  1327.3 2608.59
  1332.2 2609.72  1603.9 2610.42  1732.4  2621.1  1791.3 2630.19    1838 2649.77
#Mann= 10 ,-1,0
       0      .1       0  382.48    .035       0  536.86    .025       0
     620      .1       0     760     .05       0 1004.23      .1       0
 1094.23     .08       0 1134.23      .1       0 1374.23     .05       0
 1734.23      .1       0
Bank Sta=382.48,536.86
XS Rating Curve= 0 ,0
Exp/Cntr=0.3,0.1

Type RM Length L Ch R = 1 ,311991  ,1064.9,1069.8,1031.6
XS GIS Cut Line= 2
2296514.46579467538260.8389862742294786.40876256539294.015941977
#Sta/Elev= 30
       0 2672.19    54.4 2657.23   124.4 2642.32   133.2 2639.03   175.1 2615.42
   212.4 2601.21   300.9 2583.49   515.3  2583.9     629 2581.97   664.4 2583.07
   690.2 2580.96   701.9 2578.62   850.9 2578.62   856.5 2580.82   862.3 2584.78
     874 2585.53  1083.5 2582.91  1326.1 2584.62  1352.3 2578.15  1382.2 2577.75
  1388.1 2578.55    1399 2585.49  1410.1 2586.88  1427.1 2583.25    1522 2583.26
  1577.9 2585.26  1772.3 2584.64  1804.4 2589.22  1926.9 2648.59  2013.4 2702.17
#Mann= 7 ,-1,0
       0      .1       0     660    .025       0   690.2    .035       0
   856.5     .05       0    1420     .07       0    1510     .05       0
    1810      .1       0
#XS Ineff= 2 , 0
                         1404.23          2600.4
Permanent Ineff=
       F       F
Bank Sta=690.2,856.5
XS Rating Curve= 0 ,0
Exp/Cntr(USF)=0,0
Exp/Cntr=0.3,0.1

Type RM Length L Ch R = 1 ,310921  ,543.4,486.6,435.4
XS GIS Cut Line= 4
2296066.45100857537346.5230962722295965.87626067537588.816807122
2295513.28989512538109.9768644242294525.82873391538974.005380476
#Sta/Elev= 30
       0 2611.94   206.4 2602.31   273.4 2601.88     284 2600.12   306.3 2590.38
   321.1 2584.73   342.3 2583.14   363.5 2578.13   501.2  2578.1   527.7 2577.07
   564.4 2581.39   707.8 2581.26  1363.3 2581.44  1379.3 2580.26  1389.9 2575.28
  1453.7 2575.28  1496.2 2580.76  1586.6 2580.54  1639.7 2585.51  1655.8 2583.25
  1728.9 2584.38    2049  2584.4  2123.4 2611.23  2168.9 2629.85  2171.2 2631.48
  2181.8 2650.54  2197.2 2660.12  2228.4 2675.68  2256.3 2684.55  2264.7 2687.87
#Mann= 9 ,-1,0
       0     .05       0   306.3     .07       0   363.5    .035       0
   501.2     .08       0   564.4     .06       0   707.8     .05       0
  1728.9     .08       0  2123.4      .1       0  2256.3     .07       0
#XS Ineff= 2 , 0
                         1632.39         2596.23
Permanent Ineff=
       F       F
Bank Sta=363.5,501.2
XS Rating Curve= 0 ,0
Exp/Cntr(USF)=0,0
Exp/Cntr=0.3,0.1

Type RM Length L Ch R = 1 ,310434  ,617,679.2,694.4
XS GIS Cut Line= 5
2295943.01836342537232.2336100212295399.00040887537410.525208572
2295399.00040887537506.5283770222295403.57198832537680.248396123
2294571.54452841538434.559005375
#Sta/Elev= 30
       0 2610.95    47.4 2605.99   133.5 2600.78   623.1 2588.34   671.1  2581.8
   689.2 2576.18   834.4 2576.18   879.3 2578.09     927 2577.88   952.9 2575.94
   974.7 2578.18  1028.3 2577.39  1171.2 2579.49  1246.4 2576.95  1284.2 2578.37
  1309.8 2574.44  1321.1 2575.15  1332.8 2578.23  1386.8 2579.96  1403.2  2578.1
  1421.3 2578.97  1435.4 2575.27  1451.6 2575.09  1486.8 2578.69  1552.4 2578.24
  1651.3 2582.39    1692 2585.65    1743 2586.18  1772.7  2589.4  1965.3 2594.44
#Mann= 13 ,-1,0
       0      .1       0      40     .05       0     350     .08       0
     450      .1       0     550     .08       0  678.49    .025       0
   689.2    .035       0   834.4      .1       0  892.27     .08       0
 1042.27     .05       0 1092.27     .08       0 1352.27     .07       0
 1752.27     .08       0
Bank Sta=689.2,834.4
XS Rating Curve= 0 ,0
Exp/Cntr(USF)=0,0
Exp/Cntr=0.3,0.1

Type RM Length L Ch R = 1 ,309755  ,511.5,506.7,508.3
XS GIS Cut Line= 4
2295189.72455577536852.9634973632294871.09577273 537471.47819385
2294466.78530013538063.217362352 2294140.1238587538309.552219827
#Sta/Elev= 30
       0 2640.63    39.9 2632.55   134.9 2603.05   185.4 2579.37   216.2 2575.89
   441.2 2576.88   457.6 2572.49   490.7 2575.26   517.7  2573.4   535.7 2576.33
   645.7 2572.59     725 2576.07     844 2573.72  971.78 2573.69   978.8    2577
  1053.1 2574.42    1129 2576.77  1172.6 2570.82  1187.1 2574.45  1228.7 2576.34
  1251.7 2586.36  1313.1 2583.85  1324.9 2588.03  1525.9 2597.54  1641.6 2597.52
  1681.2 2603.37  1711.3 2612.12  1747.9 2629.64  1811.5 2670.33  1821.6 2682.86
#Mann= 9 ,-1,0
       0      .1       0     300     .08       0     360      .1       0
     530     .08       0  765.76      .1       0     844    .035       0
  971.78     .08       0 1572.44     .06       0 1702.44      .1       0
Bank Sta=844,971.78
XS Rating Curve= 0 ,0
Exp/Cntr(USF)=0,0
Exp/Cntr=0.3,0.1

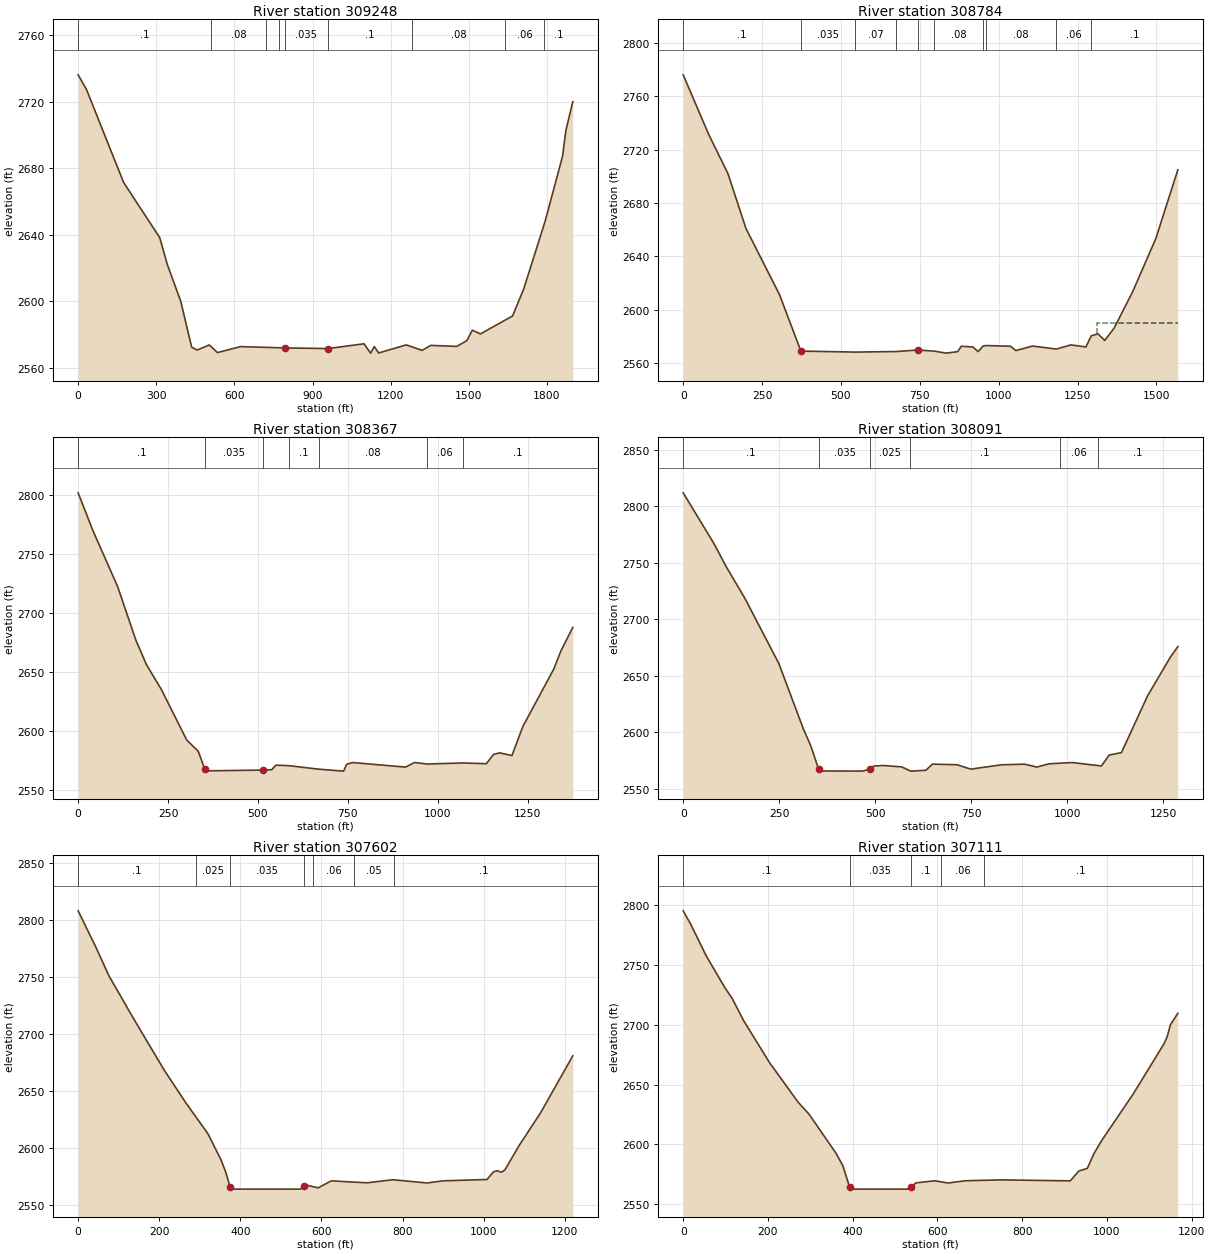
Type RM Length L Ch R = 1 ,309248  ,505.9,464.1,396.3
XS GIS Cut Line= 2
2295090.65510222536534.3347143242293875.04613163537993.600989587
#Sta/Elev= 30
       0  2736.2    32.2 2727.32   174.2 2671.61   313.4 2638.27   342.1 2622.31
   394.2 2599.91   435.8 2572.48   456.6  2570.7   503.6  2573.8   534.9 2569.19
   623.2 2572.79  793.49 2572.01  958.44 2571.61  1097.5 2574.48    1123 2568.87
    1137 2572.85  1153.8 2568.96    1260 2573.82  1320.8 2570.53  1353.8 2573.52
  1453.8 2572.93  1492.6 2576.39  1513.5 2582.68  1544.7 2580.43  1668.1 2591.22
  1711.3 2607.64  1793.1  2648.2    1860 2687.28  1872.6 2702.62  1899.3 2720.04
#Mann= 9 ,-1,0
       0      .1       0     510     .08       0     720      .1       0
     770     .08       0  793.49    .035       0  958.44      .1       0
    1280     .08       0    1640     .06       0    1790      .1       0
Bank Sta=793.49,958.44
XS Rating Curve= 0 ,0
Exp/Cntr(USF)=0,0
Exp/Cntr=0.3,0.1

Type RM Length L Ch R = 1 ,308784  ,433.9,417.6,367.1
XS GIS Cut Line= 4
2294351.65052979536445.9754719682294223.12799546537099.298354839
2293987.50334917537367.0536347032293797.39710047537878.466219245
#Sta/Elev= 30
       0  2776.1    80.7 2731.51   141.8 2702.12   198.9 2661.02   305.5 2611.32
  373.052569.088   545.5 2568.34   674.9 2568.75   742.9 2569.87   796.2 2569.04
   833.5 2567.56   870.1 2568.68   881.8 2572.72   918.6 2572.17   934.8  2568.7
   950.7 2572.85   958.4 2573.23  1037.6 2572.75  1054.7 2569.47  1107.6 2572.88
  1182.7  2570.6    1229 2573.72  1276.6 2572.19  1293.6 2580.54    1315 2581.99
  1336.3 2577.09  1365.9 2586.19    1425 2613.64  1498.5 2653.51  1568.1 2704.95
#Mann= 10 ,-1,0
       0      .1       0  373.05    .035       0   545.5     .07       0
   674.9    .035       0   742.9      .1       0   796.2     .08       0
   950.7      .1       0   958.4     .08       0  1182.7     .06       0
  1293.6      .1       0
#XS Ineff= 2 , 0
       0                  1310.7       0    2590
Permanent Ineff=
       F       F
Bank Sta=373.05,742.9
XS Rating Curve= 0 ,0
Exp/Cntr(USF)=0,0
Exp/Cntr=0.3,0.1

Type RM Length L Ch R = 1 ,308367  ,276.6,275.4,276.5
XS GIS Cut Line= 3
2293872.36857883536451.3305775662293826.85018126537546.449672213
2293722.42562211537806.172293682
#Sta/Elev= 30
       0 2802.22    41.9  2769.6   109.6 2722.99   160.5 2677.47     190  2656.6
   231.5 2635.57   302.1 2592.68   334.1 2583.22   351.7 2568.49   358.2 2566.62
   515.5 2567.28   538.3 2567.58   550.3 2571.47   586.5 2570.99   670.1 2568.01
   738.5 2566.38   746.5 2572.03   762.5 2573.67   910.6 2569.78     936  2573.7
   970.6 2572.39  1070.8 2573.29  1135.4 2572.67  1155.1 2580.42  1172.3 2581.89
  1206.8 2579.59    1237 2604.16  1323.2 2652.96  1343.1 2668.38    1376 2688.17
#Mann= 7 ,-1,0
       0      .1       0   351.7    .035       0   515.5    .025       0
   586.5      .1       0   670.1     .08       0   970.6     .06       0
  1070.8      .1       0
Bank Sta=351.7,515.5
XS Rating Curve= 0 ,0
Exp/Cntr(USF)=0,0
Exp/Cntr=0.3,0.1

Type RM Length L Ch R = 1 ,308091  ,492.3,489.2,495.1
XS GIS Cut Line= 2
     2293592.535       536441.08 2293552.7274472537727.857944609
#Sta/Elev= 30
       0 2812.07    80.1 2767.08   112.2 2746.52   160.8 2718.49   248.9 2660.91
   312.2 2603.45   332.3 2587.78   352.3 2567.43   356.3 2565.66   466.3 2565.59
     487 2567.38   496.3 2570.05   520.3 2570.55   568.4 2569.35   592.4 2565.56
   631.6 2566.31   648.7 2571.74   712.4 2571.23   748.5 2567.34   828.5 2571.17
   888.5 2571.72   920.5 2569.15   952.6 2572.07  1012.6 2573.14  1088.6 2570.14
  1108.6 2579.82  1140.6 2581.95  1208.7 2632.27  1267.5 2666.28  1287.4 2675.87
#Mann= 6 ,-1,0
       0      .1       0   352.3    .035       0     487    .025       0
     590      .1       0     980     .06       0    1080      .1       0
Bank Sta=352.3,487
XS Rating Curve= 0 ,0
Exp/Cntr=0.3,0.1

Type RM Length L Ch R = 1 ,307602  ,487.6,491.7,497.5
XS GIS Cut Line= 2
     2293095.139      536441.1042293080.00752799537660.735124643
#Sta/Elev= 30
       0 2807.97    44.1 2775.81    76.1 2750.81   137.3 2713.06   212.1 2668.36
   264.4 2640.19   320.1 2612.45   352.1 2589.69   364.1 2578.67   374.4 2566.13
   376.1 2564.38   380.1 2563.92   548.1 2563.91   556.1 2566.25   556.1 2566.28
   560.1 2567.53   592.1 2565.08   624.1 2571.16   712.1 2569.45   776.1 2572.15
   860.1 2569.31   900.1 2571.19  1008.2 2572.37  1024.2 2579.12  1032.2    2580
  1044.2 2578.78  1052.2 2580.78  1088.2 2602.62  1140.2 2630.78  1219.7 2680.78
#Mann= 7 ,-1,0
       0      .1       0     290    .025       0   374.4    .035       0
   556.1      .1       0     580     .06       0     680     .05       0
     780      .1       0
Bank Sta=374.4,556.1
XS Rating Curve= 0 ,0
Exp/Cntr=0.3,0.1

Type RM Length L Ch R = 1 ,307111  ,489.6,488.1,486.7
XS GIS Cut Line= 3
2292747.48432786536452.7793137942292605.76536491536749.931978045
2292555.47799096537586.531017398
#Sta/Elev= 30
       0 2795.29    18.2 2783.81    53.6 2758.14    97.9 2731.31   115.7 2722.04
   142.3 2703.68   203.8 2668.37   270.8 2635.54   297.4 2625.13   360.5 2592.71
   376.5  2582.5   392.6  2564.5   396.6 2562.66   528.8 2562.66   536.8 2564.18
   548.9 2567.84   592.9 2569.64     625 2567.78   665.1 2569.65   749.6 2570.39
   913.5 2569.57   933.6 2577.82   953.6 2579.98   969.6 2592.54   987.7 2603.36
  1061.8 2642.09  1135.2 2684.49  1141.9 2689.76  1149.9 2700.07  1167.3 2709.66
#Mann= 5 ,-1,0
       0      .1       0   392.6    .035       0   536.8      .1       0
  609.22     .06       0  709.22      .1       0
Bank Sta=392.6,536.8
XS Rating Curve= 0 ,0
Exp/Cntr(USF)=0,0
Exp/Cntr=0.3,0.1

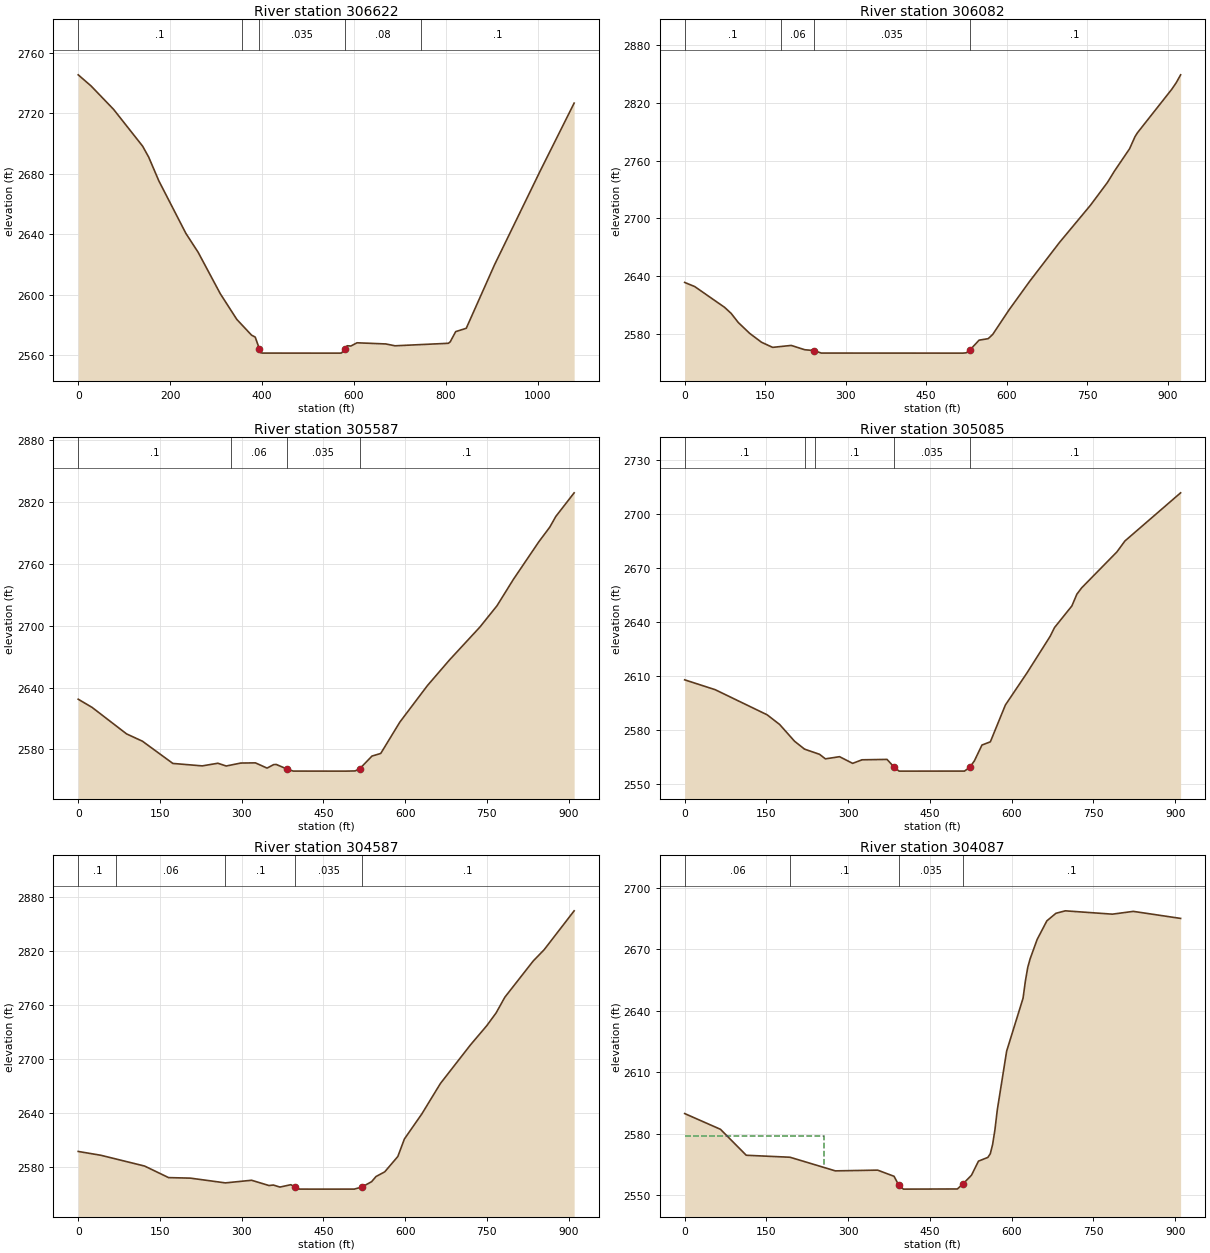
Type RM Length L Ch R = 1 ,306622  ,470.4,540.4,563
XS GIS Cut Line= 3
2292308.61270066536461.9224726942292121.17794321536635.642491795
2292084.60530761537458.526792797
#Sta/Elev= 30
       0 2745.39    27.9 2738.06      77 2722.56   140.1 2698.29   153.3 2691.07
   175.4 2675.38   234.3 2640.63   261.1 2628.08   309.1 2600.81   345.2 2583.77
   377.2 2573.39   385.2 2572.09   394.4 2564.27   397.2 2561.75   401.2 2561.52
   569.4  2561.5   573.4 2561.62     580 2564.55   585.4 2566.36   593.4  2566.2
   606.8 2568.33   669.5 2567.56   689.5 2566.34   805.6    2568   809.6 2568.97
   821.5 2575.71   844.5 2577.91   905.7 2619.66  1005.8 2682.11  1079.3  2726.7
#Mann= 5 ,-1,0
       0      .1       0  355.56     .06       0   394.4    .035       0
     580     .08       0  745.56      .1       0
Bank Sta=394.4,580
XS Rating Curve= 0 ,0
Exp/Cntr(USF)=0,0
Exp/Cntr=0.3,0.1

Type RM Length L Ch R = 1 ,306082  ,419.8,495.1,533.2
XS GIS Cut Line= 2
     2291742.677      536431.811     2291417.072      537296.635
#Sta/Elev= 30
       0 2633.56    18.6 2629.33    74.4 2607.72    86.6 2601.44    99.8 2592.04
   121.1 2580.73   143.3 2571.46   163.9  2566.2   198.6 2568.21   223.7 2563.74
   240.8 2562.88   254.5 2560.29   518.4 2560.22   524.7 2560.55   530.9  2563.1
   548.5 2573.64   565.6 2575.25   573.9 2579.56   604.1 2604.83   642.6 2634.57
   698.1 2674.86   756.4 2713.87   787.9 2737.43   800.7 2749.03     829 2772.26
   839.2 2784.92   843.5 2788.74   907.6 2833.99   915.9 2840.77   924.1 2848.98
#Mann= 4 ,-1,0
       0      .1       0     180     .06       0   240.8    .035       0
   530.9      .1       0
Bank Sta=240.8,530.9
XS Rating Curve= 0 ,0
Exp/Cntr=0.3,0.1

Type RM Length L Ch R = 1 ,305587  ,482,501.7,520.1
XS GIS Cut Line= 2
     2291543.217      536250.953     2290862.817      536855.235
#Sta/Elev= 30
       0 2628.79    25.5 2620.84    88.7 2595.14   117.8 2588.06   173.7 2566.46
   227.6 2564.09   256.3 2566.65   271.6 2563.97   298.3 2566.84   325.1 2567.02
   346.5 2561.95   358.7 2565.34   363.6 2565.44   382.8 2561.09   394.6 2559.03
   491.3    2559   508.1 2559.19   516.6 2561.32     539 2573.61   555.1 2576.16
   590.2  2606.6   640.7 2641.99   680.9 2666.68     737 2698.79   768.4 2719.48
   798.5 2745.11   845.2 2781.59   865.1 2795.66   876.4  2806.2     910  2829.1
#Mann= 4 ,-1,0
       0      .1       0     280     .06       0   382.8    .035       0
   516.6      .1       0
Bank Sta=382.8,516.6
XS Rating Curve= 0 ,0
Exp/Cntr=0.3,0.1

Type RM Length L Ch R = 1 ,305085  ,449.8,498.3,546.7
XS GIS Cut Line= 2
      2291300.18      535929.781      2290506.05      536374.155
#Sta/Elev= 30
       0 2607.93    56.1 2602.44   151.3 2588.51   174.2 2583.16   201.7  2573.8
     220 2569.44     220 2569.43   247.5 2566.57   258.2 2564.04   284.2 2565.25
   308.2 2561.54   325.4 2563.52   371.3 2563.74   383.8 2559.61   393.4 2557.23
   513.4 2557.25     523 2559.33   531.5 2562.89   545.5 2571.72   560.9 2573.51
   588.5 2593.97     628 2611.73   670.5 2632.04   678.6 2636.95   710.5 2648.98
   719.6 2655.48   728.4 2659.01   793.1 2678.97   807.8 2685.04     910 2711.78
#Mann= 5 ,-1,0
       0      .1       0     220     .06       0     240      .1       0
   383.8    .035       0     523      .1       0
Bank Sta=383.8,523
XS Rating Curve= 0 ,0
Exp/Cntr=0.3,0.1

Type RM Length L Ch R = 1 ,304587  ,474.5,500,526.5
XS GIS Cut Line= 2
     2291253.742      535700.522     2290345.181      535649.359
#Sta/Elev= 30
       0 2597.43    41.6 2593.18   121.8 2581.24   165.8 2568.42   205.9 2567.83
     270 2562.56   318.1 2565.47   350.1 2559.62   358.1 2560.18   370.2 2557.91
   390.2 2560.55   398.2 2557.79   406.2 2555.66   442.3 2555.64   506.4 2555.66
   520.3 2557.89   538.4 2563.92   546.4 2569.59   562.5 2574.84   586.5 2591.85
   598.5 2611.23   630.6 2639.14   664.6 2672.78   719.8 2715.63   749.6 2736.85
   766.8 2751.05   782.8 2768.44   834.9 2808.65   854.9 2821.11     910 2864.27
#Mann= 5 ,-1,0
       0      .1       0      70     .06       0     270      .1       0
   398.2    .035       0   520.3      .1       0
Bank Sta=398.2,520.3
XS Rating Curve= 0 ,0
Exp/Cntr=0.3,0.1

Type RM Length L Ch R = 1 ,304087  ,509.8,506.5,504.2
BEGIN DESCRIPTION:
c/e of 0.5/0.7 used to correct major drawdown in the 101 and 500 yr events
edits to banks and IFAs did not resolve the issue
END DESCRIPTION:
XS GIS Cut Line= 2
     2291361.207      535367.211     2290515.516      535031.197
#Sta/Elev= 30
       0 2589.82    65.7 2582.12     113 2569.44   193.3 2568.47   276.5 2561.81
   354.1 2562.17   384.2 2559.16   392.8 2554.82   401.4 2552.89   500.4 2552.97
   510.6 2555.45   526.2 2559.66   539.1 2566.57   556.3  2568.4   560.7 2570.14
     565 2574.66   569.3 2581.91   573.6 2591.57   590.8 2620.35   620.9  2646.2
   625.2 2654.65   629.5 2661.23   633.8 2665.38   646.7 2674.87   664.6    2684
   681.2 2687.68   698.4 2688.89   784.8 2687.26   823.2 2688.62     910 2685.18
#Mann= 4 ,-1,0
       0     .06       0   193.3      .1       0   392.8    .035       0
   510.6      .1       0
#XS Ineff= 2 , 0
          255.77 2578.99
Permanent Ineff=
       F       F
Bank Sta=392.8,510.6
XS Rating Curve= 0 ,0
Exp/Cntr=0.7,0.5

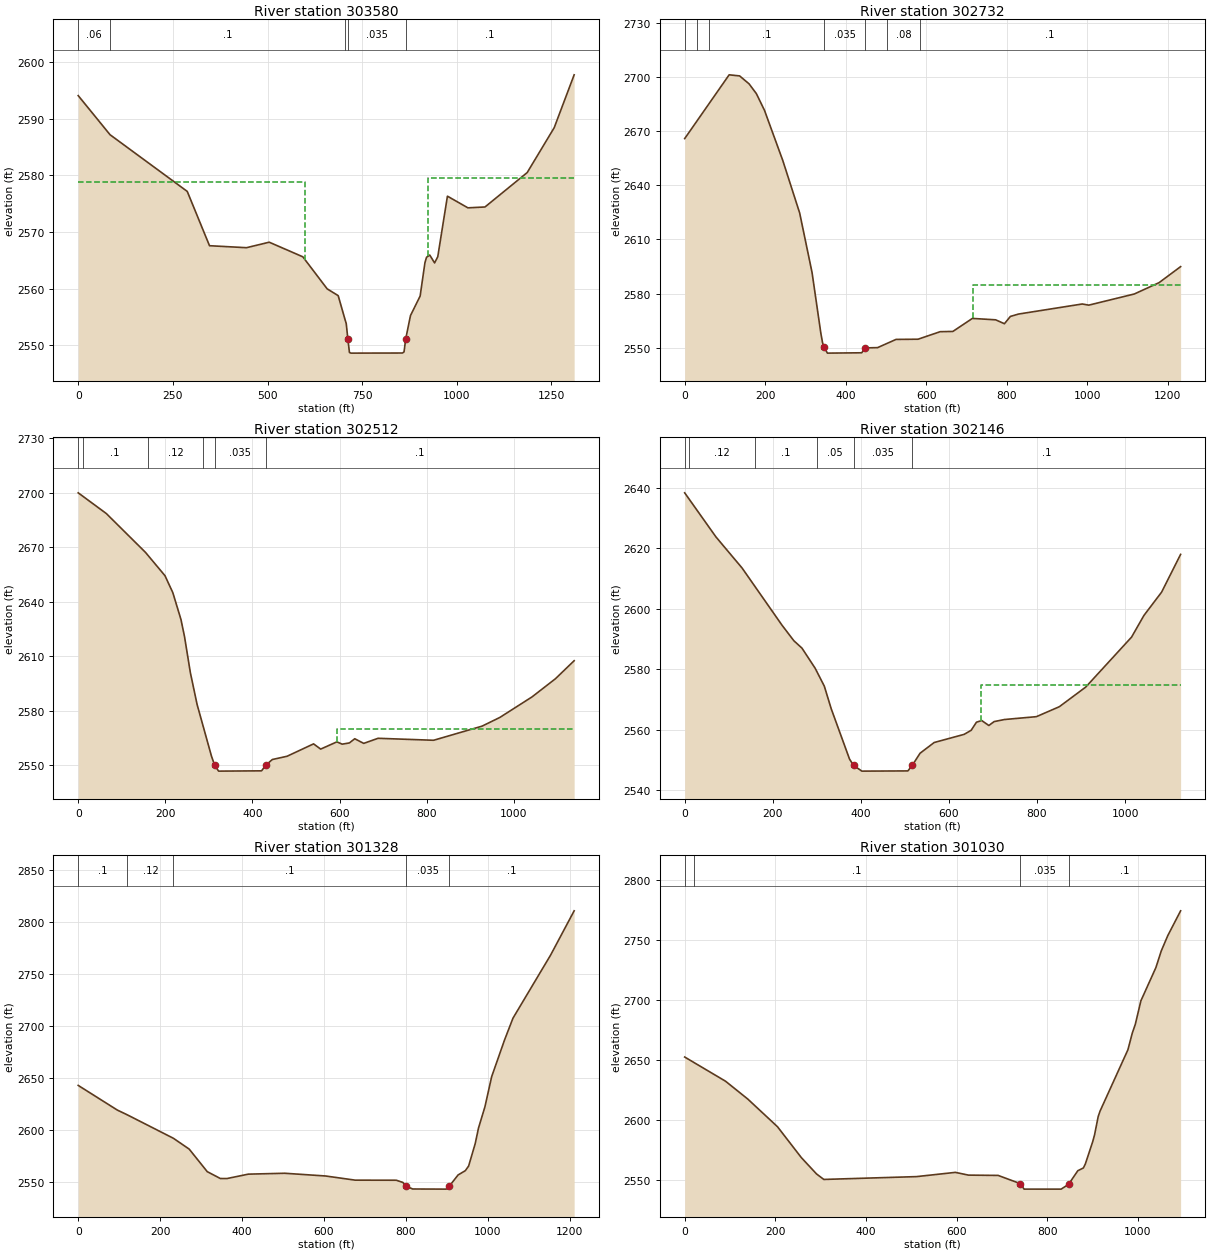
Type RM Length L Ch R = 1 ,303580  ,988,848.8,711.2
XS GIS Cut Line= 3
2291851.45475566 534985.30231034 2290895.9946506534647.005431039
2290662.84409865534829.868609039
#Sta/Elev= 30
       0 2594.07    84.1 2587.16     288 2577.15   346.8 2567.56   444.5 2567.21
   504.5 2568.18   593.3  2565.6   657.6 2559.94   686.7 2558.74   704.6 2554.55
   707.9 2553.82  712.22  2551.1   716.4  2548.7   720.6 2548.59   856.4 2548.61
   860.6  2548.8   864.9 2551.06   877.6 2555.22   903.1 2558.67   915.8 2564.56
     920 2565.52   928.5 2565.91   941.3 2564.52   949.7 2565.62   975.2 2576.31
  1029.2 2574.25  1074.4  2574.4  1185.9 2580.48  1257.2  2588.4  1309.9 2597.74
#Mann= 5 ,-1,0
       0     .06       0    84.1      .1       0   704.6    .025       0
  712.22    .035       0   864.9      .1       0
#XS Ineff= 2 , 0
          599.44 2578.74  923.61         2579.57
Permanent Ineff=
       F       F
Bank Sta=712.22,864.9
XS Rating Curve= 0 ,0
Exp/Cntr(USF)=0,0
Exp/Cntr=0.3,0.1

Type RM Length L Ch R = 1 ,302732  ,214.7,220,227.2
XS GIS Cut Line= 4
 2291106.2873053533728.117961586  2290950.853604533915.552719037
2290818.27779995534688.149646089 2290658.2725192534816.153870689
#Sta/Elev= 30
       0 2666.01   110.5 2701.42   136.5 2700.82     160 2696.41   178.1 2690.99
   198.3 2681.71   243.8 2653.84   285.7 2624.73   316.5 2591.67   338.5 2557.75
   342.6 2552.69   346.6 2550.07   354.7 2546.91     440  2547.1   448.1 2549.81
   479.3 2549.96   525.2 2554.53   579.8 2554.63   634.8 2558.81   666.4 2558.95
   714.9 2566.18   772.7  2565.4   794.5 2563.24   809.3 2567.28   829.2 2568.59
   987.8 2574.19  1004.1 2573.55  1117.2 2579.74  1178.6 2586.01  1232.3 2594.93
#Mann= 7 ,-1,0
       0      .1       0      30     .12       0      60      .1       0
   346.6    .035       0   448.1      .1       0   503.5     .08       0
   583.5      .1       0
#XS Ineff= 2 , 0
                          716.17            2585
Permanent Ineff=
       F       F
Bank Sta=346.6,448.1
XS Rating Curve= 0 ,0
Exp/Cntr(USF)=0,0
Exp/Cntr=0.3,0.1

Type RM Length L Ch R = 1 ,302512  ,386.4,365.3,346.4
XS GIS Cut Line= 3
 2290905.1378095533769.262176636 2290740.5609493533910.981139587
2290525.69671515534807.010711789
#Sta/Elev= 30
       0 2700.06    64.6 2688.63   154.4 2667.26   199.2 2654.41   217.2 2645.07
   235.9 2630.28   244.1 2620.79   257.5 2600.96   272.9 2583.49   305.8  2555.1
  313.26 2549.95   322.3 2546.72     421 2546.88  430.71 2550.04   445.7 2553.12
   479.4  2554.9   540.3 2561.73   556.7 2558.86   593.8 2562.84   606.1 2561.58
   622.6 2562.26   634.9 2564.56   655.5 2562.01   688.4 2564.81   815.9 2563.72
     927 2571.49   968.1 2576.31  1042.1 2587.65  1095.6 2597.62  1138.6 2607.55
#Mann= 6 ,-1,0
       0     .12       0      10      .1       0     160     .12       0
  287.19      .1       0  313.26    .035       0  430.71      .1       0
#XS Ineff= 2 , 0
                          594.73         2569.92
Permanent Ineff=
       F       F
Bank Sta=313.26,430.71
XS Rating Curve= 0 ,0
Exp/Cntr(USF)=0,0
Exp/Cntr=0.3,0.1

Type RM Length L Ch R = 1 ,302146  ,674.3,818.7,938
XS GIS Cut Line= 3
2290585.09223805533769.9102171172290336.88309361533991.611588846
2290368.21046136534784.434972525
#Sta/Elev= 30
       0 2638.32      71 2623.75   130.4 2613.46   221.1 2594.56   247.9 2589.44
   266.4 2586.98   296.2 2580.37   317.1 2574.42   332.8 2566.94   374.4  2550.3
   383.7 2548.22   402.4 2546.34   506.9 2546.41  517.15 2548.31   534.5 2552.25
   566.6  2555.8   634.6 2558.49   650.6 2559.84   662.6 2562.51   674.6 2563.06
   690.7 2561.42   702.7 2562.71   726.4  2563.4   798.7 2564.34   850.8 2567.63
   910.8 2574.13  1014.9 2590.65  1042.9  2597.8    1083 2605.49  1126.2 2617.98
#Mann= 6 ,-1,0
       0      .1       0      10     .12       0     160      .1       0
     300     .05       0   383.7    .035       0  517.15      .1       0
#XS Ineff= 2 , 0
                             672         2574.92
Permanent Ineff=
       F       F
Bank Sta=383.7,517.15
XS Rating Curve= 0 ,0
Exp/Cntr(USF)=0,0
Exp/Cntr=0.3,0.1

Type RM Length L Ch R = 1 ,301328  ,286.2,298.1,305.1
XS GIS Cut Line= 3
2290589.69882745533709.8316437862290388.54933165533837.835868387
2289419.37448825533760.119017736
#Sta/Elev= 30
       0 2643.26    95.6 2619.54   120.3 2614.89   232.4 2592.45   270.9 2582.06
     315 2560.39   347.1 2553.78   363.2 2553.76   415.4 2557.99   504.2 2558.84
     604 2556.21   676.2 2552.21   776.5 2552.14   792.6 2550.01   800.6  2546.4
   816.6 2543.72   896.9 2543.59   900.9 2543.86   905.6 2546.28   927.4 2557.22
   945.1 2561.35   953.1  2565.8   969.1 2587.23   977.2 2602.28   992.9 2622.72
  1009.3 2651.63  1040.8 2686.97  1061.4 2707.91  1153.3 2768.56  1210.7 2811.04
#Mann= 5 ,-1,0
       0      .1       0   120.3     .12       0   232.4      .1       0
   800.6    .035       0   905.6      .1       0
Bank Sta=800.6,905.6
XS Rating Curve= 0 ,0
Exp/Cntr(USF)=0,0
Exp/Cntr=0.3,0.1

Type RM Length L Ch R = 1 ,301030  ,348.1,362.9,376.7
XS GIS Cut Line= 2
2290616.41960579 533666.288923812289546.46950745533437.358159525
#Sta/Elev= 30
       0 2652.47    90.2 2632.35   139.3 2617.51   204.8 2594.52   257.2 2568.96
   290.9 2555.28     307 2550.71   511.6 2553.06   597.3 2556.59   626.1  2554.3
   691.6 2554.06   740.6 2547.21   748.8 2542.67   830.6 2542.66   847.1  2546.7
   867.4 2557.97   879.7 2560.26     884 2563.61   900.2 2582.05   904.3 2587.75
   912.4 2603.06   916.5 2607.56   977.9 2658.48   987.6 2672.38   994.3 2679.75
  1006.5 2699.13  1039.7 2726.87  1051.5 2740.66  1065.9 2753.39  1094.2 2773.99
#Mann= 4 ,-1,0
       0     .12       0      20      .1       0   740.6    .035       0
   847.1      .1       0
Bank Sta=740.6,847.1
XS Rating Curve= 0 ,0
Exp/Cntr(USF)=0,0
Exp/Cntr=0.3,0.1

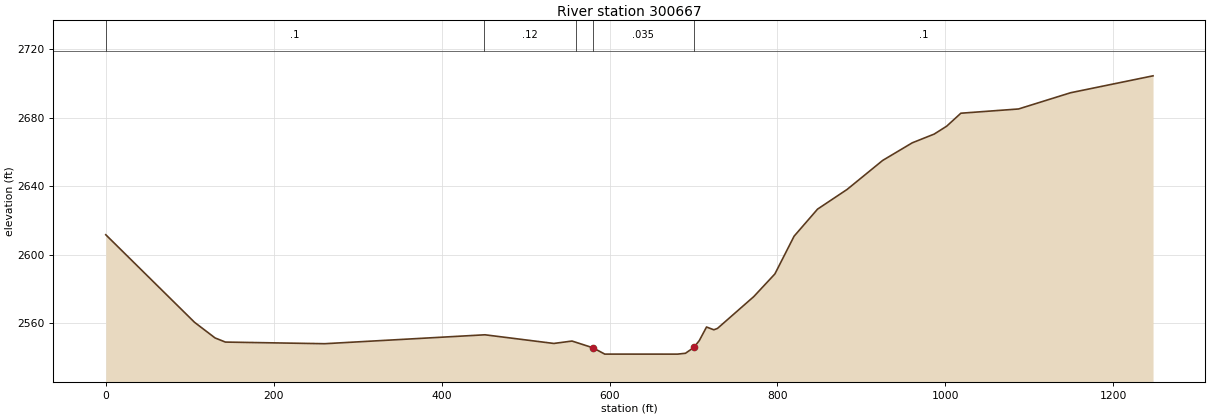
Type RM Length L Ch R = 1 ,300667  ,222.8,240.7,255.2
XS GIS Cut Line= 3
 2290521.1251357533394.392661735 2289771.3861059533083.525259134
 2289387.3734321533289.246334385
#Sta/Elev= 30
       0 2611.71   105.7 2560.63   130.2 2551.49   142.5 2549.09   260.8 2548.14
   451.6 2553.34   533.6 2548.29   555.3 2549.69   580.2 2545.76   594.3 2542.07
   680.9 2542.06   690.4 2542.55   700.4 2545.96   706.9 2549.98   715.5 2557.88
   724.2 2556.26   728.5 2557.05   771.8 2575.64   796.9 2588.84   819.8 2610.88
   847.7 2626.65   882.9 2638.15   925.3 2655.08   960.5 2665.35   986.6 2670.44
  1001.5 2675.05  1018.4 2682.62  1087.1  2685.1  1149.1 2694.57  1247.3 2704.44
#Mann= 5 ,-1,0
       0      .1       0     450     .12       0     560      .1       0
   580.2    .035       0   700.4      .1       0
Bank Sta=580.2,700.4
XS Rating Curve= 0 ,0
Exp/Cntr(USF)=0,0
Exp/Cntr=0.3,0.1