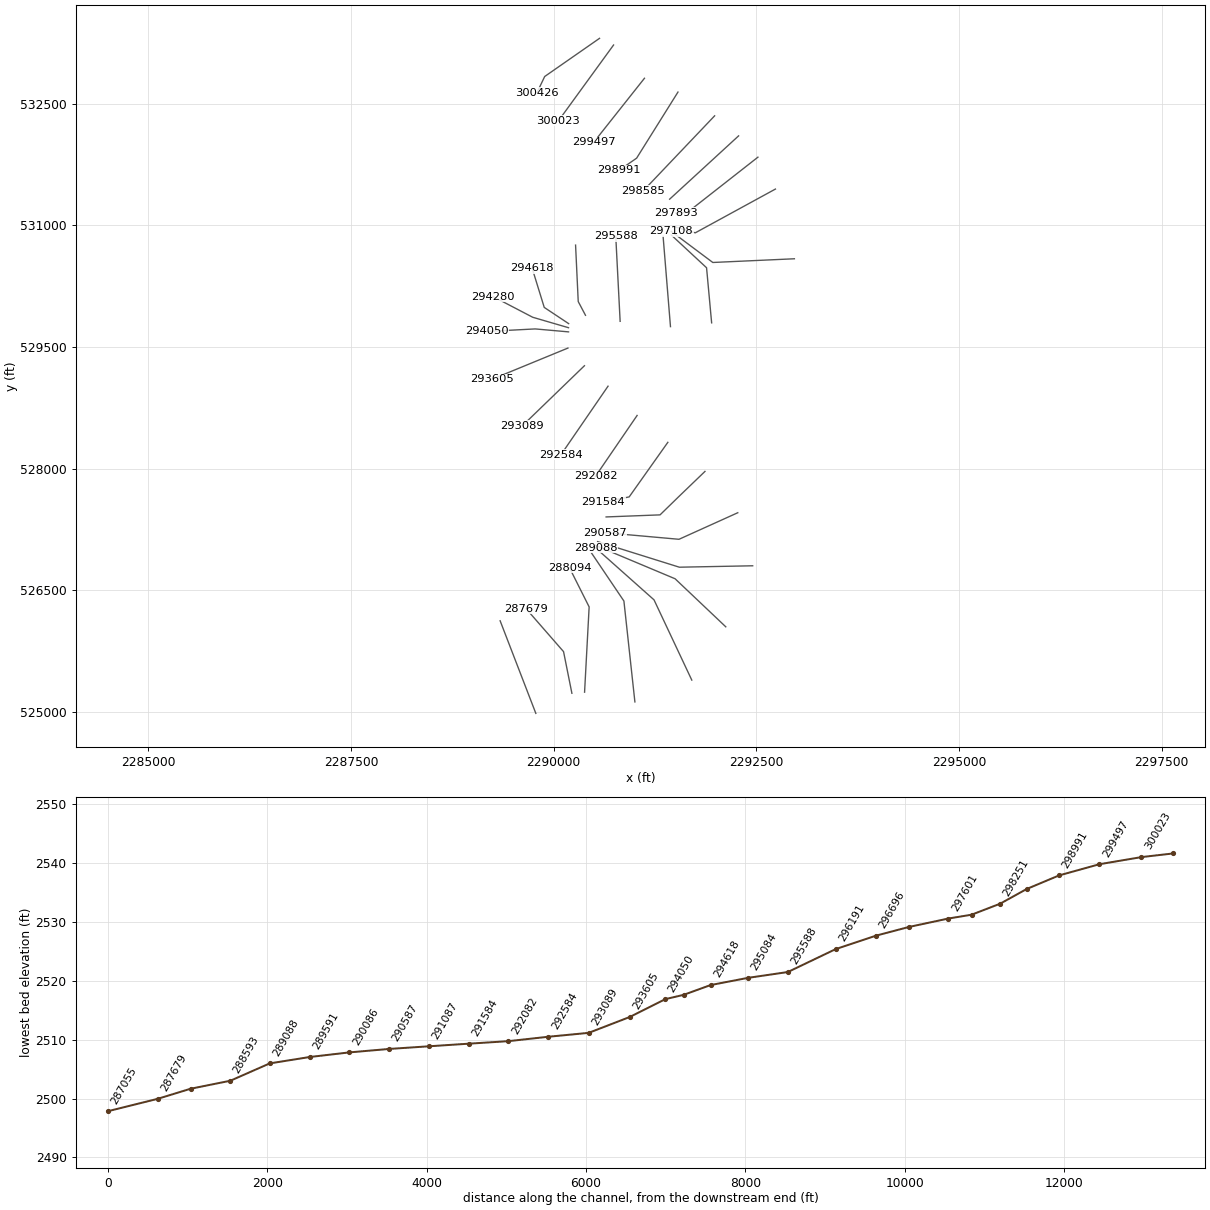
HEC-RAS study GRNBRRRV.prj: GRNBRRRV

--- GRNBRRRV.g01 (geometry) --- (continued)

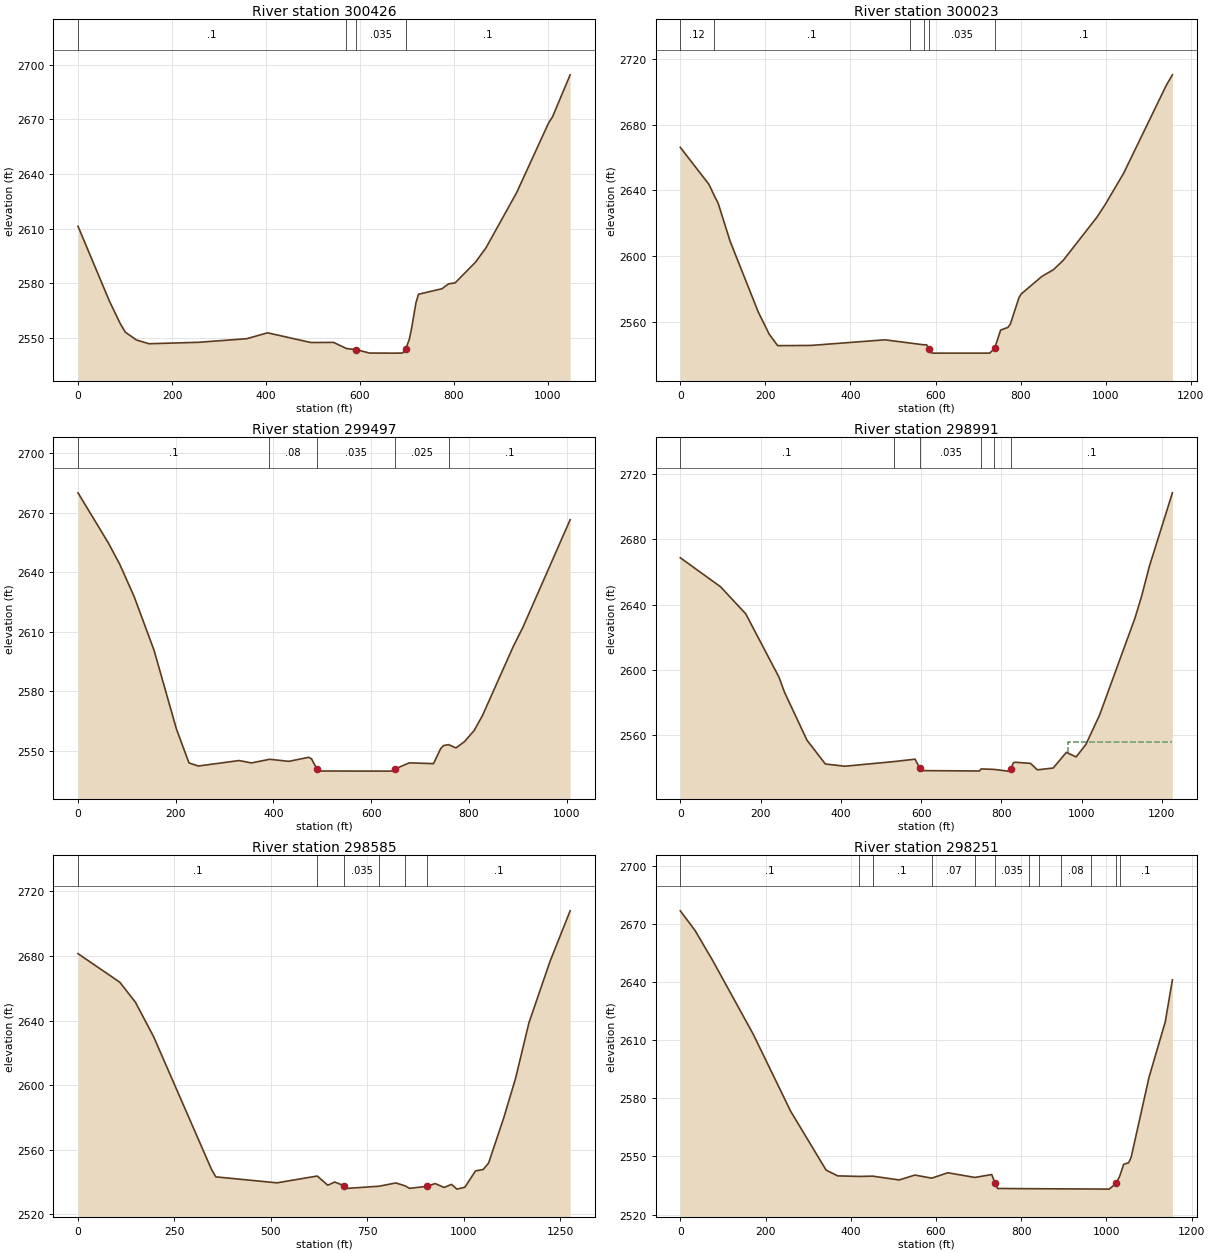
Type RM Length L Ch R = 1 ,300426  ,376.6,403,426.6
XS GIS Cut Line= 3
 2290566.8409302533307.532652185 2289890.2471716532836.659968834
2289794.24400315532635.510473033
#Sta/Elev= 30
       0 2611.28    67.1 2570.04    89.8  2557.9   100.7 2553.15   124.3 2548.88
   151.2 2546.81   256.5  2547.6     359 2549.57   403.3 2552.81   495.5 2547.48
   543.8 2547.55   571.3 2544.17   592.3 2543.57   620.3  2541.7   675.8 2541.66
   690.5  2541.7   697.4 2543.88     705 2549.31   709.9 2555.38   719.1 2569.28
   724.5 2573.96   774.4 2576.99   788.4 2579.64   802.5 2580.23   845.9  2591.6
   868.1 2599.44   933.5 2629.82    1001 2667.81  1009.9 2671.46  1047.2 2694.39
#Mann= 4 ,-1,0
       0      .1       0     570    .025       0   592.3    .035       0
   697.4      .1       0
Bank Sta=592.3,697.4
XS Rating Curve= 0 ,0
Exp/Cntr(USF)=0,0
Exp/Cntr=0.3,0.1

Type RM Length L Ch R = 1 ,300023  ,530.2,526,522.1
XS GIS Cut Line= 2
2290739.95881391533225.1350660142290059.63177271532289.843264512
#Sta/Elev= 30
       0 2666.21    67.6  2643.6      80 2636.76      89  2632.2   117.2 2609.03
   183.2 2566.08   208.8 2552.64   228.9 2545.58   306.6  2545.7   480.9 2549.13
   572.5 2546.08   578.7 2546.13   584.4 2543.69   588.6 2541.46   593.5 2541.03
   727.2 2541.03   738.6 2543.87   752.9 2555.03   770.1 2556.71   775.8 2558.75
   795.8 2574.65   801.2    2577   849.6 2587.66   876.8 2591.75   900.2 2597.53
   979.3 2623.75   999.2 2631.65  1042.1 2650.52  1142.5 2704.09  1156.6 2710.32
#Mann= 6 ,-1,0
       0     .12       0      80      .1       0     540    .025       0
   572.5      .1       0   584.4    .035       0   738.6      .1       0
Bank Sta=584.4,738.6
XS Rating Curve= 0 ,0
Exp/Cntr=0.3,0.1

Type RM Length L Ch R = 1 ,299497  ,495.7,505.7,526.2
XS GIS Cut Line= 2
2291121.26806321532815.1728955922290495.53769266532026.027026214
#Sta/Elev= 30
       0 2679.91      62 2654.71    85.5  2643.9   114.9 2627.65   155.7 2600.58
   201.3 2561.09   227.1 2543.94   246.4  2542.4   329.6 2545.15   354.8 2543.95
   392.3 2545.78   431.4 2544.74     472 2546.78   477.7 2546.04   489.1 2540.81
   492.6 2539.88   640.7 2539.82   648.5 2540.86   677.8 2543.99   727.4 2543.58
   742.1 2551.13   747.9 2552.69   758.1 2553.17   773.4  2551.5   790.9 2554.67
   810.8  2560.3   827.9 2567.91   890.5 2602.46   910.5 2612.28  1007.1 2666.36
#Mann= 5 ,-1,0
       0      .1       0     390     .08       0   489.1    .035       0
   648.5    .025       0     760      .1       0
Bank Sta=489.1,648.5
XS Rating Curve= 0 ,0
Exp/Cntr=0.3,0.1

Type RM Length L Ch R = 1 ,298991  ,414.5,406.7,360.7
XS GIS Cut Line= 3
2291534.62225315532644.8078523162291024.59881485531829.818008189
2290807.35090917531678.674479399
#Sta/Elev= 30
       0 2668.67   100.2 2650.91     163 2634.32   245.9 2595.51   259.8 2586.18
   315.7 2556.86   361.4 2542.29   410.1 2540.92   532.8 2543.78   584.9 2545.25
   596.4 2539.86   602.3 2538.23   745.1 2538.01   749.8 2539.28   782.2 2538.97
   815.9 2537.92   823.4 2539.51   830.1 2543.04   834.5 2543.37   872.5 2542.66
   889.6 2538.71   929.1 2539.82   961.9 2549.43   986.3 2546.62  1010.7 2554.33
  1044.8 2572.39  1132.5 2631.46    1149  2644.8  1169.1 2663.76  1226.1 2708.45
#Mann= 6 ,-1,0
       0      .1       0   532.8     .08       0   596.4    .035       0
   749.8     .08       0   782.2    .035       0   823.4      .1       0
#XS Ineff= 2 , 0
       0                   966.8       0    2556
Permanent Ineff=
       F       F
Bank Sta=596.4,823.4
XS Rating Curve= 0 ,0
Exp/Cntr=0.3,0.1

Type RM Length L Ch R = 1 ,298585  ,337.5,333.4,326.8
XS GIS Cut Line= 2
2291986.90821887532351.7663717282291106.79244218 531427.44768188
#Sta/Elev= 30
       0 2681.39   108.4  2663.7     149 2651.29   196.2 2629.91     346 2547.92
   357.4  2543.2   515.9  2539.5   620.5 2543.72   647.8 2538.04   665.8    2540
   688.8 2537.82   699.5 2536.09   781.3 2537.43   824.3 2539.44   848.6 2537.61
   859.7 2536.08   906.3 2537.41   926.1 2539.06   949.5 2536.66   968.5 2538.55
   982.7 2535.61  1003.3  2536.8  1030.9  2546.9  1050.6 2547.74  1064.7  2551.7
  1104.4 2579.97  1135.1  2604.5  1169.4 2638.57  1224.2 2676.69  1276.3 2707.91
#Mann= 6 ,-1,0
       0      .1       0   620.5     .08       0   688.8    .035       0
   781.3     .08       0   848.6    .035       0   906.3      .1       0
Bank Sta=688.8,906.3
XS Rating Curve= 0 ,0
Exp/Cntr=0.3,0.1

Type RM Length L Ch R = 1 ,298251  ,344.2,358.1,274.9
XS GIS Cut Line= 2
2292282.51311966532104.5349253322291431.85459552531323.760529244
#Sta/Elev= 30
       0 2676.69    34.5 2666.61    75.9 2651.09   171.1 2613.06   258.8 2573.36
   342.1 2542.94   369.2 2539.95   420.2 2539.66   451.3 2539.81   513.7 2537.85
   550.4 2540.35   590.1 2538.77   627.6 2541.56   691.2 2539.15   730.7 2540.64
   738.5 2536.22   744.4 2533.45   817.6 2533.33   842.4 2533.31   893.6 2533.24
   963.7 2533.18  1006.2 2533.11  1023.2 2536.14  1031.7 2540.15  1040.2 2545.88
    1052 2546.73  1057.9 2549.55  1099.9 2590.88  1137.9  2619.4  1154.7 2641.12
#Mann= 12 ,-1,0
       0      .1       0   420.2     .08       0   451.3      .1       0
   590.1     .07       0   691.2     .08       0   738.5    .035       0
   817.6     .08       0   842.4      .1       0   893.6     .08       0
   963.7    .035       0  1023.2     .08       0  1031.7      .1       0
Bank Sta=738.5,1023.2
XS Rating Curve= 0 ,0
Exp/Cntr(USF)=0,0
Exp/Cntr=0.3,0.1

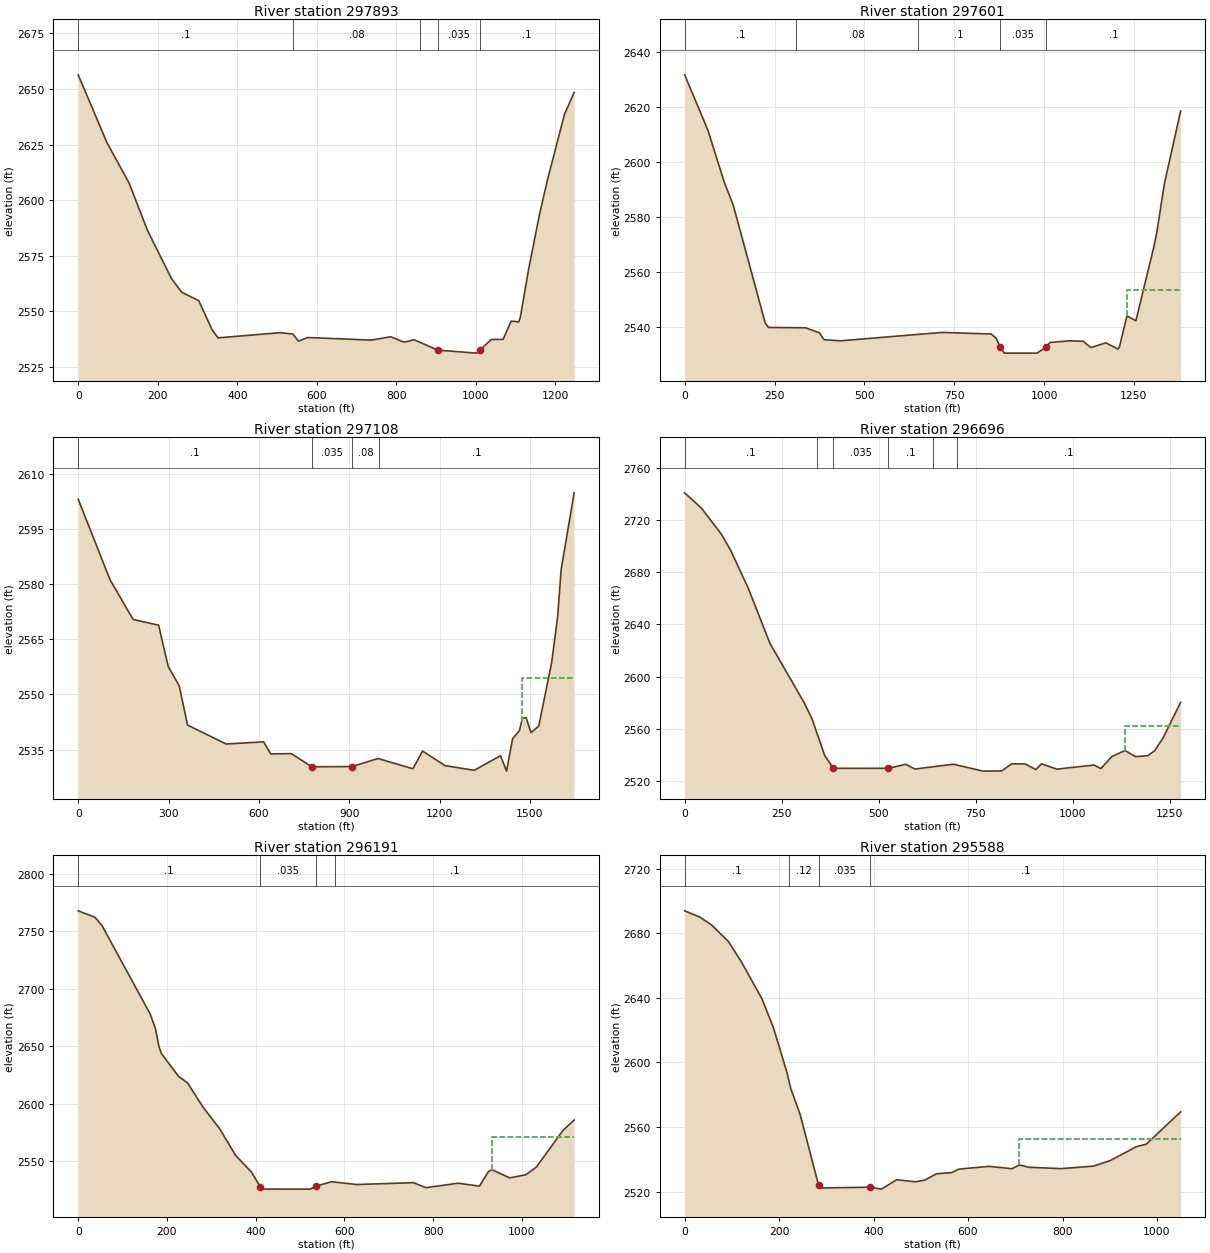
Type RM Length L Ch R = 1 ,297893  ,304.5,291.7,279.8
XS GIS Cut Line= 3
2292521.08307402531841.8669957842291653.55596725531162.304095485
2291508.96811612 531152.66490541
#Sta/Elev= 30
       0 2656.32    72.3 2625.85   128.2 2607.56   173.9  2586.5   234.6  2564.7
   260.4 2558.61   303.2 2554.78   336.5 2541.76   351.6  2538.1   508.3 2540.44
   539.8  2539.8   553.9 2536.62   576.7 2538.26   736.2 2537.09     786 2538.59
   819.2 2536.17   844.6 2537.24   904.3 2532.58  1002.1 2531.24  1009.7 2532.59
  1038.3 2537.36  1068.2 2537.42  1088.5 2545.64  1107.4  2545.3  1111.4 2547.18
  1132.3 2568.81  1159.5  2593.3    1179 2608.54  1222.5 2638.52  1246.9  2648.4
#Mann= 5 ,-1,0
       0      .1       0     540     .08       0     860      .1       0
   904.3    .035       0  1009.7      .1       0
Bank Sta=904.3,1009.7
XS Rating Curve= 0 ,0
Exp/Cntr(USF)=0,0
Exp/Cntr=0.3,0.1

Type RM Length L Ch R = 1 ,297601  ,542.6,493.8,464.9
XS GIS Cut Line= 3
2292736.81176827531448.4383469162291747.96378113 530908.63068188
2291504.90653301530980.637710677
#Sta/Elev= 30
       0 2631.82    64.5 2611.72   110.1  2592.8   135.5 2584.27     224 2541.61
   233.1 2539.94     336  2539.8   374.3 2538.03   388.1 2535.47   433.7 2535.07
   716.2 2538.12   852.9 2537.55   866.7 2536.05  877.93 2532.82   889.4 2530.59
   980.5 2530.59  1005.2 2532.71  1016.9 2534.47    1070 2535.06  1108.8 2534.91
  1130.5  2532.6  1171.9 2534.34  1205.6  2532.1  1209.8 2532.82  1230.7 2544.13
  1255.7 2542.37  1305.8 2569.34  1314.1 2574.71    1335 2592.21  1380.1 2618.65
#Mann= 5 ,-1,0
       0      .1       0     310     .08       0     650      .1       0
  877.93    .035       0  1005.2      .1       0
#XS Ineff= 2 , 0
                         1231.21         2553.47
Permanent Ineff=
       F       F
Bank Sta=877.93,1005.2
XS Rating Curve= 0 ,0
Exp/Cntr=0.3,0.1

Type RM Length L Ch R = 1 ,297108  ,562.2,411.2,293.8
XS GIS Cut Line= 3
2292970.89773105530588.7277727072291964.41984718530542.986133156
2291452.42680992530925.918041203
#Sta/Elev= 30
       0 2603.03   105.6 2581.17   182.2 2570.37     267 2568.81     299 2557.54
   335.1  2552.4   363.1 2541.69   491.2 2536.53   615.8 2537.11   639.4 2533.83
   707.5 2533.92   775.8 2530.35   909.4  2530.4   995.7 2532.59  1111.4  2529.8
  1143.6 2534.61  1218.2 2530.66    1315 2529.38  1402.4 2533.36  1422.4 2529.16
  1442.4 2537.94  1465.3 2540.18  1475.1 2543.55  1487.3 2543.68  1503.6 2539.62
  1529.4 2541.41  1572.3 2558.71  1592.2 2571.21  1603.7 2583.89  1646.9 2604.77
#Mann= 4 ,-1,0
       0      .1       0   775.8    .035       0   909.4     .08       0
    1000      .1       0
#XS Ineff= 2 , 0
                         1472.45         2554.42
Permanent Ineff=
       F       F
Bank Sta=775.8,909.4
XS Rating Curve= 0 ,0
Exp/Cntr=0.3,0.1

Type RM Length L Ch R = 1 ,296696  ,507.1,505.5,504.6
XS GIS Cut Line= 3
2291949.96106206 529798.358699852291887.30632657530477.921600149
2291451.13297567530882.767583305
#Sta/Elev= 30
       0 2740.68      43 2729.03    95.2 2708.79   119.3 2696.13   163.5 2667.86
   219.7 2625.44   308.1 2579.93   328.2 2567.58   360.3 2539.91   383.1 2529.85
     525 2529.86   569.2 2532.94   593.3 2529.28   692.2 2532.99   768.6 2527.69
   816.6 2527.86   842.6 2533.27   876.6 2533.17   904.8 2528.92   919.1 2533.27
   958.7 2529.21  1054.9 2532.36  1071.9 2529.56  1100.2 2538.82  1134.2  2543.5
  1161.5 2538.76  1192.9 2539.48  1210.6 2543.32  1232.5 2553.19  1277.5 2580.32
#Mann= 6 ,-1,0
       0      .1       0     340    .025       0   383.1    .035       0
     525      .1       0     640     .08       0  702.45      .1       0
#XS Ineff= 2 , 0
                         1134.99          2562.5
Permanent Ineff=
       F       F
Bank Sta=383.1,525
XS Rating Curve= 0 ,0
Exp/Cntr(USF)=0,0
Exp/Cntr=0.3,0.1

Type RM Length L Ch R = 1 ,296191  ,605.9,603,602
XS GIS Cut Line= 2
2291442.12388835529751.6912024812291351.02430571530865.936789097
#Sta/Elev= 30
       0 2767.86    37.6 2762.31    53.7 2754.97     162 2678.16   174.1 2665.27
   182.1 2649.53   187.4 2643.62   226.2 2623.63   246.3 2618.01   281.4 2596.83
   318.6 2578.18   354.7 2554.86   390.8 2540.08   410.3 2527.64   414.9 2525.44
   523.2 2525.41   535.3 2527.92   571.4 2531.87   627.6 2529.42     756 2531.04
   784.1 2526.67   856.5 2530.56   904.5 2528.02   924.6 2540.57   932.6 2542.37
   972.7 2535.21  1008.8 2537.88  1032.9 2544.65  1093.1 2576.74    1118 2585.62
#Mann= 4 ,-1,0
       0      .1       0   410.3    .035       0   535.3    .025       0
     580      .1       0
#XS Ineff= 2 , 0
                          933.63         2570.48
Permanent Ineff=
       F       F
Bank Sta=410.3,535.3
XS Rating Curve= 0 ,0
Exp/Cntr=0.3,0.1

Type RM Length L Ch R = 1 ,295588  ,499.9,503.5,504.2
XS GIS Cut Line= 2
2290821.11920248529817.0855081952290767.07101241530865.769764285
#Sta/Elev= 30
       0 2693.89    32.1 2690.01    56.2  2685.3    92.2 2675.03   119.1 2662.81
   163.8 2639.31   188.3 2621.18   216.4 2593.91   224.4 2584.06   244.8 2567.44
  283.47 2523.97   288.5 2522.22   393.3 2522.69   416.6  2521.5   448.7 2527.29
     489 2526.02   508.8 2527.16   532.8 2530.96   564.8 2531.75   580.9 2533.91
   644.9  2535.6     693 2534.13     709 2536.49   729.1 2535.03   797.1 2534.19
   865.6 2535.75   901.3 2539.22   957.7 2547.97   977.4  2549.3  1050.1 2569.38
#Mann= 4 ,-1,0
       0      .1       0     220     .12       0  283.47    .035       0
   393.3      .1       0
#XS Ineff= 2 , 0
                          707.15         2552.56
Permanent Ineff=
       F       F
Bank Sta=283.47,393.3
XS Rating Curve= 0 ,0
Exp/Cntr=0.3,0.1

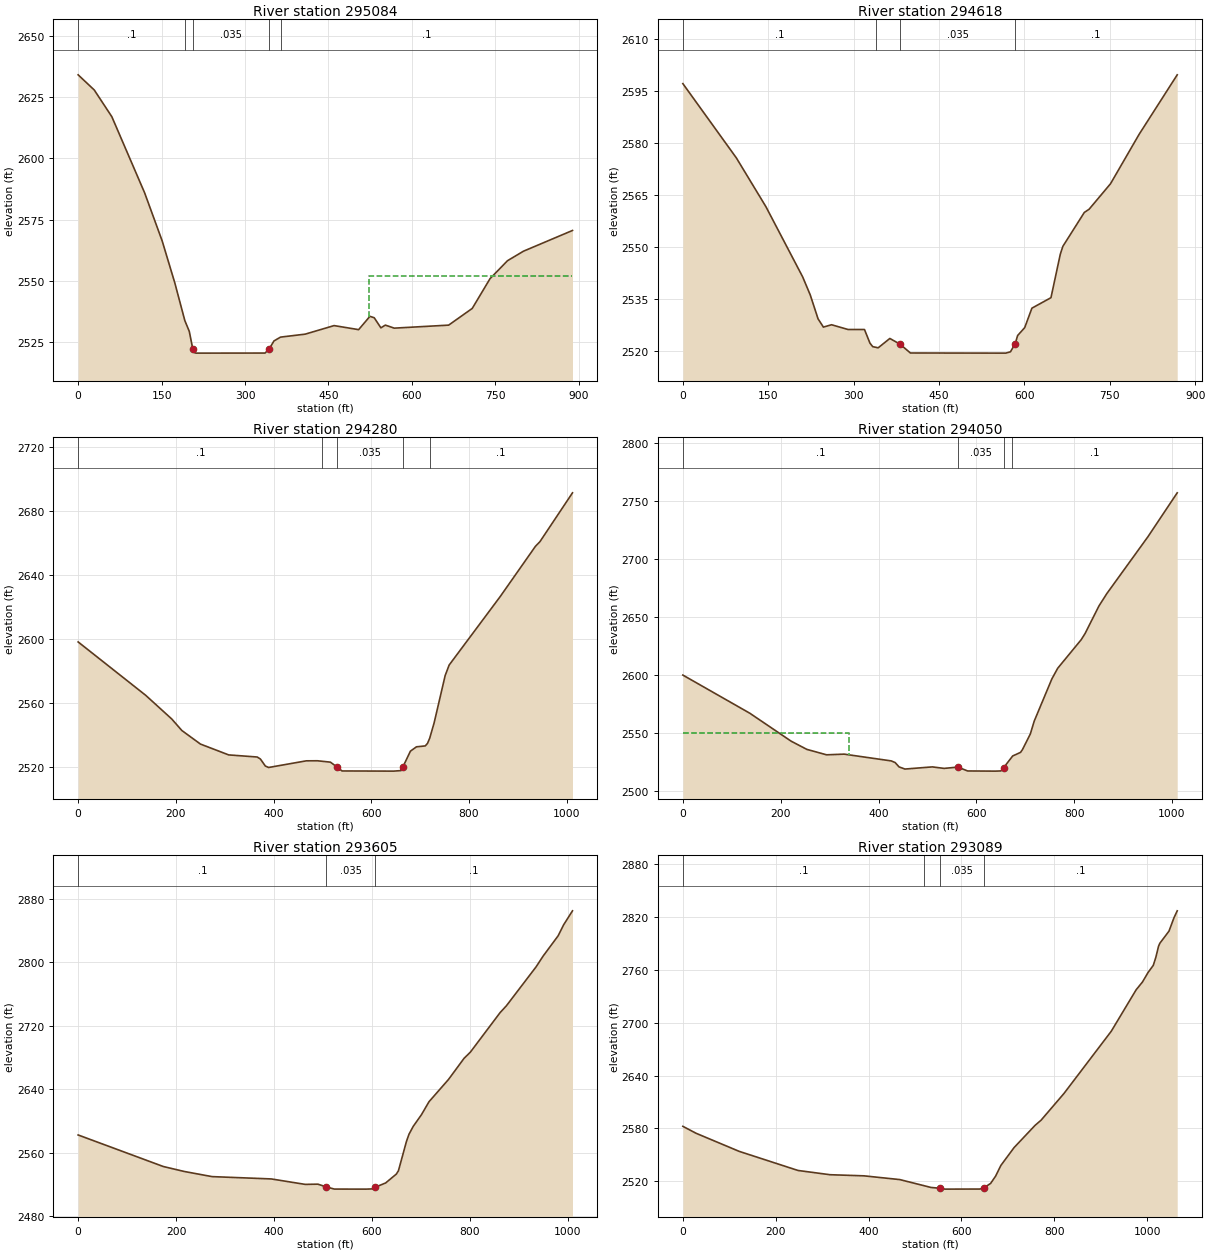
Type RM Length L Ch R = 1 ,295084  ,428.4,466.3,483.2
BEGIN DESCRIPTION:
c/e of 0.5/0.7 used to correct drawdown
END DESCRIPTION:
XS GIS Cut Line= 3
2290393.64112805529891.5735990222290304.06935673530061.026629398
2290271.33280993530757.191243684
#Sta/Elev= 30
       0 2634.02      29 2627.83    60.6 2616.93   119.5  2585.9   151.1 2566.25
   173.7 2549.21   191.7 2533.86   191.7 2533.82   199.8 2529.37   206.22522.078
   207.8 2520.83   211.8  2520.5     336 2520.53   343.2 2522.14     352 2525.47
   363.8 2527.03   408.1 2528.24   460.1 2531.73   504.2 2530.08   524.5 2535.51
   532.2 2534.93   544.2 2530.82   552.2 2531.93   568.2 2530.69     666 2531.92
   708.4 2538.73   740.4 2550.88   771.8  2558.2   800.5 2562.08   888.6 2570.53
#Mann= 5 ,-1,0
       0      .1       0   191.7     .12       0   206.2    .035       0
   343.2    .025       0   363.8      .1       0
#XS Ineff= 2 , 0
                          523.38         2551.96
Permanent Ineff=
       F       F
Bank Sta=206.2,343.2
XS Rating Curve= 0 ,0
Exp/Cntr=0.7,0.5

Type RM Length L Ch R = 1 ,294618  ,221,338.3,390
XS GIS Cut Line= 3
2290185.98927831529788.7195097752289884.76458846529988.732703834
2289735.35714229530473.102005111
#Sta/Elev= 30
       0 2597.05      94 2575.61   145.9 2561.54   210.5 2541.27   223.8 2536.07
   237.5 2529.18   246.9 2526.79   261.2 2527.47   290.1  2526.1   319.1 2526.09
   328.7 2522.15   333.5 2521.16   343.1 2520.81   363.6 2523.51   381.6 2521.86
   399.7 2519.32   567.2 2519.28   575.5 2519.66   583.9 2522.02   588.1 2524.35
   600.6 2526.65   613.2 2532.25   646.7 2535.28   663.1 2547.84   667.6  2550.1
   705.3 2559.88   713.7  2560.8   751.3 2568.16   801.6 2582.43   868.5 2599.59
#Mann= 4 ,-1,0
       0      .1       0     340     .08       0   381.6    .035       0
   583.9      .1       0
Bank Sta=381.6,583.9
XS Rating Curve= 0 ,0
Exp/Cntr(USF)=0,0
Exp/Cntr=0.3,0.1

Type RM Length L Ch R = 1 ,294280  ,182.7,229.4,264.9
XS GIS Cut Line= 3
2290184.08455999529738.4471483412289742.30936447 529867.35039236
2289252.97763232530122.653904786
#Sta/Elev= 30
       0 2598.36   138.3 2565.01   191.6 2550.22   212.4 2542.99   250.5 2534.52
   308.2 2527.76   366.6 2526.44   373.1 2525.21   383.3 2520.79     390  2519.9
   467.1 2524.05   489.8 2524.09   516.5 2523.23   530.3 2520.12   540.2 2517.73
   645.7 2517.62   661.1 2517.95   664.7 2520.12   680.3 2530.11   692.7 2532.81
   710.7 2533.38   715.3 2534.98   719.8 2538.23   728.8 2547.75   751.4 2577.32
   759.6 2583.92   864.1 2626.71   936.3 2658.14   945.4 2660.99  1012.1 2691.54
#Mann= 5 ,-1,0
       0      .1       0   500.2     .08       0   530.3    .035       0
   664.7     .08       0   720.2      .1       0
Bank Sta=530.3,664.7
XS Rating Curve= 0 ,0
Exp/Cntr(USF)=0,0
Exp/Cntr=0.3,0.1

Type RM Length L Ch R = 1 ,294050  ,424,445.4,470.5
XS GIS Cut Line= 3
2290184.55143432529687.0292906142289773.59655962529723.429294669
2289176.28411794529692.327609023
#Sta/Elev= 30
       0 2599.85   136.9 2566.89   221.2  2542.8   253.4 2535.68   293.8 2530.98
   329.7 2531.56     426 2525.72     434  2524.3     442 2520.54   454.1 2518.68
   510.1 2520.55   534.1 2519.25   562.2 2520.37   582.2 2517.03   638.3 2516.89
   650.3 2517.05   655.9 2519.93   674.3 2529.97   690.4 2533.09   694.4 2535.55
   710.4 2549.02   718.4 2560.15   754.4 2596.53   766.3 2605.71   814.5 2630.47
   822.5 2635.89   850.6 2659.48   866.6 2670.12   950.7 2719.27  1010.7 2757.26
#Mann= 4 ,-1,0
       0      .1       0   562.2    .035       0   655.9     .08       0
  672.56      .1       0
#XS Ineff= 2 , 0
          338.73 2549.76
Permanent Ineff=
       F       F
Bank Sta=562.2,655.9
XS Rating Curve= 0 ,0
Exp/Cntr(USF)=0,0
Exp/Cntr=0.3,0.1

Type RM Length L Ch R = 1 ,293605  ,488.6,515.8,540.6
XS GIS Cut Line= 2
2290176.94111564529487.291735489     2289243.487      529103.548
#Sta/Elev= 30
       0 2582.24   173.8 2542.42   216.7 2536.14   273.3 2529.66   394.4 2526.72
   463.6 2519.84   489.5 2520.12   506.8 2516.59   523.2 2513.92   587.6 2513.86
     602 2514.17   607.1 2516.38   627.9 2521.69   649.6 2532.84   653.9 2536.99
   670.3 2574.07   675.5 2583.16   684.1 2593.04     701  2607.9   716.3 2624.15
   756.2 2652.34   787.9 2678.96   800.9 2686.88   861.5  2736.7   874.4 2745.35
     935 2794.49   949.2 2807.95   979.9 2833.59   991.2 2847.56  1009.3  2865.2
#Mann= 3 ,0,0
       0      .1       0   506.8    .035       0   607.1      .1       0
Bank Sta=506.8,607.1
XS Rating Curve= 0 ,0
Exp/Cntr=0.3,0.1

Type RM Length L Ch R = 1 ,293089  ,490,505.4,517.9
XS GIS Cut Line= 2
2290380.68588835529269.559685864     2289615.121      528529.195
#Sta/Elev= 30
       0 2582.38    28.5  2574.5   121.4 2553.98     248 2532.33     317  2527.5
   390.2 2526.23   467.4 2521.98   534.9 2513.01   554.62512.157   564.4 2511.16
   639.9 2511.26   648.4 2512.68   662.9 2517.56   673.8 2525.96   685.1 2538.03
   713.5 2558.26   758.8  2583.5   771.6 2589.28     821 2619.63   922.8 2690.16
   976.6 2737.31   990.2 2746.12    1002 2756.74  1013.5    2765    1019 2774.19
  1024.7 2786.51  1027.5 2789.98  1047.3 2803.79    1058 2818.94    1065  2826.8
#Mann= 4 ,-1,0
       0      .1       0     520    .025       0   554.6    .035       0
   648.4      .1       0
Bank Sta=554.6,648.4
XS Rating Curve= 0 ,0
Exp/Cntr=0.3,0.1

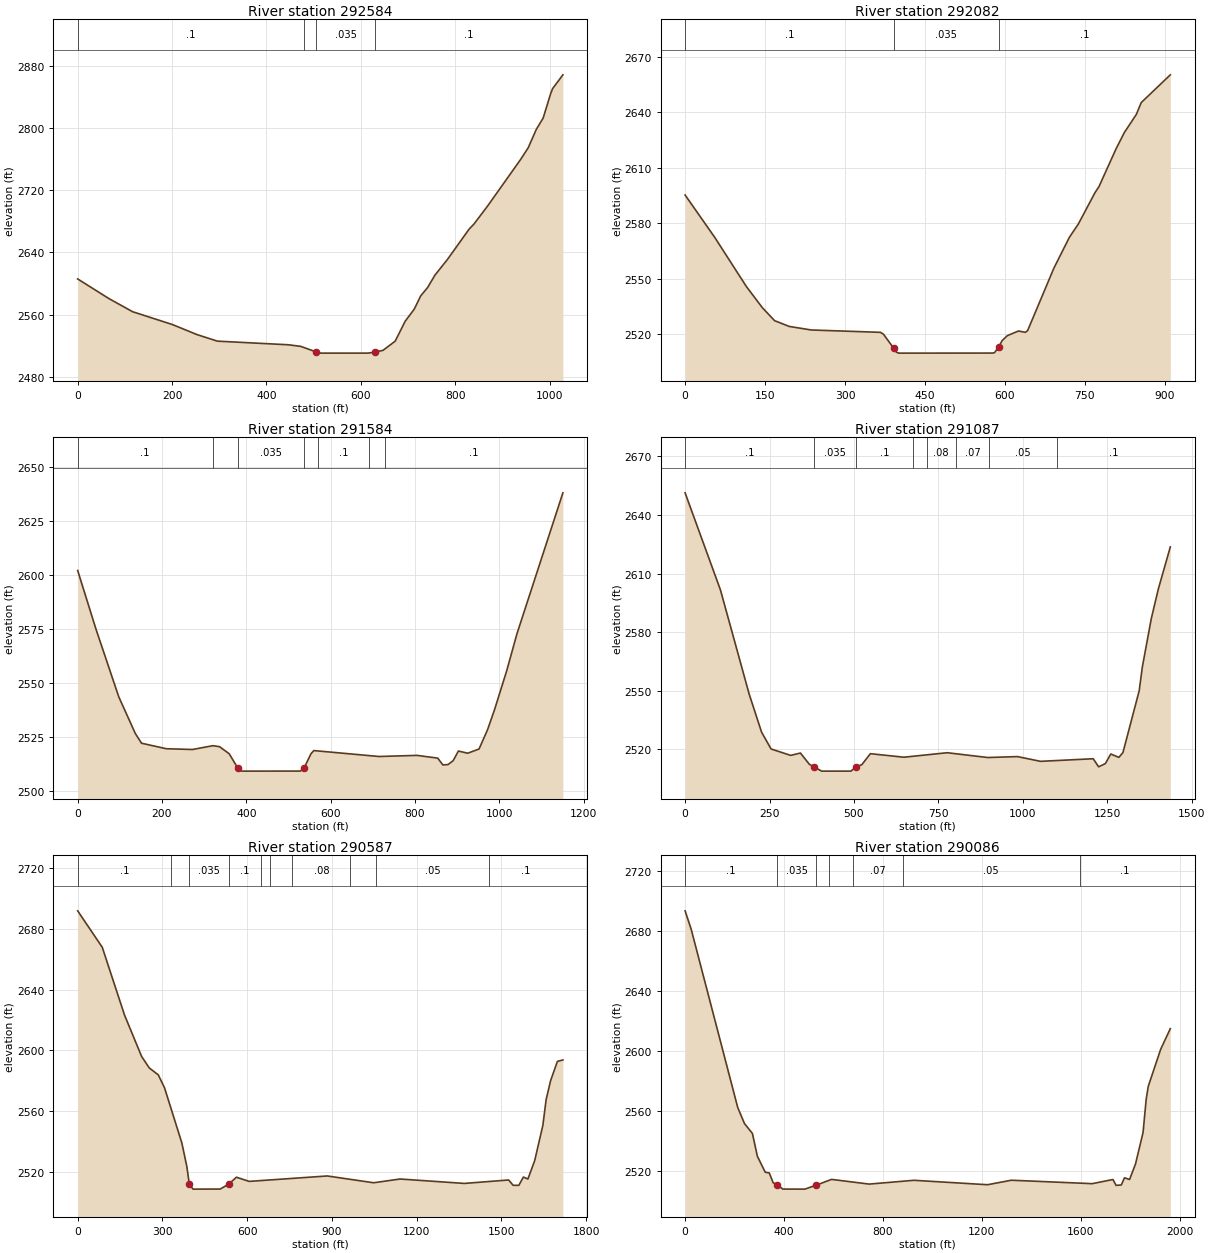
Type RM Length L Ch R = 1 ,292584  ,501.3,501.7,504.4
XS GIS Cut Line= 2
2290671.80392556529017.248103233     2290089.561      528169.574
#Sta/Elev= 30
       0  2605.9    65.9 2580.76   116.5 2563.75   201.2 2547.16   252.9 2534.34
   296.1 2525.91   446.5 2521.24   472.7  2519.2   506.1  2511.9   514.7  2510.5
   615.4 2510.51   630.9 2511.95   647.1 2514.08   672.9 2525.85     694 2551.37
   713.4  2567.1     727 2584.05     742 2595.11   757.1 2610.71   783.6 2630.87
   829.9 2670.17   839.8 2676.38   868.6 2699.49     939  2759.7   954.9 2774.58
   972.1 2798.29   986.5  2812.7  1002.6  2844.4  1006.6 2850.64  1028.4 2868.36
#Mann= 4 ,-1,0
       0      .1       0     480    .025       0   506.1    .035       0
   630.9      .1       0
Bank Sta=506.1,630.9
XS Rating Curve= 0 ,0
Exp/Cntr=0.3,0.1

Type RM Length L Ch R = 1 ,292082  ,497.6,498.1,491.4
XS GIS Cut Line= 2
     2291030.412      528656.114     2290516.593       527904.99
#Sta/Elev= 30
       0 2595.24    55.5 2572.38     115 2545.74   144.7 2534.39   167.8 2527.31
   195.2 2524.19   236.8 2522.26   366.3 2520.99   372.1 2519.98   391.3 2512.39
   396.1 2510.33   400.9 2509.75   576.4 2509.78   580.3 2509.97   587.9 2512.93
   594.8 2516.56   604.5 2519.22   625.3 2521.71   638.4 2520.98   642.6 2522.01
   691.7 2555.68   720.8 2572.37   737.6 2579.56   769.1 2596.65   776.2 2599.71
   808.1 2620.05   823.9 2629.03   846.4 2638.82   855.5  2645.2   910.1 2660.21
#Mann= 3 ,-1,0
       0      .1       0   391.3    .035       0   587.9      .1       0
Bank Sta=391.3,587.9
XS Rating Curve= 0 ,0
Exp/Cntr=0.3,0.1

Type RM Length L Ch R = 1 ,291584  ,514.4,497,483.8
XS GIS Cut Line= 3
     2291409.614      528324.7282290932.67925731527651.722654008
2290613.42427293      527585.796
#Sta/Elev= 30
       0 2602.21    43.7 2574.88    97.5  2543.7   136.7 2526.76   151.4 2522.25
   210.2 2519.69   272.3 2519.33   320.7  2521.1   336.4 2520.64   359.4 2517.37
   379.4 2510.84   389.9 2509.32   528.3 2509.34   537.3 2510.87   553.4 2517.37
   560.2 2518.83     715 2516.09     805 2516.61     854 2515.34   866.2 2512.19
   878.5 2512.36   890.7 2514.18     903 2518.62   925.2 2517.61     952 2519.56
   972.4 2528.59   988.8  2537.8  1017.3 2555.57  1041.9 2572.89  1150.9 2638.16
#Mann= 7 ,-1,0
       0      .1       0     320    .025       0   379.4    .035       0
   537.3    .025       0     570      .1       0     690     .07       0
     730      .1       0
Bank Sta=379.4,537.3
XS Rating Curve= 0 ,0
Exp/Cntr=0.3,0.1

Type RM Length L Ch R = 1 ,291087  ,527.2,499.5,467
XS GIS Cut Line= 4
     2291867.629      527965.855     2291539.674      527650.484
2291313.42726528 527430.021282282290648.01978557527404.567723082
#Sta/Elev= 30
       0 2651.33   104.7 2601.62   189.6 2548.39   226.4 2528.86   254.5 2520.24
   312.6 2516.93   341.5 2518.14   367.9 2512.38     382 2511.04   404.3 2508.88
   491.2 2508.88   506.5 2511.09   523.4  2512.2   548.6 2517.81   647.9    2516
   776.1  2518.3   896.3 2515.84   984.3 2516.32  1052.3 2513.89  1208.5 2515.22
  1224.5 2511.08  1244.5 2512.75  1260.5 2517.63  1284.5 2515.93  1296.5 2518.38
  1344.6 2549.99    1354 2562.22  1380.6 2587.06  1401.3 2602.09  1436.8 2623.64
#Mann= 8 ,-1,0
       0      .1       0     382    .035       0   506.5      .1       0
  674.99     .07       0  714.99     .08       0  800.88     .07       0
  900.88     .05       0 1100.88      .1       0
Bank Sta=382,506.5
XS Rating Curve= 0 ,0
Exp/Cntr=0.3,0.1

Type RM Length L Ch R = 1 ,290587  ,539.3,501.4,461.1
XS GIS Cut Line= 3
     2292272.278      527456.364 2291547.1776246527128.796592431
2290628.74943865527210.820863533
#Sta/Elev= 30
       0 2691.94    87.1 2667.88   165.7 2623.29   226.2 2595.97   253.4 2588.34
   285.4 2583.76   307.4 2575.28   368.8 2538.88   386.4 2523.37   395.1 2511.81
   408.3 2508.43   504.4 2508.48   534.6 2511.67   561.9 2516.28   607.2 2513.53
   883.6 2517.11  1047.7 2512.63  1141.6  2515.1  1368.9 2512.19  1525.6 2514.46
  1541.6 2510.94  1561.7 2510.92  1577.8 2516.39  1593.8  2515.1  1617.9 2527.25
  1646.7 2550.43  1658.4  2567.5  1674.1 2579.91  1698.2 2592.65  1717.7 2593.62
#Mann= 10 ,-1,0
       0      .1       0     330    .025       0   395.1    .035       0
   534.6      .1       0     650     .08       0     680     .07       0
     760     .08       0  965.66      .1       0 1055.66     .05       0
 1455.66      .1       0
Bank Sta=395.1,534.6
XS Rating Curve= 0 ,0
Exp/Cntr=0.3,0.1

Type RM Length L Ch R = 1 ,290086  ,572.2,494.8,415.5
XS GIS Cut Line= 3
     2292456.301      526801.9972291551.69806647526784.603809925
 2290542.9980173527100.190904736
#Sta/Elev= 30
       0 2693.44    24.5 2681.24   212.9 2562.22   240.2 2551.53   272.2 2544.98
   292.2 2529.76   324.2 2519.06   340.2 2518.66   356.2 2512.03   372.2 2510.88
     395 2507.88   484.2 2507.84   528.2 2510.38   592.2 2514.33   744.3  2511.2
   925.2 2513.73  1222.8 2510.78  1319.2 2513.78  1646.1 2511.48  1729.9 2514.25
  1742.5 2510.34  1763.5 2510.62  1776.4  2515.4    1797 2514.27  1821.1 2524.68
  1851.5 2545.61  1864.1 2567.68  1872.4 2576.28  1922.7 2601.11  1961.7 2614.86
#Mann= 7 ,-1,0
       0      .1       0   372.2    .035       0   528.2      .1       0
     580     .05       0     680     .07       0     880     .05       0
 1594.77      .1       0
Bank Sta=372.2,528.2
XS Rating Curve= 0 ,0
Exp/Cntr=0.3,0.1

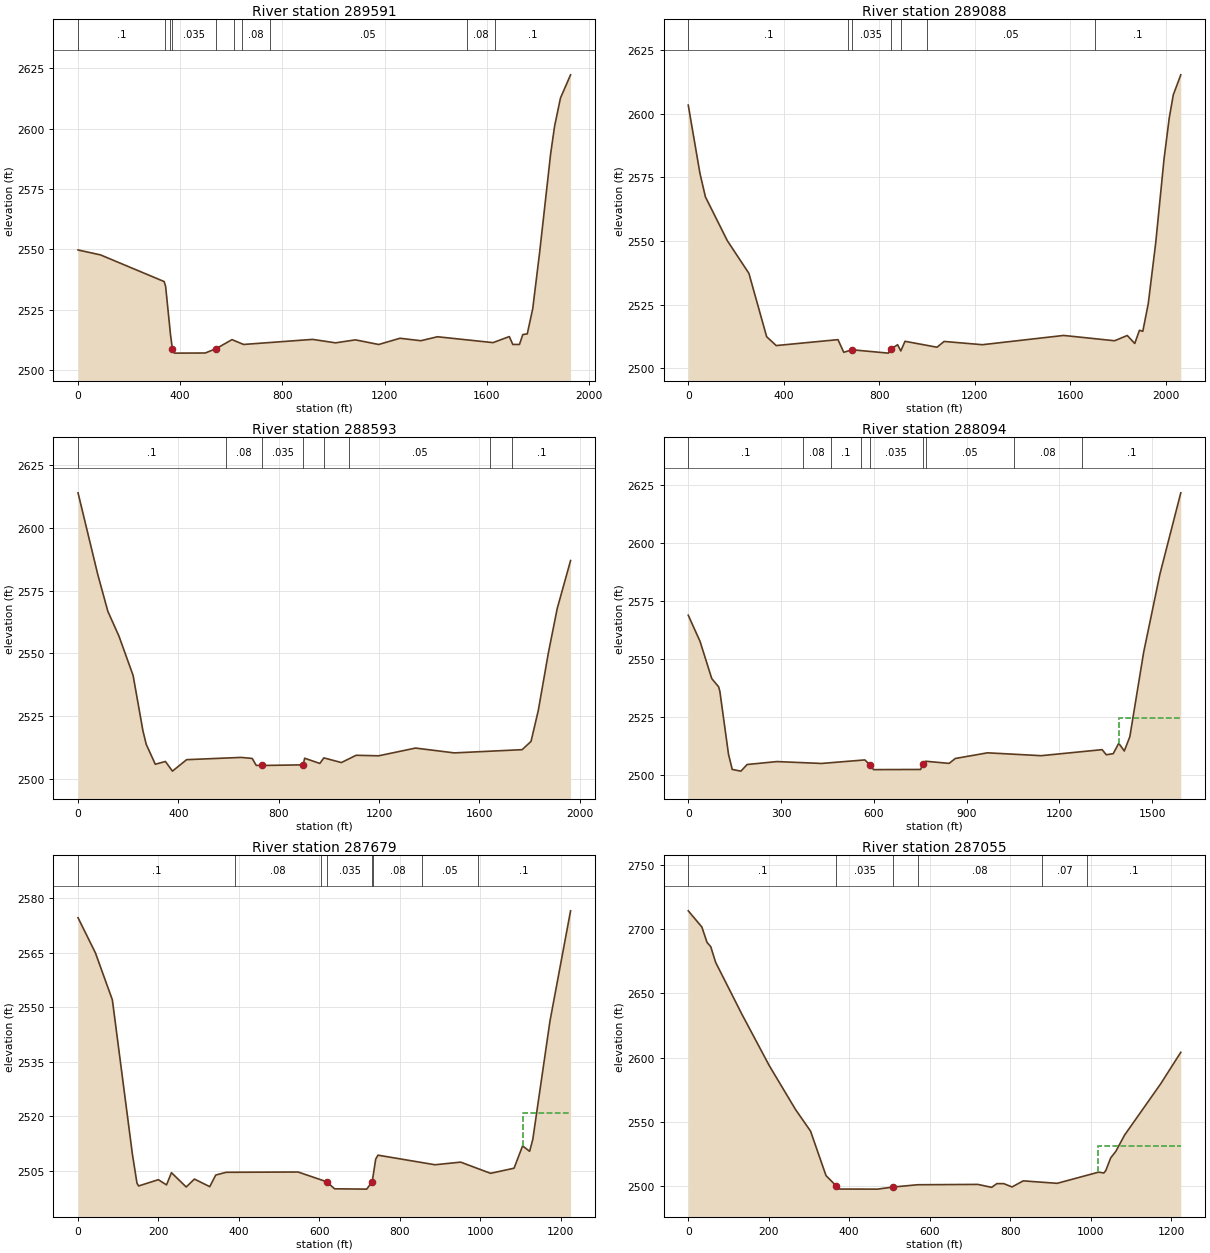
Type RM Length L Ch R = 1 ,289591  ,540.8,503.6,463.2
XS GIS Cut Line= 3
     2292124.341      526049.3842291498.98167423526642.017493635
2290515.70617015527054.633603006
#Sta/Elev= 30
       0 2549.77    87.7 2547.74     337  2536.7   342.8  2534.7   362.1 2514.57
  369.21 2508.97   377.7 2507.06     498 2507.11  541.66 2508.97   602.6 2512.65
   647.9 2510.65   918.1 2512.75  1007.8 2511.32  1085.8 2512.55  1176.9 2510.64
  1260.3 2513.22  1341.8  2512.2  1406.8 2513.84  1624.4 2511.41  1688.1 2513.91
  1701.8 2510.66  1727.9 2510.66  1740.9 2514.75  1758.4 2515.03  1779.8 2525.47
  1807.3 2549.24    1850 2589.72  1865.3 2601.02  1888.4  2612.7  1927.9 2622.29
#Mann= 10 ,-1,0
       0      .1       0     340    .025       0     360      .1       0
  369.21    .035       0  541.66    .025       0     610      .1       0
     640     .08       0     750     .05       0 1521.56     .08       0
 1631.56      .1       0
Bank Sta=369.21,541.66
XS Rating Curve= 0 ,0
Exp/Cntr=0.3,0.1

Type RM Length L Ch R = 1 ,289088  ,523.8,495.1,456.7
XS GIS Cut Line= 3
2291704.98411911525392.1791379672291239.16294639526381.833487367
 2290515.8060873 527025.23384669
#Sta/Elev= 30
       0 2603.44    48.9 2576.66    71.8 2567.39   163.7 2550.14   253.9 2537.33
   328.3 2512.41   368.2 2508.94   626.8 2511.27     651  2506.3   686.4 2507.28
   837.8 2505.97   847.2 2507.48   876.5 2509.27   889.7 2506.82   907.4 2510.62
  1041.4 2508.29    1071 2510.56  1231.6 2509.28  1571.4 2512.92    1785 2510.83
  1837.8  2512.9  1869.2 2509.76  1888.8 2514.95  1902.9 2514.54  1925.6 2525.36
  1956.8 2549.19  1991.8 2582.28  2013.4 2598.26  2030.4 2607.45  2061.9 2615.34
#Mann= 7 ,-1,0
       0      .1       0     670     .07       0   686.4    .035       0
   847.2    .025       0     890     .07       0    1000     .05       0
  1703.8      .1       0
Bank Sta=686.4,847.2
XS Rating Curve= 0 ,0
Exp/Cntr=0.3,0.1

Type RM Length L Ch R = 1 ,288593  ,514.1,498.3,480.5
XS GIS Cut Line= 3
2291003.17755782525122.968752332 2290867.6147243526367.300576493
2290469.44280196526957.372594585
#Sta/Elev= 30
       0 2614.01    78.7 2581.42   118.9 2566.74   163.2 2556.84   219.5 2541.19
   258.7 2519.11   271.8 2513.71     308 2505.76   348.3 2506.87   376.4 2503.02
   432.9 2507.59     650 2508.49   694.3 2508.08   710.4 2505.31   734.5 2505.27
  897.212505.528   903.5 2508.16   963.9 2506.09     980  2508.3  1049.7 2506.44
  1108.7 2509.34  1198.5 2509.13  1345.6 2512.22  1500.1 2510.29  1770.3 2511.58
  1805.8 2514.87  1834.7 2527.17    1875 2550.17  1910.2 2567.85  1963.5 2587.01
#Mann= 8 ,-1,0
       0      .1       0     590     .08       0   734.5    .035       0
  897.21    .025       0     980      .1       0    1080     .05       0
 1641.69     .08       0 1731.69      .1       0
Bank Sta=734.5,897.21
XS Rating Curve= 0 ,0
Exp/Cntr=0.3,0.1

Type RM Length L Ch R = 1 ,288094  ,343.2,414.8,472.9
XS GIS Cut Line= 3
2290382.32821489 525243.138045642290438.67076596 526295.00665093
 2290196.7954506526776.326603006
#Sta/Elev= 30
       0 2568.88    38.1 2557.62    75.9 2541.58    98.2    2538   102.2 2536.04
   130.2 2508.89   142.2 2502.38   170.3 2501.66   190.3 2504.51   286.5 2505.78
   430.7 2504.97   570.9 2506.49   586.9 2504.41   598.9 2502.31   751.1 2502.38
  757.73 2504.56   767.1 2505.93   843.2    2505   863.3 2507.11   967.4 2509.55
  1140.9 2508.32  1337.8 2510.92  1351.3 2508.73  1373.7 2509.18  1391.6 2513.67
  1409.5 2510.35  1427.4  2516.5  1472.1 2552.92  1524.6 2586.59  1592.1 2621.65
#Mann= 9 ,-1,0
       0      .1       0     370     .08       0     460      .1       0
     560    .025       0   586.9    .035       0  757.73    .025       0
   767.1     .05       0 1053.38     .08       0 1273.38      .1       0
#XS Ineff= 2 , 0
                         1390.87         2524.62
Permanent Ineff=
       F       F
Bank Sta=586.9,757.73
XS Rating Curve= 0 ,0
Exp/Cntr=0.3,0.1

Type RM Length L Ch R = 1 ,287679  ,649.5,624.2,582.3
XS GIS Cut Line= 3
2290225.89003722525229.511413384  2290122.987291525743.163019127
2289662.45634293526271.035801503
#Sta/Elev= 30
       0 2574.64    43.3 2564.94    85.3 2552.05   135.1 2509.58   146.5 2501.59
   150.6 2500.81   199.6 2502.54     220 2501.11   232.2 2504.47   268.9 2500.53
   289.3 2502.71   327.4 2500.62   342.3 2503.82   368.2 2504.57   547.1 2504.65
     618 2501.97   637.8 2500.03   717.6 2499.94   731.4    2502   739.9 2508.18
   745.6 2509.29   887.3 2506.65   951.2 2507.37  1025.5 2504.29  1083.9  2505.7
  1105.1 2511.84  1122.6 2510.35  1130.5 2513.64  1173.1 2546.15  1224.4 2576.54
#Mann= 8 ,-1,0
       0      .1       0     390     .08       0  603.86    .025       0
     618    .035       0   731.4     .05       0  733.86     .08       0
  853.86     .05       0  993.86      .1       0
#XS Ineff= 2 , 0
                          1105.8         2520.83
Permanent Ineff=
       F       F
Bank Sta=618,731.4
XS Rating Curve= 0 ,0
Exp/Cntr=0.3,0.1

Type RM Length L Ch R = 1 ,287055  ,464,454.1,429.4
XS GIS Cut Line= 2
2289780.91113647524981.6724545872289340.50768188526123.748119623
#Sta/Elev= 30
       0 2714.19    33.8 2701.64    46.6  2689.7    55.9 2686.31    68.1  2674.1
   133.2 2633.88   201.3 2593.87   266.3 2559.88   303.9 2542.94   342.4 2508.33
   368.4 2500.18   376.7  2497.9   470.5 2497.84   509.6 2499.48     570 2501.24
   719.7 2501.51     754 2499.22   766.9 2502.13     784 2502.12   804.6 2499.53
   832.5 2504.27   916.9 2502.35  1019.8 2511.05  1032.7 2510.38  1037.6 2512.25
  1049.8 2522.11  1062.7 2527.28  1084.1 2539.74  1174.1 2579.74    1224 2604.22
#Mann= 6 ,-1,0
       0      .1       0   368.4    .035       0   509.6      .1       0
     570     .08       0     880     .07       0     990      .1       0
#XS Ineff= 2 , 0
                         1019.04         2531.03
Permanent Ineff=
       F       F
Bank Sta=368.4,509.6
XS Rating Curve= 0 ,0
Exp/Cntr=0.3,0.1