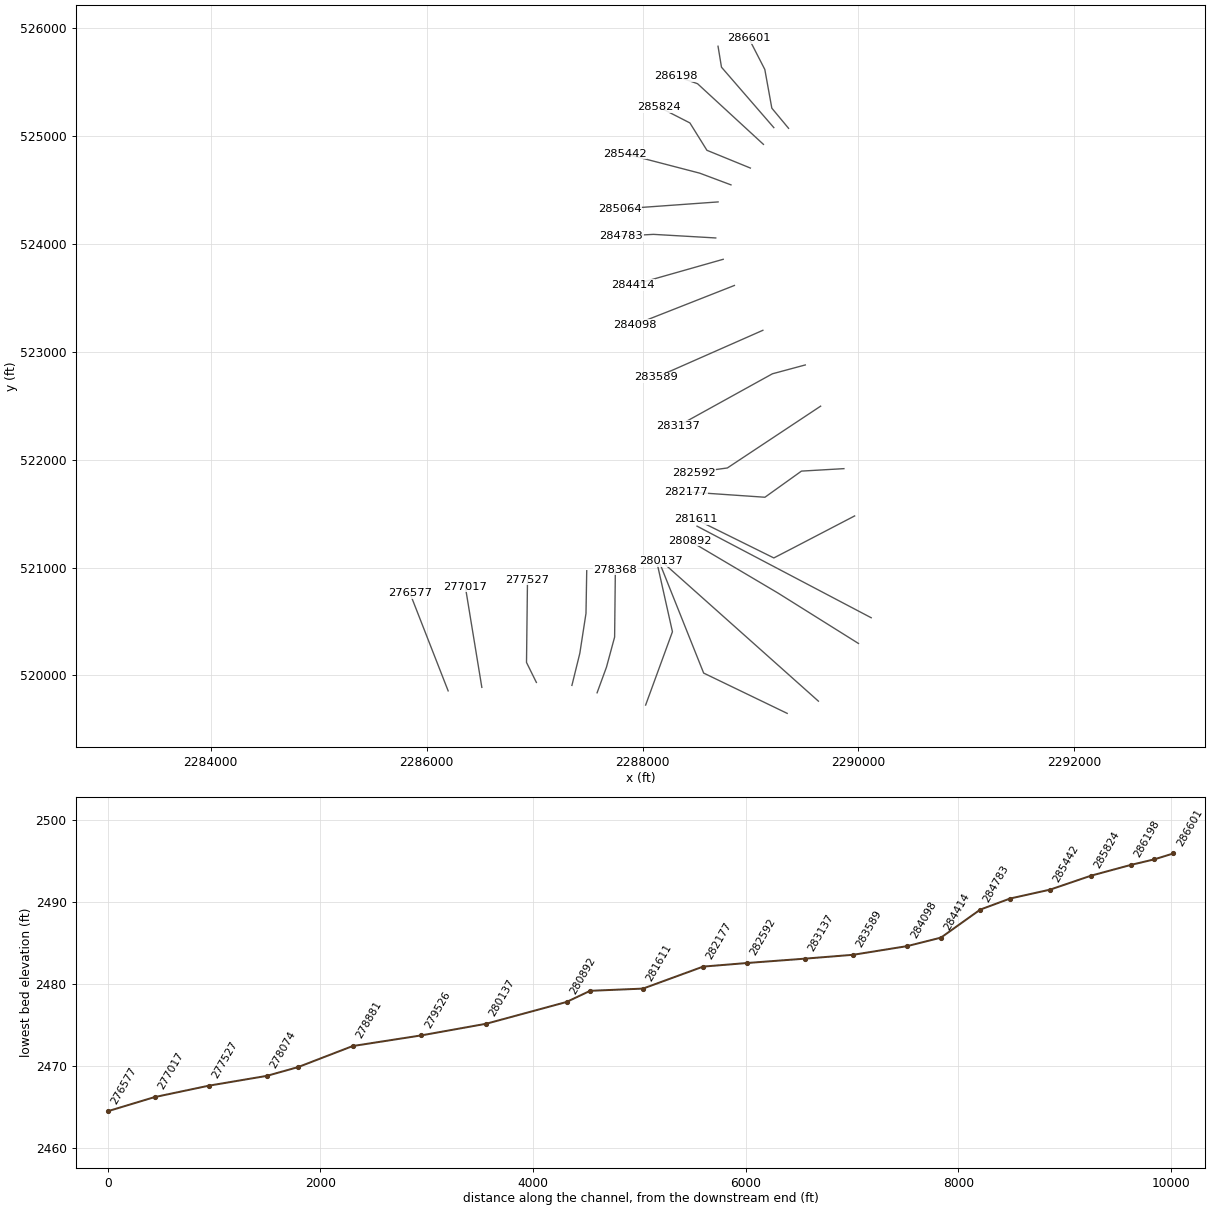
HEC-RAS study GRNBRRRV.prj: GRNBRRRV

--- GRNBRRRV.g01 (geometry) --- (continued)

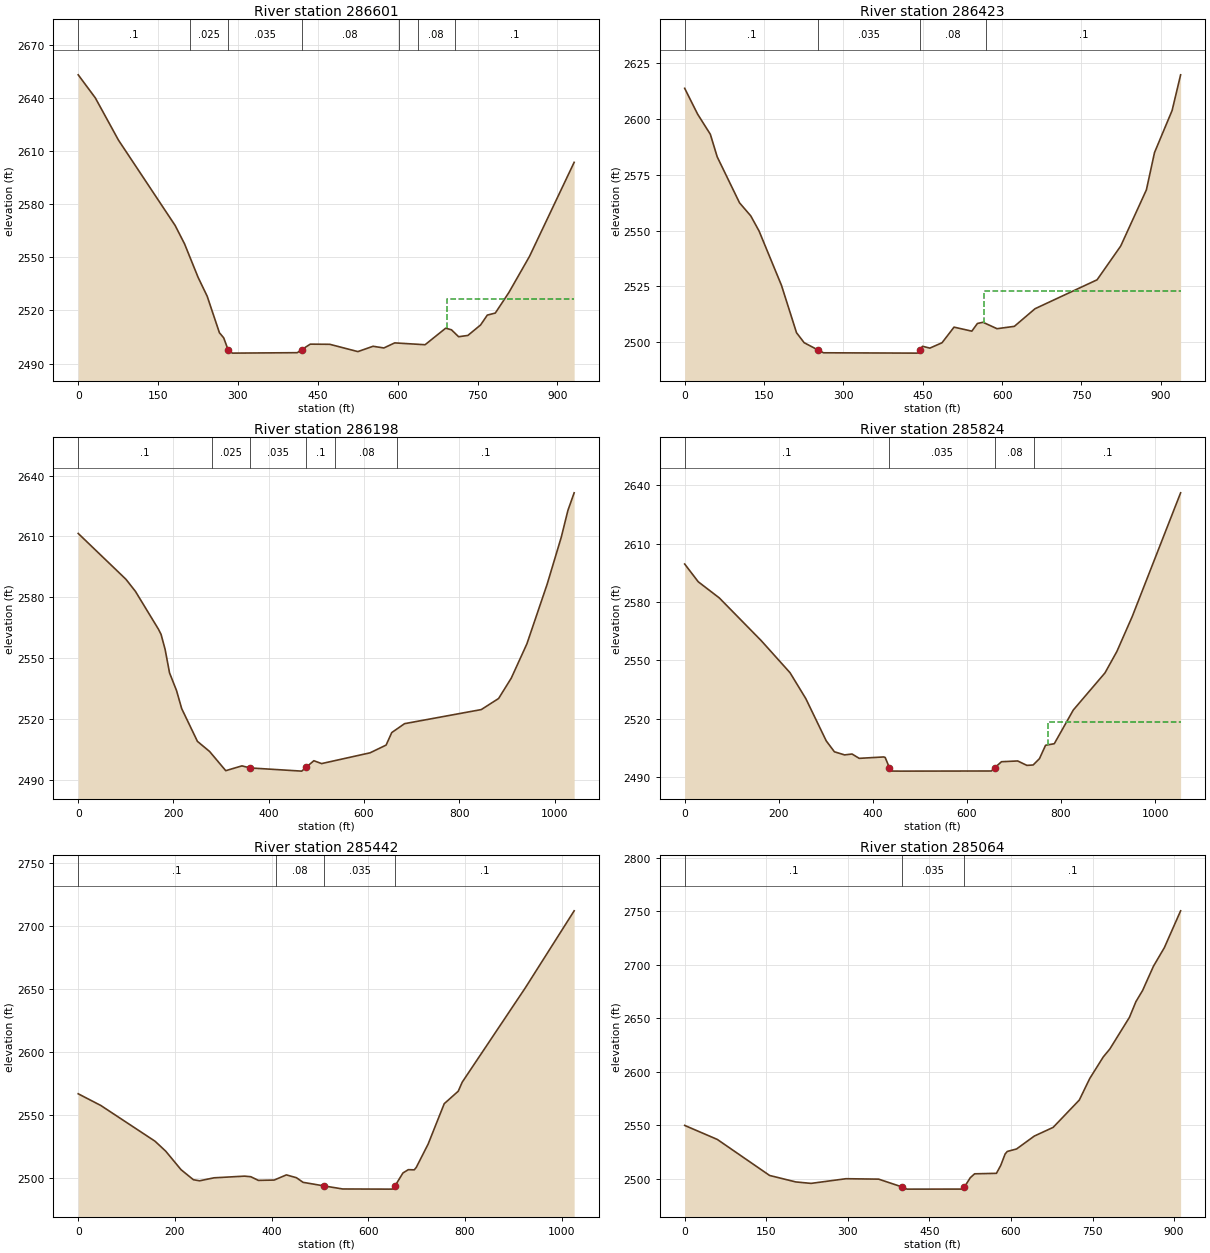
Type RM Length L Ch R = 1 ,286601  ,130.8,178.4,252.5
XS GIS Cut Line= 4
2289352.48469827525072.3084461652289197.62504378 525258.79371785
2289132.56051077 525617.853548152288984.54428932525906.266305714
#Sta/Elev= 30
       0 2653.03    32.1 2640.03    75.6 2616.17   182.1 2567.96   199.7 2557.62
   225.2 2538.68   242.3    2528   265.2 2507.44   273.3 2504.53   281.4 2497.88
   289.5 2495.91   411.5 2496.16   419.6 2497.87   435.9 2500.98   472.5 2500.89
   525.3 2496.77   553.8 2499.78   574.1 2498.82   594.4 2501.69   651.5 2500.65
   690.3    2510     701 2509.09   714.5 2505.17   731.9  2505.9   755.7 2511.79
   768.4 2517.38   783.4 2518.53   808.9 2530.14   847.8 2550.62   931.5 2603.62
#Mann= 7 ,-1,0
       0      .1       0     210    .025       0   281.4    .035       0
   419.6     .08       0   602.4     .07       0  637.31     .08       0
  707.31      .1       0
#XS Ineff= 2 , 0
                          692.39         2526.58
Permanent Ineff=
       F       F
Bank Sta=281.4,419.6
XS Rating Curve= 0 ,0
Exp/Cntr=0.3,0.1

Type RM Length L Ch R = 1 ,286423  ,221.4,224.4,233.3
XS GIS Cut Line= 3
2289215.93920272525078.6896421612288731.35178102525638.708124788
2288699.35072487525833.000251413
#Sta/Elev= 30
       0 2613.57    24.3  2602.1    48.5 2593.02    61.5 2582.93   103.7 2562.38
     125 2556.52   140.6 2549.79     183 2525.48   211.4 2504.33   225.8 2499.86
   251.9 2496.61   262.5 2495.34   439.8 2495.19     444 2496.51   449.7 2498.25
   463.5 2497.43   486.5 2499.83   509.2 2506.81   542.8 2505.01   553.4 2508.45
     564 2508.98   590.4 2506.11   623.2 2507.16   662.3 2515.04   779.6 2527.97
   824.2 2543.04   872.8 2568.17   888.2 2584.88   921.4 2603.65   937.5  2619.6
#Mann= 4 ,-1,0
       0      .1       0   251.9    .035       0     444     .08       0
     570      .1       0
#XS Ineff= 2 , 0
                           566.2         2523.09
Permanent Ineff=
       F       F
Bank Sta=251.9,444
XS Rating Curve= 0 ,0
Exp/Cntr(USF)=0,0
Exp/Cntr=0.3,0.1

Type RM Length L Ch R = 1 ,286198  ,389.6,374.1,342.3
XS GIS Cut Line= 3
2289119.93603427524923.2559408612288509.63017769525485.560213213
2288310.76647162525556.419694688
#Sta/Elev= 30
       0  2611.5   100.3 2588.91   120.1 2582.99   168.3 2564.41   173.9 2561.83
   182.4 2554.43   191.7 2542.88   206.4 2534.15   217.2 2525.28   250.3 2509.13
   275.8 2504.17   309.7 2494.72   343.7 2497.09   360.7 2496.07   469.2  2494.5
   478.3 2496.36   494.6 2499.62   510.9 2498.21   612.6 2503.51   646.3 2507.32
   658.1 2513.47     685 2517.86   846.1  2524.8   882.4 2530.25     909 2540.27
   941.8 2557.15   984.3 2586.49    1014 2609.69  1027.9 2622.83    1041 2631.49
#Mann= 6 ,-1,0
       0      .1       0     280    .025       0   360.7    .035       0
   478.3      .1       0     540     .08       0     670      .1       0
Bank Sta=360.7,478.3
XS Rating Curve= 0 ,0
Exp/Cntr(USF)=0,0
Exp/Cntr=0.3,0.1

Type RM Length L Ch R = 1 ,285824  ,306.8,382.7,447.7
XS GIS Cut Line= 4
2288998.78917885 524703.820127262288596.49018725524868.396987461
2288438.77069622525122.1196469362288153.04698059525268.410189337
#Sta/Elev= 30
       0 2599.53    28.8 2590.43    73.6 2582.13   162.7  2560.2   223.9 2543.75
   257.6  2530.4     301 2508.71   318.3 2503.13   339.9 2501.52   355.8 2501.98
   371.1 2499.75   423.2 2500.47   426.3  2500.2   435.3 2494.95   440.3 2493.23
   458.7 2493.19   652.2 2493.26  659.62 2495.04   673.6 2498.02     708 2498.41
   727.6 2496.14   740.8 2496.34   754.3  2499.6   767.3 2506.47   785.8 2507.27
   826.2 2524.56   893.6 2543.63   918.9 2554.64   951.6 2572.62  1054.4 2636.09
#Mann= 4 ,-1,0
       0      .1       0   435.3    .035       0  659.62     .08       0
  743.41      .1       0
#XS Ineff= 2 , 0
                          772.73         2518.59
Permanent Ineff=
       F       F
Bank Sta=435.3,659.62
XS Rating Curve= 0 ,0
Exp/Cntr(USF)=0,0
Exp/Cntr=0.3,0.1

Type RM Length L Ch R = 1 ,285442  ,343.9,378,401
XS GIS Cut Line= 3
2288819.28683333524547.9034498072288530.11113108524656.344338152
2287836.08944567524837.079152061
#Sta/Elev= 30
       0 2566.96    46.9 2557.68   158.8 2529.45   180.9  2521.6   212.7 2506.91
   238.3 2498.94   251.1 2498.09     281 2500.45   343.9 2501.78     357 2501.32
   372.8 2498.42   405.4 2498.68   430.7 2502.76   451.4 2500.54   465.2 2496.88
   509.2    2494   547.2 2491.62   641.5  2491.5   649.8 2491.53   655.4 2494.04
   671.8 2504.29   682.8 2506.89   695.2 2506.76   699.4 2508.72     724 2527.23
   757.2 2559.11   786.2 2569.01   794.4 2576.15   925.2 2650.96    1026 2711.78
#Mann= 4 ,-1,0
       0      .1       0  408.84     .08       0   509.2    .035       0
   655.4      .1       0
Bank Sta=509.2,655.4
XS Rating Curve= 0 ,0
Exp/Cntr(USF)=0,0
Exp/Cntr=0.3,0.1

Type RM Length L Ch R = 1 ,285064  ,288.4,280.1,267
BEGIN DESCRIPTION:
c/e of 0.5/0.7 used to correct drawdown in the 100 year profile
END DESCRIPTION:
XS GIS Cut Line= 2
     2288699.974      524389.874     2287790.292      524324.396
#Sta/Elev= 30
       0 2549.98      60 2536.87   156.2 2503.18   204.3 2497.14   232.4 2495.78
   296.6 2500.14   356.7 2499.75   399.7 2492.45   408.9 2490.41   509.1 2490.44
  514.572492.542   525.2 2501.08   533.2 2504.73   573.3 2505.18   581.3 2512.68
   589.3 2523.28   593.3 2525.65   610.3 2527.95   642.9    2540   677.6 2548.15
   725.7  2573.7   744.9 2593.85   769.8 2614.03   781.8 2621.39   817.9 2651.04
   829.9 2665.78     842 2676.05     862 2698.75   882.1 2716.18     912  2750.6
#Mann= 3 ,0,0
       0      .1       0   399.7    .035       0  514.57      .1       0
Bank Sta=399.7,514.57
XS Rating Curve= 0 ,0
Exp/Cntr=0.7,0.5

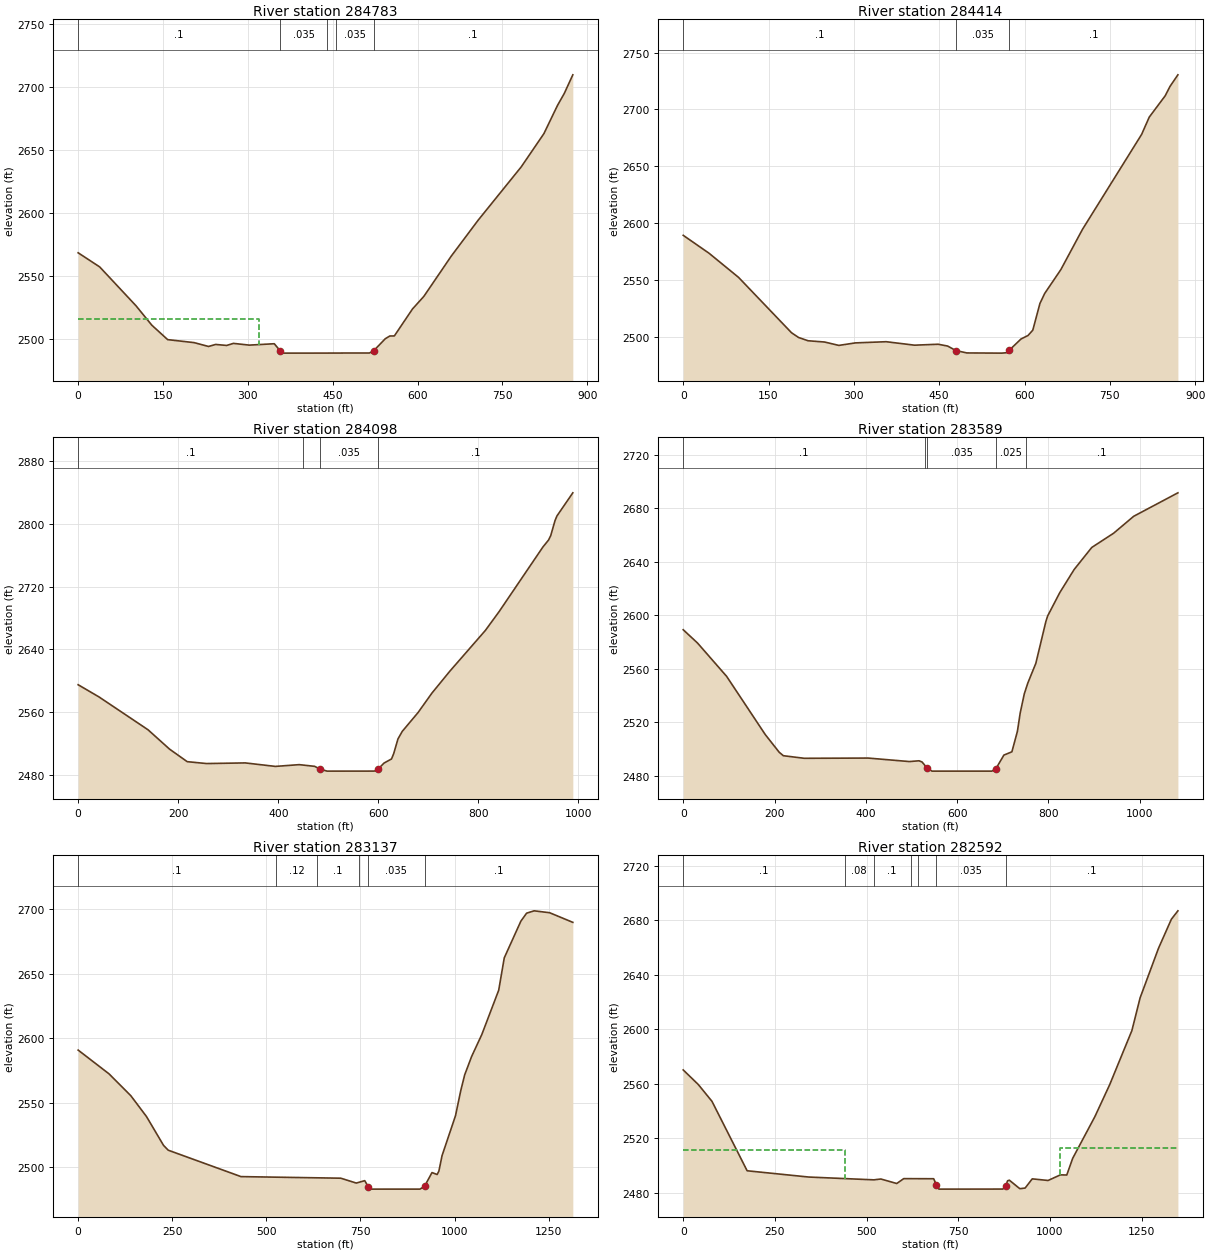
Type RM Length L Ch R = 1 ,284783  ,345.4,369.2,394.1
BEGIN DESCRIPTION:
IFA added to correct drawdown
END DESCRIPTION:
XS GIS Cut Line= 3
2288678.25536804524055.8384617822288101.46973804 524089.11455582
2287805.15404351524073.268796754
#Sta/Elev= 30
       0 2568.65    38.1 2557.45   102.3 2526.61   130.3  2511.2   158.3 2499.76
   204.9  2497.4   230.5 2494.34   243.1 2495.95   262.5 2495.15   274.5 2496.79
   302.5 2495.41   346.7 2496.51  356.85 2491.08   362.7 2489.06     440 2489.09
   456.22489.125   514.9 2489.16   522.2 2490.83     543  2500.5     551 2502.65
     559  2502.7   591.1 2524.11   611.1 2534.05   659.6 2566.02   707.2 2594.55
   783.3 2636.82   823.4  2663.2   847.4 2685.56   859.4 2695.07   874.5 2709.83
#Mann= 5 ,-1,0
       0      .1       0  356.85    .035       0     440     .08       0
   456.2    .035       0   522.2      .1       0
#XS Ineff= 2 , 0
          319.44 2516.33
Permanent Ineff=
       F       F
Bank Sta=356.85,522.2
XS Rating Curve= 0 ,0
Exp/Cntr(USF)=0,0
Exp/Cntr=0.3,0.1

Type RM Length L Ch R = 1 ,284414  ,309,315.9,322.7
XS GIS Cut Line= 2
 2288747.3523091523858.0779290082287910.75326974523620.355797608
#Sta/Elev= 30
       0 2589.27    45.4 2573.51    97.2 2552.32   190.4 2503.57   202.9 2499.39
   219.5 2496.53   248.6 2495.41   273.6 2492.44   302.7 2494.65   356.8 2495.69
   406.7 2492.64   448.2 2493.47   464.9 2491.86   479.3 2487.93   498.7 2485.81
   560.3 2485.65   568.8 2486.03     573  2488.1   593.8 2498.05   606.3  2501.2
   614.6 2505.85   627.1 2529.29   635.4 2538.06   663.9 2559.11   701.9  2594.5
   805.9 2678.03   819.3 2693.22   847.4 2712.04   855.8 2720.25   869.7 2730.44
#Mann= 3 ,0,0
       0      .1       0   479.3    .035       0     573      .1       0
Bank Sta=479.3,573
XS Rating Curve= 0 ,0
Exp/Cntr(USF)=0,0
Exp/Cntr=0.3,0.1

Type RM Length L Ch R = 1 ,284098  ,506.1,508.9,512
XS GIS Cut Line= 2
2288850.99553301523615.476747895     2287931.016      523253.067
#Sta/Elev= 30
       0 2594.83    41.7 2579.27   139.7 2537.37   182.8 2512.64     218 2496.69
   256.7 2494.28   334.1 2495.09   394.3 2490.64   441.9 2492.89   472.7 2490.73
   483.3 2487.34   497.4 2484.62     592 2484.66   599.2 2487.03   611.5 2494.93
   626.4 2500.16   630.7 2506.87   639.3 2525.71   647.9 2535.37   679.4 2559.31
   707.1 2584.09   742.5 2611.74   813.9 2664.03   841.4 2688.05   929.2  2770.7
   940.3 2779.43   944.6 2785.05   953.1 2804.01     957 2810.08   988.8 2839.64
#Mann= 4 ,-1,0
       0      .1       0     450     .07       0   483.3    .035       0
   599.2      .1       0
Bank Sta=483.3,599.2
XS Rating Curve= 0 ,0
Exp/Cntr=0.3,0.1

Type RM Length L Ch R = 1 ,283589  ,443.5,452.8,460.4
XS GIS Cut Line= 2
2289114.71983872523199.850723082      2288123.55      522762.303
#Sta/Elev= 30
       0 2589.23    31.3 2579.31      95 2554.42   179.8 2510.83   210.2 2497.68
   219.3 2495.08   265.1 2493.15     405 2493.32   495.4 2490.71   516.4 2491.28
   523.1  2490.4   534.6 2485.71     545 2483.56   676.1 2483.56   684.9  2485.4
   702.4 2495.56   719.9 2497.99     732 2513.36     738 2526.87   747.1 2541.39
   754.8 2549.43   772.3  2564.1   794.2 2595.23   798.2 2599.53   824.8 2616.99
   856.3 2634.28   894.8 2650.72   942.9 2661.42   986.6 2674.01  1083.5 2691.56
#Mann= 5 ,-1,0
       0      .1       0     530    .025       0   534.6    .035       0
   684.9    .025       0     750      .1       0
Bank Sta=534.6,684.9
XS Rating Curve= 0 ,0
Exp/Cntr=0.3,0.1

Type RM Length L Ch R = 1 ,283137  ,533.3,544.2,552.3
XS GIS Cut Line= 3
2289507.37724788522878.6911871612289202.92936213522796.664286712
2288328.73440984522312.960590159
#Sta/Elev= 30
       0 2590.75    82.2 2572.31     140  2555.4   181.5 2539.33     227 2516.92
   239.4 2513.23   432.7 2492.78   697.9 2491.55     739 2487.78   761.4 2489.64
     771 2484.91   780.2 2483.09   908.2  2483.1   920.3 2485.22   940.2 2495.91
   953.9 2494.41   958.5 2497.02   966.9 2508.99  1002.7 2539.96  1016.5 2559.19
    1027  2571.5  1045.3 2585.65  1072.7 2602.89  1117.5 2637.13  1132.2 2662.13
  1176.3 2690.54  1191.6 2696.75  1211.6 2698.57  1252.8  2697.1  1314.4 2689.65
#Mann= 6 ,-1,0
       0      .1       0   525.3     .12       0   635.3      .1       0
   745.3     .12       0     771    .035       0   920.3      .1       0
Bank Sta=771,920.3
XS Rating Curve= 0 ,0
Exp/Cntr=0.3,0.1

Type RM Length L Ch R = 1 ,282592  ,411,415.1,418.5
XS GIS Cut Line= 3
2289649.42090474522496.5853965412288785.54966807521923.633951844
 2288475.7947315521881.523913158
#Sta/Elev= 30
       0 2570.12    40.9 2559.47    78.4 2547.07   174.3 2496.04   342.3 2491.44
     520 2489.38   539.1 2489.99   582.3 2486.69   601.5 2490.27   683.1 2490.19
   690.7 2485.61   697.5 2482.56     872  2482.6   879.9 2485.22   884.7 2488.69
   889.5 2489.12     918 2482.89   932.5 2483.34   951.9  2490.1   995.1 2488.92
  1028.7 2493.03  1046.1 2492.94  1062.2 2505.18  1122.8 2535.83  1163.1 2559.26
  1223.7 2599.04  1246.1 2623.07  1296.3  2659.5  1331.4 2680.84  1349.2 2687.01
#Mann= 7 ,-1,0
       0      .1       0     440     .08       0     520      .1       0
     620     .08       0     640    .025       0   690.7    .035       0
   879.9      .1       0
#XS Ineff= 2 , 0
           440.9 2511.56 1027.72         2512.81
Permanent Ineff=
       F       F
Bank Sta=690.7,879.9
XS Rating Curve= 0 ,0
Exp/Cntr=0.3,0.1

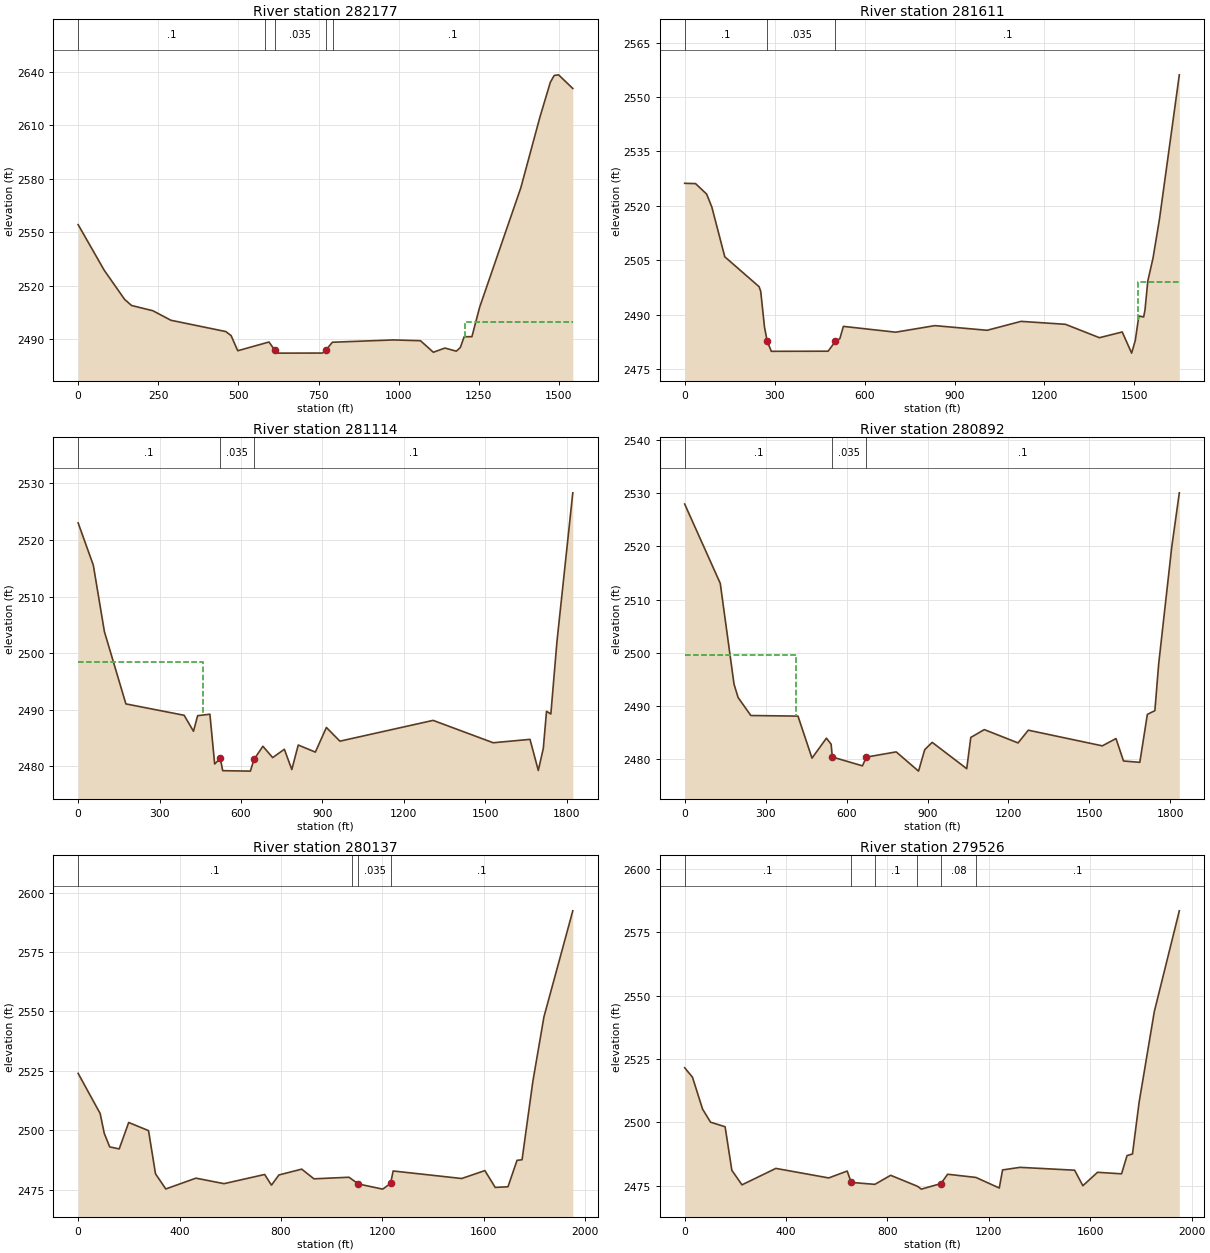
Type RM Length L Ch R = 1 ,282177  ,599,566.1,552.7
XS GIS Cut Line= 4
2289865.10348462521917.4424524782289471.94765192521894.584555228
2289133.65077262521652.2908443772288402.19806062521702.578218328
#Sta/Elev= 30
       0  2554.3    81.1 2528.74     145 2512.31   166.6 2508.88   233.3 2505.92
   289.4 2500.58   460.6 2494.24   477.2 2491.96   497.9 2483.46   595.3 2488.37
  613.24 2483.88   622.9 2482.12   762.5 2482.16   772.4 2483.73   793.2 2488.24
   983.8 2489.53    1068 2489.09  1108.1 2482.61  1144.2 2484.97  1179.8 2483.21
  1192.3  2485.3  1204.3 2491.34  1228.4 2491.35  1252.5 2507.91  1380.8  2574.9
  1440.9 2614.92    1473 2634.23    1485 2638.09  1498.7 2638.45  1543.1 2630.79
#Mann= 5 ,-1,0
       0      .1       0  583.82     .08       0  613.24    .035       0
   772.4     .12       0  793.82      .1       0
#XS Ineff= 2 , 0
                         1206.99          2499.7
Permanent Ineff=
       F       F
Bank Sta=613.24,772.4
XS Rating Curve= 0 ,0
Exp/Cntr(USF)=0,0
Exp/Cntr=0.3,0.1

Type RM Length L Ch R = 1 ,281611  ,629.9,496.8,417
XS GIS Cut Line= 4
     2289964.356      521479.0342289386.67561587521177.983884361
2289216.02674737521089.6384106282288493.52811568521447.489791956
#Sta/Elev= 30
       0 2526.23    36.3 2526.15    73.3 2523.25    90.5 2519.71   133.8 2505.98
   248.3 2497.74   253.6 2496.47   266.3 2486.58   275.3 2482.71   288.9 2479.94
   478.3 2479.97   502.6 2482.66   517.5 2483.42   529.3 2486.81   703.8 2485.21
   834.4 2487.02  1008.6 2485.73  1121.9 2488.19    1270 2487.38  1383.4 2483.69
  1459.4 2485.27  1490.7 2479.44  1502.9 2482.92  1514.8 2489.66  1530.8  2489.4
  1535.3 2491.32  1544.6 2499.27  1562.1 2505.64  1583.5  2516.3  1649.8 2556.12
#Mann= 3 ,-1,0
       0      .1       0   275.3    .035       0   502.6      .1       0
#XS Ineff= 2 , 0
                         1513.01         2499.07
Permanent Ineff=
       F       F
Bank Sta=275.3,502.6
XS Rating Curve= 0 ,0
Exp/Cntr=0.3,0.1

Type RM Length L Ch R = 1 ,281114  ,227.9,222.2,217.2
XS GIS Cut Line= 2
2290117.87182632520535.1894793992288504.63348384521384.375536992
#Sta/Elev= 30
       0    2523      56 2515.52    96.8  2503.8     176 2491.04   390.7 2489.03
   425.1 2486.21   440.4 2488.96   485.6 2489.22   503.2 2480.43   523.9 2481.41
   532.8 2479.25   634.8 2479.17   648.3 2481.25   680.9 2483.56     717 2481.56
     760 2483.03   787.5 2479.45   811.2 2483.78   874.3 2482.53   914.9 2486.88
   964.7 2484.46  1308.3 2488.13  1529.8 2484.18  1665.4 2484.78    1696 2479.29
  1714.4 2483.17  1726.3 2489.74  1742.2 2489.25  1764.7 2502.02  1823.1 2528.31
#Mann= 3 ,0,0
       0      .1       0   523.9    .035       0   648.3      .1       0
#XS Ineff= 2 , 0
          460.85 2498.42
Permanent Ineff=
       F       F
Bank Sta=523.9,648.3
XS Rating Curve= 0 ,0
Exp/Cntr=0.3,0.1

Type RM Length L Ch R = 1 ,280892  ,785.7,754.9,765.2
XS GIS Cut Line= 3
 2289999.9650784520296.8175374492289252.51183832520765.404431075
2288434.19911677521249.991852776
#Sta/Elev= 30
       0 2527.91   131.9 2513.03   182.9 2494.12     198 2491.62   245.2 2488.24
   419.9 2488.13   471.9 2480.25   525.3 2483.99   542.8 2482.86   547.1 2480.46
   658.8  2478.8   673.3 2480.44   783.9 2481.42   866.7 2477.81   889.6 2481.83
   917.3 2483.21  1045.3 2478.27  1060.4 2484.13  1110.4  2485.6  1235.6  2483.1
  1273.5 2485.49    1548 2482.55  1598.5 2483.92  1626.4 2479.71  1686.8 2479.46
  1714.7 2488.45  1742.6 2489.15  1756.5 2497.81  1804.9 2519.77  1833.2 2530.01
#Mann= 3 ,0,0
       0      .1       0   547.1    .035       0   673.3      .1       0
#XS Ineff= 2 , 0
          413.52 2499.64
Permanent Ineff=
       F       F
Bank Sta=547.1,673.3
XS Rating Curve= 0 ,0
Exp/Cntr(USF)=0,0
Exp/Cntr=0.3,0.1

Type RM Length L Ch R = 1 ,280137  ,582.1,611,451.7
XS GIS Cut Line= 2
2289628.97879965 519762.04557749 2288173.4610983521060.926440118
#Sta/Elev= 30
       0 2523.91    86.9 2506.98   102.9 2498.68   124.4 2492.95   161.9 2492.09
   199.4 2503.23   277.6 2499.79   305.1 2481.62   345.6 2475.23   464.6 2479.78
   575.4 2477.46   735.6 2481.33   762.4 2476.84   791.7 2481.12   881.8 2483.58
   929.9  2479.5  1068.1 2480.16  1105.5 2477.32  1201.1 2475.16  1232.3 2477.58
  1242.3  2482.8  1512.8 2479.63  1604.1 2482.97  1644.8 2475.89  1695.2 2476.15
  1730.9 2487.29  1750.7 2487.53  1793.2 2520.45    1837 2547.69  1950.8 2592.35
#Mann= 4 ,-1,0
       0      .1       0    1080    .025       0  1105.5    .035       0
  1232.3      .1       0
Bank Sta=1105.5,1232.3
XS Rating Curve= 0 ,0
Exp/Cntr(USF)=0,0
Exp/Cntr=0.3,0.1

Type RM Length L Ch R = 1 ,279526  ,746.9,645.8,349.2
XS GIS Cut Line= 3
2289339.80309739519648.7850941072288566.25809386520022.303709519
 2288161.4121107 521036.82846493
#Sta/Elev= 30
       0 2521.57    30.7 2517.87    70.7 2505.26   102.1 2500.12   159.5 2498.32
   186.1 2481.15   226.1 2475.43   359.7 2481.91   568.2 2478.15   641.1 2480.86
     657 2476.39   750.3 2475.62   812.5 2479.19   918.2 2474.87   933.6 2473.74
  1010.9 2475.92  1037.3 2479.61  1149.1 2478.34  1241.1 2474.18    1254 2481.31
  1322.9 2482.32  1538.3  2481.2  1570.8 2475.09  1628.7 2480.37  1723.4 2479.77
    1745 2486.96  1766.5 2487.59  1792.5 2507.85  1852.6 2543.69  1951.3 2583.41
#Mann= 6 ,-1,0
       0      .1       0     657    .035       0   750.3      .1       0
   918.2    .035       0  1010.9     .08       0  1149.1      .1       0
Bank Sta=657,1010.9
XS Rating Curve= 0 ,0
Exp/Cntr(USF)=0,0
Exp/Cntr=0.3,0.1

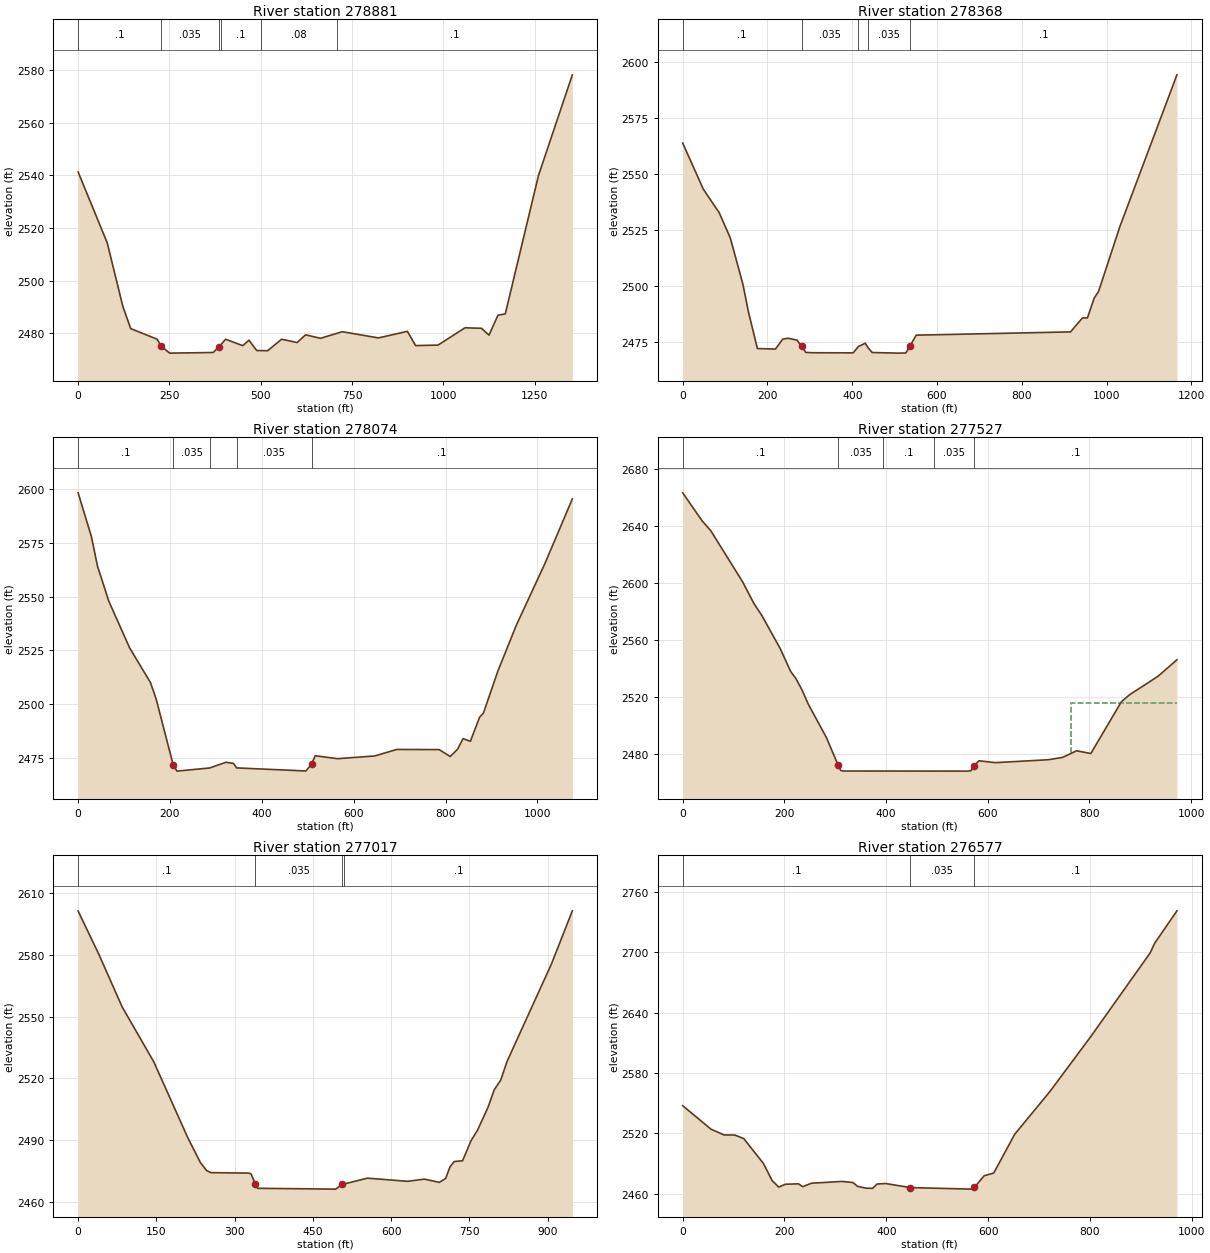
Type RM Length L Ch R = 1 ,278881  ,465.6,512.7,509.7
XS GIS Cut Line= 3
2288028.87324717519725.8986147082288277.08239161520405.461515007
2288139.72393303521019.959882298
#Sta/Elev= 30
       0 2541.24    79.6 2514.36   122.7 2490.06     144 2481.75   216.4 2477.73
   226.6 2475.21   250.5 2472.44   369.7 2472.68   385.7 2474.84   403.8 2477.71
   450.6 2475.28   467.7 2477.35     489 2473.43   518.8 2473.35   557.1 2477.72
   599.7 2476.46   622.7  2479.4   663.6 2478.07   723.2 2480.57   822.2 2478.22
   901.5 2480.72     924 2475.31   985.3 2475.49  1059.3 2482.07  1104.4 2481.87
  1124.9 2479.26  1149.4 2486.84  1169.5 2487.35  1260.3 2539.88  1353.1 2578.15
#Mann= 6 ,-1,0
       0      .1       0   226.6    .035       0   385.7    .025       0
     390      .1       0     500     .08       0     710      .1       0
Bank Sta=226.6,385.7
XS Rating Curve= 0 ,0
Exp/Cntr(USF)=0,0
Exp/Cntr=0.3,0.1

Type RM Length L Ch R = 1 ,278368  ,278.4,294,295.9
XS GIS Cut Line= 4
2287579.31375962519839.6595924482287666.17376917520077.381723848
2287741.60483009520356.2480702992287748.46219927520980.268665226
#Sta/Elev= 30
       0 2563.67    48.6  2543.1    86.1 2532.59   112.3  2521.3   142.2 2500.51
   154.9 2488.43   176.2 2471.93   218.8  2471.7   235.8  2476.1   248.6 2476.52
   269.5 2475.69  280.48 2472.98   290.4 2470.19   306.7 2470.06   402.1    2470
   414.4 2472.81   430.7 2474.31   437.2 2472.32     447 2470.15     509 2469.88
   526.4 2469.94  536.33 2473.11   550.9  2477.9   914.9 2479.36   942.9 2485.56
   954.9 2485.62   970.9  2494.5   981.2 2497.45  1030.9 2526.13    1166 2594.16
#Mann= 5 ,-1,0
       0      .1       0  280.48    .035       0   414.4      .1       0
   437.2    .035       0  536.33      .1       0
Bank Sta=280.48,536.33
XS Rating Curve= 0 ,0
Exp/Cntr(USF)=0,0
Exp/Cntr=0.3,0.1

Type RM Length L Ch R = 1 ,278074  ,486.2,547.4,554.1
XS GIS Cut Line= 4
2287346.16320767519908.2332841982287419.30847887520205.385948449
2287476.45322199  520575.68388392287483.31059117520971.125506326
#Sta/Elev= 30
       0 2598.37    28.9 2577.99    42.1  2564.3    66.9 2547.88   112.2 2526.17
   157.5 2510.05   169.9 2502.39   206.9 2471.81   215.2 2468.81   286.7 2470.29
     322 2472.94   338.2 2472.41   345.2 2470.31     496 2468.88   508.2 2472.05
   516.3 2475.98   564.8  2474.6   645.8 2475.87   694.2 2478.91   786.2 2478.83
   810.2 2475.62   826.2 2478.99   838.2 2483.96   854.2 2482.71   874.2 2493.89
   882.5 2495.79   914.2 2515.47   954.2 2536.74  1016.2 2565.32  1076.2 2595.55
#Mann= 5 ,-1,0
       0      .1       0   206.9    .035       0   286.7      .1       0
   345.2    .035       0   508.2      .1       0
Bank Sta=206.9,508.2
XS Rating Curve= 0 ,0
Exp/Cntr(USF)=0,0
Exp/Cntr=0.3,0.1

Type RM Length L Ch R = 1 ,277527  ,469.7,509.8,520
XS GIS Cut Line= 3
2287017.00948727519935.6627608982286925.57789827520120.811728623
2286934.72105717  520886.5512865
#Sta/Elev= 30
       0 2663.31      38  2643.7    55.2 2636.69   117.7 2600.83     140 2585.53
   155.5 2577.16   191.6 2553.96   212.3 2537.75   222.9 2532.62   234.9 2524.56
   246.9 2514.82   282.9 2491.08   305.5 2472.03   310.9 2468.12   314.9 2467.69
   394.6 2467.66   495.2 2467.63   558.9 2467.61   566.9 2467.83   573.1 2471.33
   582.9 2474.89   614.9 2473.57   718.9 2475.62     747 2477.22   774.9 2481.91
   802.9 2479.99   862.9 2516.35   878.9 2521.27   934.9 2534.27   972.3 2545.91
#Mann= 5 ,-1,0
       0      .1       0   305.5    .035       0   394.6      .1       0
   495.2    .035       0   573.1      .1       0
#XS Ineff= 2 , 0
                           764.2         2515.24
Permanent Ineff=
       F       F
Bank Sta=305.5,573.1
XS Rating Curve= 0 ,0
Exp/Cntr(USF)=0,0
Exp/Cntr=0.3,0.1

Type RM Length L Ch R = 1 ,277017  ,424.3,439.7,450
XS GIS Cut Line= 2
2286511.84995804519889.9469663982286358.70204647520824.834963925
#Sta/Elev= 30
       0 2601.38    39.8 2580.33    84.3 2554.82   144.9 2528.16     210 2491.32
   234.3 2479.16   246.3 2475.23   254.6 2474.23   327.5 2474.01   331.6 2473.54
   339.7 2468.72   343.8 2466.62   493.6 2466.22   505.9 2468.47   554.5 2471.55
   631.5 2470.02     664 2471.09   692.3 2469.51   704.5 2471.43   712.6 2476.94
   720.7 2479.63   736.9 2480.01   753.1 2489.76   765.4 2494.81   785.6 2505.96
   797.7 2514.58   809.9 2519.15     822 2528.19   907.2 2575.64   947.3 2601.48
#Mann= 4 ,-1,0
       0      .1       0   339.7    .035       0   505.9    .025       0
     510      .1       0
Bank Sta=339.7,505.9
XS Rating Curve= 0 ,0
Exp/Cntr(USF)=0,0
Exp/Cntr=0.3,0.1

Type RM Length L Ch R = 1 ,276577  ,454.7,490.1,517.3
XS GIS Cut Line= 2
2286199.90215286519857.430429775     2285846.644      520762.005
#Sta/Elev= 30
       0 2547.49    55.6 2524.12    81.3  2518.4   102.8 2518.29     120 2514.74
   158.6 2490.05   175.8  2472.9   188.7 2466.55   201.6 2469.36   227.3 2469.77
   235.9 2466.98   253.1 2470.38   313.2 2472.17   334.7 2471.04   343.3 2467.32
   360.4 2465.43   373.3 2465.31   381.9 2469.61   399.1 2470.05   447.4 2466.03
   566.6  2464.5  572.992466.122   592.3 2477.79   611.1 2480.47   652.4 2519.12
   721.2 2561.39     802 2616.39   918.7 2699.64   927.3 2709.06   971.1 2741.33
#Mann= 3 ,-1,0
       0      .1       0   447.4    .035       0  572.99      .1       0
Bank Sta=447.4,572.99
XS Rating Curve= 0 ,0
Exp/Cntr=0.3,0.1