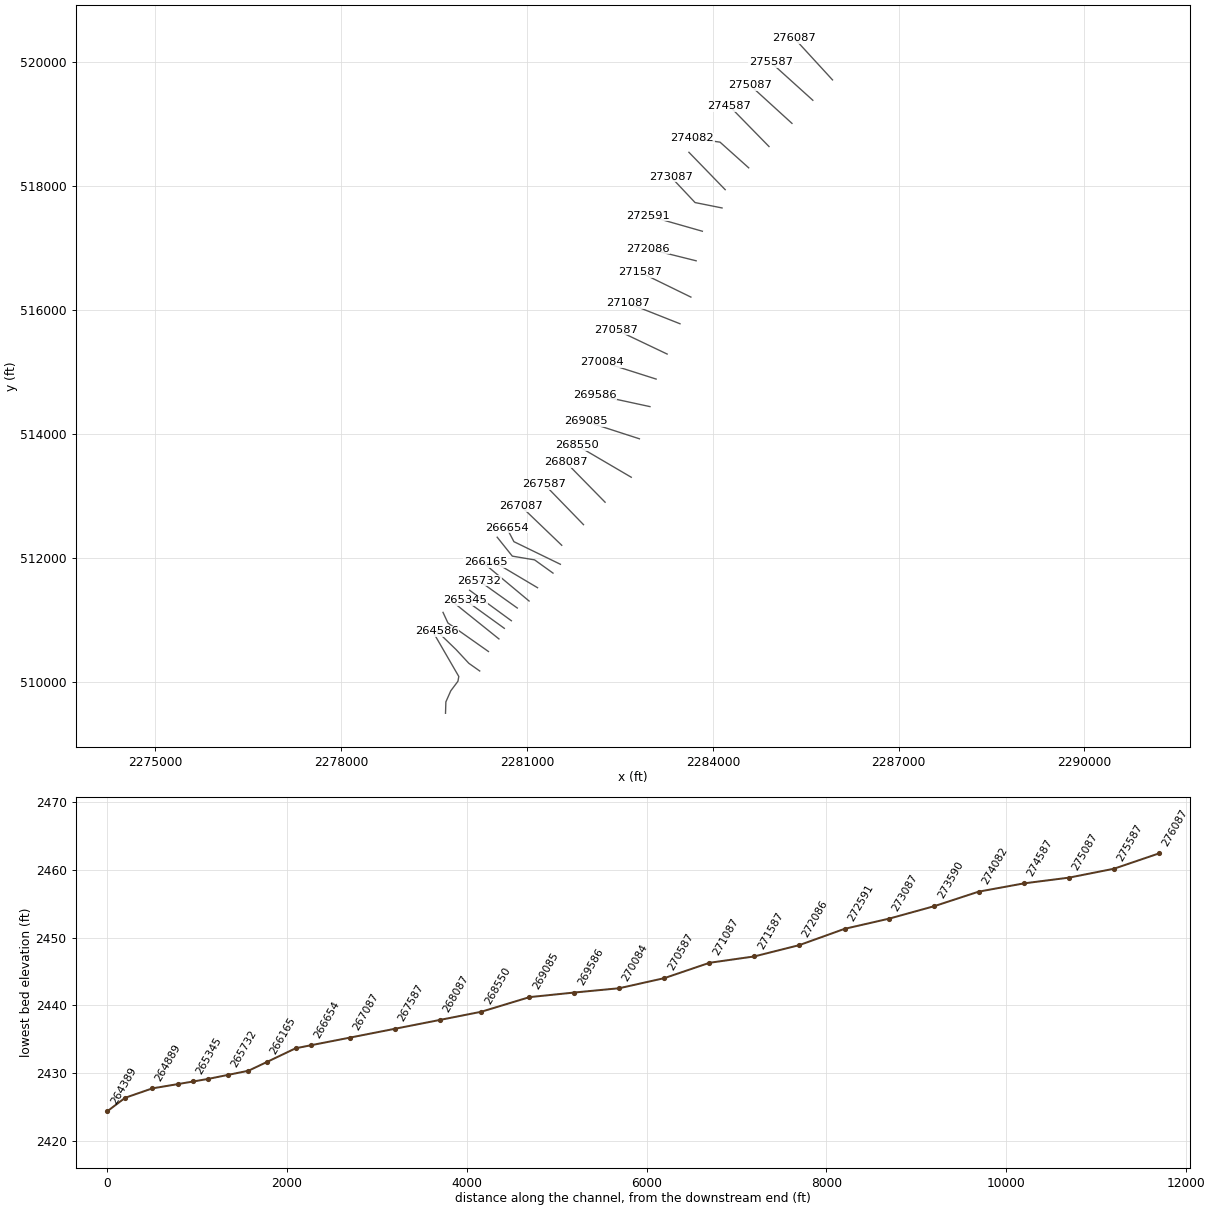
HEC-RAS study GRNBRRRV.prj: GRNBRRRV

--- GRNBRRRV.g01 (geometry) --- (continued)

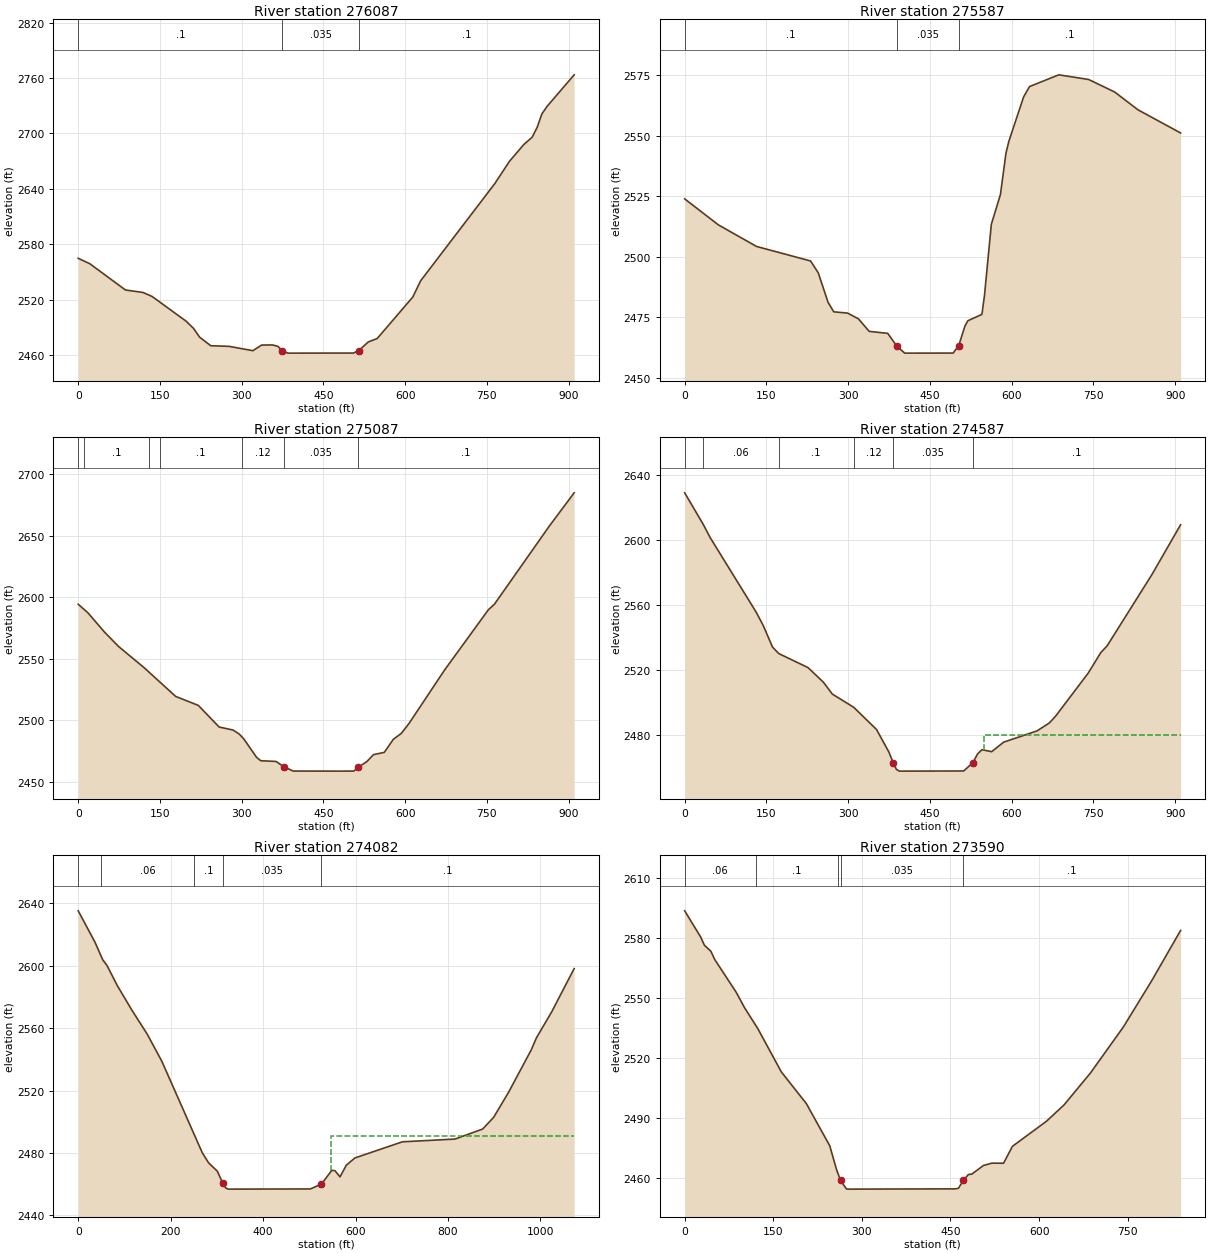
Type RM Length L Ch R = 1 ,276087  ,491.2,500,507.2
XS GIS Cut Line= 2
      2285932.03      519709.332      2285316.06      520379.168
#Sta/Elev= 30
       0 2564.98    21.5 2559.02    86.7 2530.67   118.7 2528.03   135.7 2523.62
     198 2496.94   211.7  2489.1   222.6 2479.75   243.2 2470.37   276.9 2469.69
   320.4 2465.02   336.6 2471.08   356.5 2471.23   366.2 2469.77   374.7 2464.87
   384.8 2462.37   505.2 2462.44     515 2465.19   532.3 2474.51   548.6 2478.15
   613.9 2523.05   628.3 2540.59   764.1 2645.55   791.6 2670.12   817.9 2688.18
     833    2696   842.1 2706.59   850.7 2721.05   860.4 2729.39     910 2763.46
#Mann= 3 ,-1,0
       0      .1       0   374.7    .035       0     515      .1       0
Bank Sta=374.7,515
XS Rating Curve= 0 ,0
Exp/Cntr=0.3,0.1

Type RM Length L Ch R = 1 ,275587  ,500.6,500,499.8
XS GIS Cut Line= 2
     2285614.254      519380.995     2284938.148      519990.077
#Sta/Elev= 30
       0 2523.86      62 2513.09   131.9 2504.19     231  2498.2   245.1  2493.3
   263.2 2481.08   273.5 2477.19   298.9 2476.66   318.8 2474.29   338.6 2469.11
   372.6 2468.29   389.6 2462.93   403.8 2460.12   492.7 2460.14   502.9 2463.27
   514.2 2471.28   519.6  2473.5   545.4 2476.13   550.1 2483.93   562.7 2513.36
   579.4 2525.67   589.6 2542.82     595 2547.77   621.9 2565.96   632.7 2570.25
   686.5 2575.11   741.3 2573.18     789 2568.01   831.9 2560.64     910 2551.08
#Mann= 3 ,0,0
       0      .1       0   389.6    .035       0   502.9      .1       0
Bank Sta=389.6,502.9
XS Rating Curve= 0 ,0
Exp/Cntr=0.3,0.1

Type RM Length L Ch R = 1 ,275087  ,505.5,500,495.7
XS GIS Cut Line= 2
     2285277.154      519008.893     2284603.858      519621.079
#Sta/Elev= 30
       0 2594.32    17.5 2587.53      49 2571.34    74.5 2559.85   120.3 2543.07
   178.8 2519.49   220.4 2512.18   258.6 2494.62   284.1 2492.19   295.4 2488.95
   303.7 2485.06   327.4 2469.94     335 2467.27   363.1 2466.66   377.5 2462.33
   394.5 2458.87   482.3 2458.81   505.8 2458.86   513.4 2461.83   529.6 2466.54
   541.7 2472.17   561.6 2474.04   578.5 2484.79   592.7 2489.38   606.9 2497.44
   672.3 2540.94   752.8 2589.97   763.6 2594.27   864.5 2657.83     910  2684.8
#Mann= 7 ,-1,0
       0     .06       0      10      .1       0     130     .06       0
     150      .1       0     300     .12       0   377.5    .035       0
   513.4      .1       0
Bank Sta=377.5,513.4
XS Rating Curve= 0 ,0
Exp/Cntr=0.3,0.1

Type RM Length L Ch R = 1 ,274587  ,501.8,504.7,510.8
BEGIN DESCRIPTION:
c/e of 0.5/0.7 added to correct drawdown between the 100-500 yr events
END DESCRIPTION:
XS GIS Cut Line= 2
     2284906.619      518635.753     2284269.376      519285.385
#Sta/Elev= 30
       0 2629.18    33.9 2609.87    46.8 2601.62   130.9 2555.94   144.2 2547.53
   161.1 2534.34   172.5 2530.32   226.3 2521.67   254.5 2512.69   270.9 2505.39
   310.2 2497.24   351.9 2483.64   374.8 2469.68     383 2462.79   388.6    2459
   394.2 2457.97   511.9 2458.06     529 2463.22   537.3  2468.5   545.5 2471.16
   563.3 2469.93   585.4 2475.82   646.4 2482.69   668.8 2487.51     680 2491.52
   740.4 2518.25   763.6 2530.91   775.2 2535.06     857  2578.7     910 2609.54
#Mann= 6 ,-1,0
       0      .1       0    33.9     .06       0   172.5      .1       0
   310.2     .12       0     383    .035       0     529      .1       0
#XS Ineff= 2 , 0
       0                   548.6       0    2480
Permanent Ineff=
       F       F
Bank Sta=383,529
XS Rating Curve= 0 ,0
Exp/Cntr=0.7,0.5

Type RM Length L Ch R = 1 ,274082  ,500.9,492.2,482.4
XS GIS Cut Line= 3
     2284578.635      518292.6012284115.36207666 518706.55426426
2283667.80704564518768.567541429
#Sta/Elev= 30
       0 2635.26    36.1 2615.26    53.1 2603.85    62.3 2600.21    84.3 2587.45
   115.9 2571.68   149.5 2556.07     181 2538.74   268.4 2480.13   282.2 2473.58
     301 2468.26     313 2460.47   319.4  2457.4   325.2 2456.75   502.2 2456.86
   526.2 2459.95   548.9 2468.87   555.8  2468.5   566.5 2464.61   580.1  2472.1
   598.7 2476.75   701.6 2487.11   815.3 2488.86   875.1 2495.29   899.1 2502.87
   931.4 2518.97   979.9 2545.86   991.7  2553.9  1024.3 2570.35  1073.1  2598.2
#Mann= 5 ,-1,0
       0      .1       0      50     .06       0     250      .1       0
     313    .035       0   526.2      .1       0
#XS Ineff= 2 , 0
                          547.61         2490.95
Permanent Ineff=
       F       F
Bank Sta=313,526.2
XS Rating Curve= 0 ,0
Exp/Cntr=0.3,0.1

Type RM Length L Ch R = 1 ,273590  ,499.1,503.4,502.7
XS GIS Cut Line= 2
2284199.04141648517940.7503748962283613.68345845518542.712666844
#Sta/Elev= 30
       0 2593.58    27.1  2580.5    33.4 2576.39    44.3 2573.42    50.8 2569.31
    87.2 2552.93     101 2545.39     124 2534.68   163.6 2513.17     206 2497.33
   245.6 2476.27   257.2 2464.29  263.94 2458.96   273.9 2454.69   279.5 2454.62
   458.1 2454.75   463.4 2455.03   471.9    2459   480.3 2461.93   486.1  2462.1
   505.8 2466.44     520 2467.59   539.8 2467.55   554.9    2476   612.3 2488.47
   642.2 2496.66   686.9 2512.59   742.7 2535.59   790.2 2558.45   839.6 2583.79
#Mann= 5 ,-1,0
       0     .06       0     120      .1       0     260     .12       0
  263.94    .035       0   471.9      .1       0
Bank Sta=263.94,471.9
XS Rating Curve= 0 ,0
Exp/Cntr=0.3,0.1

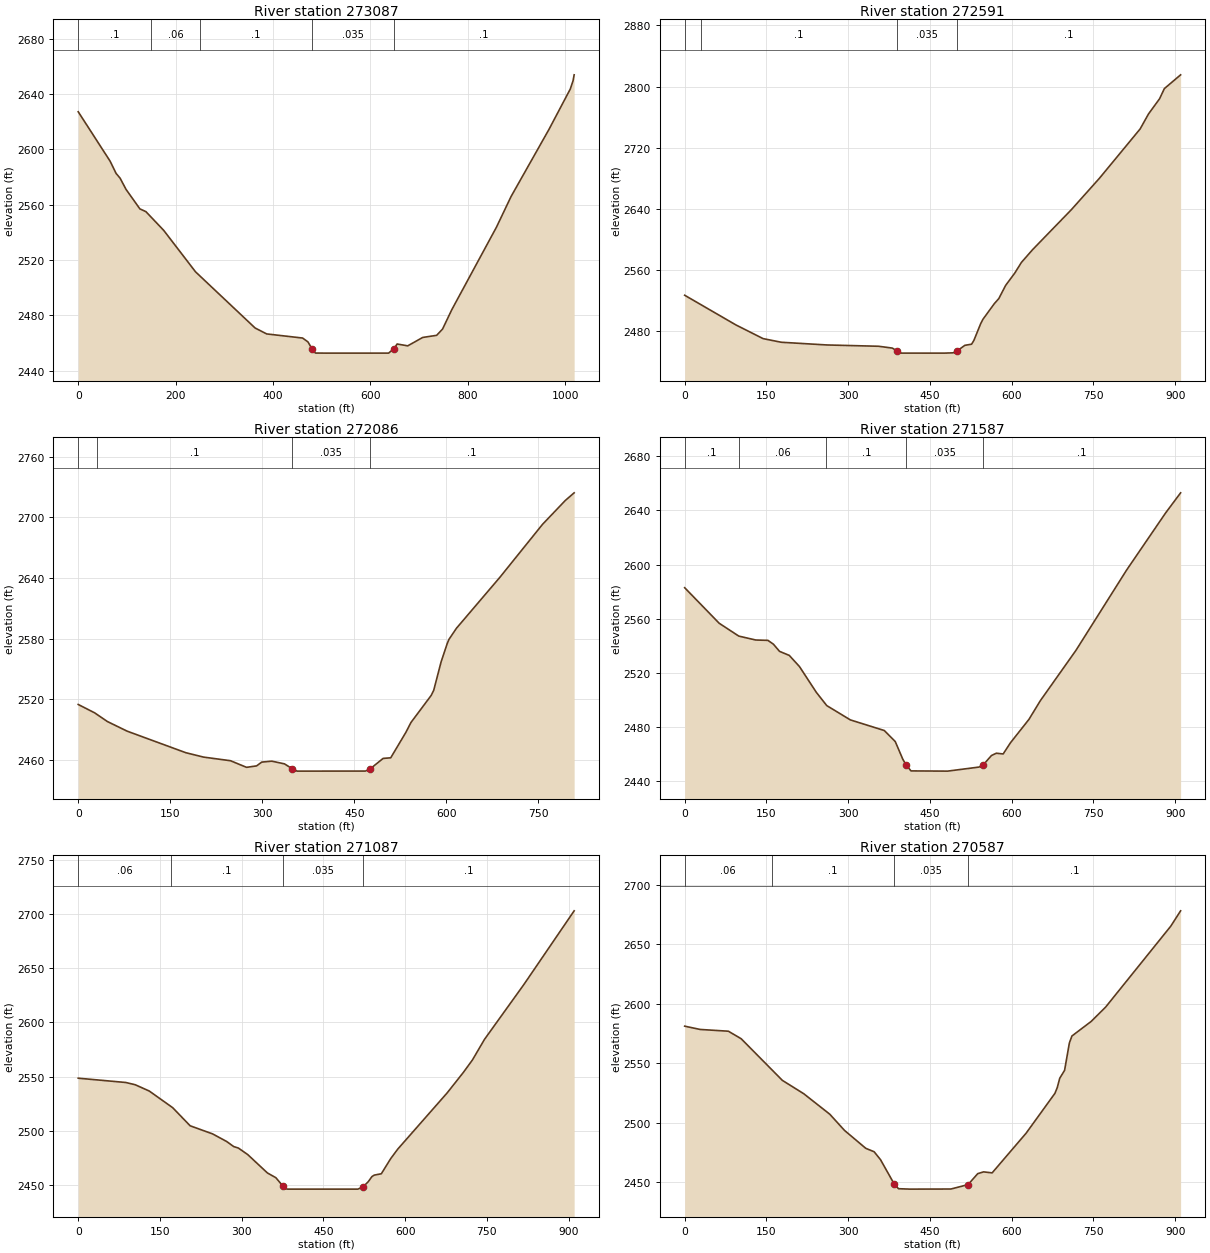
Type RM Length L Ch R = 1 ,273087  ,443,495.2,543.9
XS GIS Cut Line= 3
 2284148.4707891517646.0718387212283712.92589102517732.996066669
     2283318.594      518150.812
#Sta/Elev= 30
       0 2627.17    65.6 2591.42    77.8 2582.61      86  2579.2    98.2  2571.1
   126.7 2556.98     139 2555.02   175.7 2541.43   240.9 2511.54   363.3 2470.94
   387.1 2466.65   460.9 2463.68   471.9 2460.86   480.2 2455.89   487.2 2452.84
   509.3 2452.78   637.5 2452.79   648.5 2456.03     655 2459.37   676.8 2458.04
   707.5  2464.1   736.2 2465.64   748.3 2470.16   767.4 2484.23     859 2543.76
     889  2565.9   966.9 2614.42  1010.7 2643.61  1016.4 2649.59  1018.6 2653.84
#Mann= 5 ,-1,0
       0      .1       0     150     .06       0     250      .1       0
   480.2    .035       0   648.5      .1       0
Bank Sta=480.2,648.5
XS Rating Curve= 0 ,0
Exp/Cntr=0.3,0.1

Type RM Length L Ch R = 1 ,272591  ,502.7,505.1,506
XS GIS Cut Line= 2
     2283830.561      517270.784     2282955.343      517520.133
#Sta/Elev= 30
       0 2527.01      94 2488.18   143.9 2470.26   177.2 2465.51   260.3 2461.98
     356 2460.25     381 2457.87   389.3 2454.29   397.6 2451.31   475.9 2451.28
   492.7 2451.67   500.2 2454.29   514.1 2461.49   526.5 2462.97   530.7 2467.98
   543.2  2489.9   547.3 2495.58   568.1 2515.93   576.4 2522.65   588.9 2539.86
   605.6 2555.92     618 2570.08   638.8 2586.96   709.5 2638.93   761.3 2680.27
   835.8 2744.64     851  2764.1   871.4 2784.08   880.1 2797.29     910 2815.38
#Mann= 4 ,-1,0
       0     .06       0      30      .1       0   389.3    .035       0
   500.2      .1       0
Bank Sta=389.3,500.2
XS Rating Curve= 0 ,0
Exp/Cntr=0.3,0.1

Type RM Length L Ch R = 1 ,272086  ,512,499.4,473.7
XS GIS Cut Line= 2
2283730.31284299516794.6556629532282946.10493091516989.826344725
#Sta/Elev= 30
       0 2514.86    26.9 2506.53    47.5 2497.98    79.8 2488.42   175.3 2467.12
   204.2 2462.77   248.1 2459.18   274.3 2452.63   290.7 2454.07     299 2457.81
   315.5 2458.73   336.1 2456.07   348.5 2451.29   356.7 2448.88     468 2448.94
475.93052451.199   496.8 2461.46   509.2 2462.06   533.9 2487.23   542.2 2497.03
   575.2 2523.84   579.3 2528.94   591.3 2556.98   601.3 2575.19     604 2579.18
   616.4 2590.34   687.1 2640.72   756.5 2693.08   793.6  2716.7   808.1 2724.32
#Mann= 4 ,-1,0
       0     .06       0      30      .1       0   348.5    .035       0
475.9305      .1       0
Bank Sta=348.5,475.9305
XS Rating Curve= 0 ,0
Exp/Cntr=0.3,0.1

Type RM Length L Ch R = 1 ,271587  ,495.5,500,509.1
XS GIS Cut Line= 2
     2283645.429      516209.784     2282827.474      516608.596
#Sta/Elev= 30
       0 2582.87    63.3 2556.59    99.3 2547.08   130.4 2544.19   152.7 2543.94
   162.9 2541.08     174 2535.81   191.9 2532.82   210.6 2524.58   241.7 2505.41
   260.7 2495.69     304 2485.11   366.3 2477.25   386.4 2469.08   400.2 2456.06
   406.4 2451.72   415.3 2447.38   482.4 2447.22   539.9 2450.21   547.9 2451.89
   562.9 2458.76   571.9 2460.47   584.4 2459.92   597.7 2468.15   631.7 2485.49
   652.6 2499.32   717.9 2536.51   810.9 2595.93   882.5  2638.2     910 2653.05
#Mann= 5 ,-1,0
       0      .1       0     100     .06       0     260      .1       0
   406.4    .035       0   547.9      .1       0
Bank Sta=406.4,547.9
XS Rating Curve= 0 ,0
Exp/Cntr=0.3,0.1

Type RM Length L Ch R = 1 ,271087  ,506.3,500,494.2
XS GIS Cut Line= 2
     2283469.482      515779.978     2282623.165      516114.414
#Sta/Elev= 30
       0 2548.56    87.4 2544.59   104.6 2542.52   130.4 2536.72   173.4 2521.35
   205.4 2504.68   246.6  2497.2   272.4  2490.2   285.3 2485.53   293.9 2484.15
   311.1 2478.11   347.2 2461.18   362.7 2456.81   375.6  2449.1   379.9 2446.67
   384.2 2446.28   513.2 2446.28   522.9 2448.51   532.2 2453.14     539 2457.87
   543.3 2459.21   556.2 2460.45   573.4 2474.42   586.3 2483.15   677.1 2535.07
   706.8 2553.95   723.3 2565.32   745.5 2584.37     818  2635.1     910 2702.87
#Mann= 4 ,-1,0
       0     .06       0     170      .1       0   375.6    .035       0
   522.9      .1       0
Bank Sta=375.6,522.9
XS Rating Curve= 0 ,0
Exp/Cntr=0.3,0.1

Type RM Length L Ch R = 1 ,270587  ,492,502.6,513.1
XS GIS Cut Line= 2
     2283261.828      515292.041     2282439.863      515682.519
#Sta/Elev= 30
       0 2581.19    28.4 2578.43    80.2 2576.94   103.7  2570.6   179.2 2535.58
   218.3 2524.39   266.3 2507.07   293.3 2493.44   332.3 2478.38   347.6  2475.5
   359.4 2468.78   384.9 2447.97   392.4 2444.38   413.4 2444.03   488.5 2444.12
     520 2447.84   537.7 2457.05   548.5 2458.55   564.2 2457.72   626.6 2491.17
   679.4 2524.67   683.6 2529.43   688.2 2537.35   697.1 2544.04   705.9 2567.08
   710.6 2572.93   745.8 2585.15   772.4 2597.24   891.9 2665.33     910 2678.27
#Mann= 4 ,-1,0
       0     .06       0     160      .1       0   384.9    .035       0
     520      .1       0
Bank Sta=384.9,520
XS Rating Curve= 0 ,0
Exp/Cntr=0.3,0.1

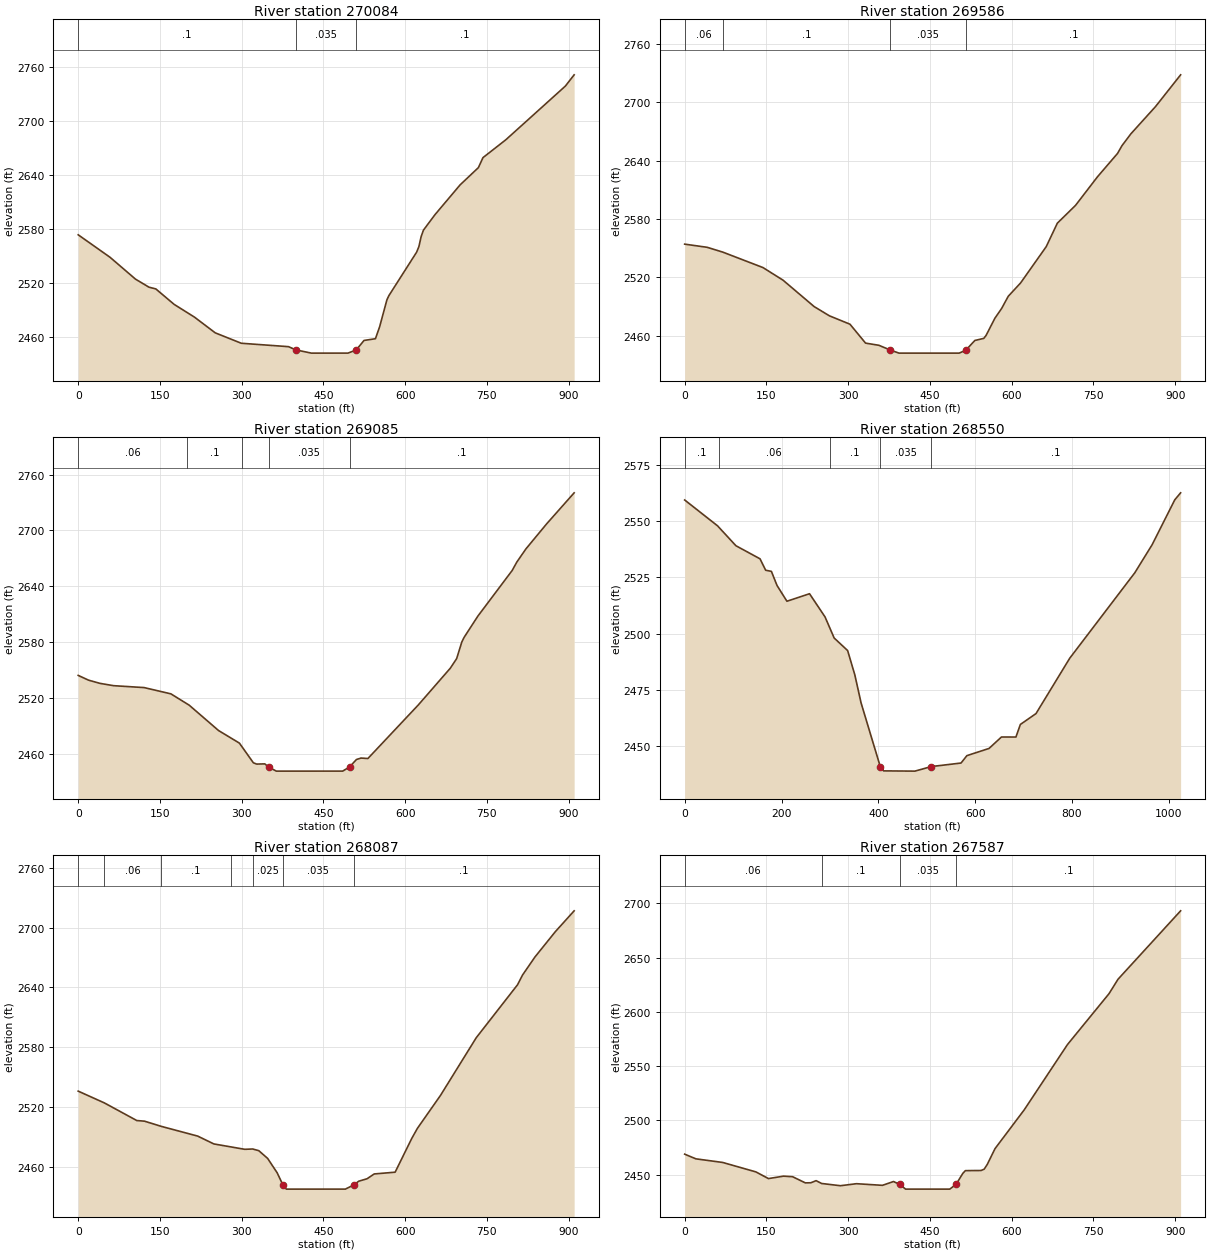
Type RM Length L Ch R = 1 ,270084  ,491.5,498.3,505.5
XS GIS Cut Line= 2
     2283083.925      514888.945     2282216.679      515164.741
#Sta/Elev= 30
       0 2574.02    58.5 2548.99   105.1 2524.76   129.9  2515.8   142.4 2513.89
     176 2496.72   213.4 2482.51   251.5 2465.05   299.3  2453.5   385.9 2449.72
   399.3 2446.15   427.9 2442.54     495 2442.56  510.16 2446.05   524.4 2456.62
   545.4 2458.55   553.2 2472.08   566.4  2501.7     570 2506.38     621 2554.76
   625.1 2560.89   629.3 2572.12   633.5 2579.22   654.5 2596.29   700.7 2629.47
   734.3 2648.67   742.7 2659.76   784.7 2679.65   893.8 2739.22     910 2751.78
#Mann= 3 ,0,0
       0      .1       0   399.3    .035       0  510.16      .1       0
Bank Sta=399.3,510.16
XS Rating Curve= 0 ,0
Exp/Cntr=0.3,0.1

Type RM Length L Ch R = 1 ,269586  ,510.8,500.8,492.7
XS GIS Cut Line= 2
     2282984.553      514445.055     2282095.083      514637.274
#Sta/Elev= 30
       0 2554.12    41.3 2550.86      70  2545.9   143.6 2530.02   180.4 2517.06
   237.7 2489.77   265.7 2480.29   303.3 2471.69   331.9 2452.22   356.4 2449.97
   377.3 2445.08   393.3 2441.91   503.7 2441.91     516 2444.97   532.4 2454.93
   548.8 2457.09   552.9 2459.98   569.2 2477.83   581.5  2487.8   593.8 2500.49
   616.4 2514.18   663.4 2551.53   683.8  2575.7   717.2 2594.04   757.3 2623.35
   794.3 2647.55   802.5 2655.59   818.9  2667.8   863.9 2695.72     910 2728.45
#Mann= 4 ,-1,0
       0     .06       0      70      .1       0   377.3    .035       0
     516      .1       0
Bank Sta=377.3,516
XS Rating Curve= 0 ,0
Exp/Cntr=0.3,0.1

Type RM Length L Ch R = 1 ,269085  ,548.5,535.4,521.9
XS GIS Cut Line= 2
     2282814.035      513926.678     2281947.994      514206.439
#Sta/Elev= 30
       0 2544.12    18.8 2539.05    39.8 2535.58      65 2533.07     121 2531.02
   170.1 2524.29   203.6 2512.15   257.6 2484.84   295.8 2471.35   321.4  2450.2
   327.5  2448.8   342.4 2449.02   349.8 2445.53   363.5 2441.23   485.4 2441.25
     498 2445.75   510.6 2453.72     519 2455.28   531.6 2454.77   624.1 2512.35
   682.9  2551.9   694.5 2562.19   703.9 2579.94   708.1 2584.96   733.4 2607.83
   796.4 2656.91   804.8 2665.85   821.6 2680.09   859.5 2706.92   910.1 2740.36
#Mann= 5 ,-1,0
       0     .06       0     200      .1       0     300     .12       0
   349.8    .035       0     498      .1       0
Bank Sta=349.8,498
XS Rating Curve= 0 ,0
Exp/Cntr=0.3,0.1

Type RM Length L Ch R = 1 ,268550  ,483.9,462.9,447
XS GIS Cut Line= 2
2282682.75444218 513306.829743912281798.44385955513824.025355338
#Sta/Elev= 30
       0 2559.28    67.9 2547.82   105.9 2538.99   155.6  2533.2   167.3 2528.13
   179.1 2527.64   190.7  2521.4   211.2 2514.39   257.9 2517.72   289.9 2507.45
   308.8 2498.08   336.6 2492.53   351.5 2481.71   364.4  2469.3   404.2 2440.95
   410.8 2439.19   475.6 2439.08   509.4  2441.1   570.8 2442.67     583 2445.95
   628.6 2449.13   654.3  2454.2   684.2 2454.19   693.4 2459.77   725.7 2464.59
   795.4 2489.14   929.8 2527.02   965.6 2539.46  1012.3 2559.34  1024.4 2562.45
#Mann= 5 ,-1,0
       0      .1       0      70     .06       0     300      .1       0
   404.2    .035       0   509.4      .1       0
Bank Sta=404.2,509.4
XS Rating Curve= 0 ,0
Exp/Cntr=0.3,0.1

Type RM Length L Ch R = 1 ,268087  ,505.5,500,499.9
BEGIN DESCRIPTION:
channel burned 0.73' for transition from approximate to detailed reach:
lidar = 2438.6
interpolated = 2437.87
END DESCRIPTION:
XS GIS Cut Line= 2
     2282259.937      512904.929     2281621.779      513553.662
#Sta/Elev= 30
       0 2536.09    48.1 2524.26   107.5 2506.62   121.6 2505.99   152.7 2500.74
   219.2 2491.03   248.9 2483.17     280 2480.21   305.5 2477.78   320.2  2478.1
   331.4  2476.4   347.6 2468.65   365.1 2454.21   375.6 2442.08   381.8 2437.87
   490.2 2437.89   505.3 2441.97   514.8 2445.81   530.1 2448.29   543.1 2453.08
   581.5 2454.85   611.9 2488.54   622.3 2498.72   664.7 2531.77   730.4 2589.66
   806.1 2642.69   815.3 2652.48   838.1 2670.58   875.7 2696.07     910 2716.83
#Mann= 7 ,-1,0
       0      .1       0    48.1     .06       0   152.7      .1       0
     280     .12       0   320.2    .025       0   375.6    .035       0
   505.3      .1       0
Bank Sta=375.6,505.3
XS Rating Curve= 0 ,0
Exp/Cntr=0.3,0.1

Type RM Length L Ch R = 1 ,267587  ,502.7,500,503.8
BEGIN DESCRIPTION:
channel burned 1.43' for transition from approximate to detailed reach:
lidar = 2438
interpolated = 2436.57
c/e of 0.5/0.7 used to correct drawdown
END DESCRIPTION:
XS GIS Cut Line= 2
     2281911.376      512543.247     2281276.822      513195.506
#Sta/Elev= 30
       0  2468.8    20.6 2464.49    69.7 2461.16   130.8 2452.43   153.7 2446.28
   181.3 2448.53     198 2448.02   221.4 2442.33   231.5 2442.44   241.2 2444.37
   251.3 2441.77   285.7 2439.71   315.2 2441.57   362.9 2440.06   383.2 2443.59
   394.7 2440.91   405.3 2436.58   486.4 2436.57   497.9 2440.94   510.5 2451.19
   515.1 2453.61   543.9 2453.75   549.6 2454.97   555.3 2459.42   569.4 2473.84
   623.1 2509.71   702.3 2569.77   778.7 2616.78   795.1 2630.01     910 2693.11
#Mann= 4 ,-1,0
       0     .06       0   251.3      .1       0   394.7    .035       0
   497.9      .1       0
Bank Sta=394.7,497.9
XS Rating Curve= 0 ,0
Exp/Cntr=0.7,0.5

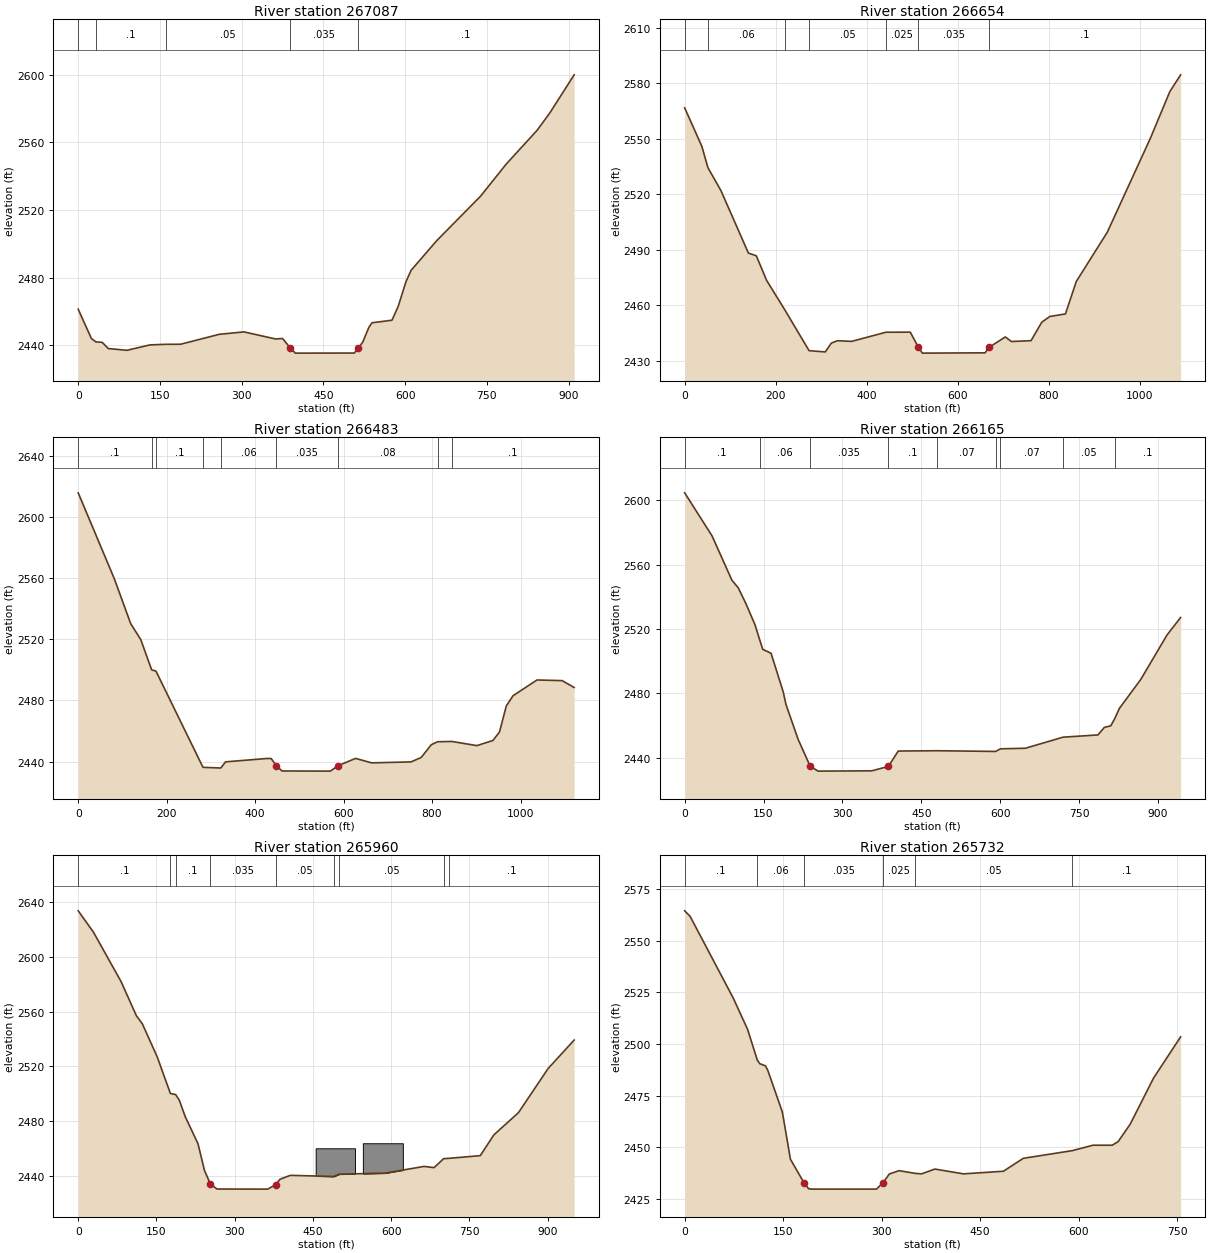
Type RM Length L Ch R = 1 ,267087  ,345.1,433.1,462.1
BEGIN DESCRIPTION:
channel burned 1.76' for transition from approximate to detailed reach:
lidar = 2437.03
interpolated = 2435.27
END DESCRIPTION:
XS GIS Cut Line= 2
     2281559.954      512210.729      2280902.69      512840.097
#Sta/Elev= 30
       0 2461.28    24.2 2443.91    32.5 2441.92      44 2441.65    55.3 2437.97
    89.3 2436.94   131.7 2440.14   160.3 2440.48     188 2440.54     259 2446.42
   304.3 2447.84   362.1 2443.65     375 2443.95   389.2 2438.32   398.4 2435.27
   506.7 2435.32   513.6 2438.12   522.1 2441.79   533.4 2450.58   539.1 2453.25
   575.7 2454.75   587.2 2462.99   601.3 2477.48   610.8  2484.3   657.9 2501.89
   738.1 2528.13   785.2 2547.13   842.2 2567.26   865.3 2577.46     910 2600.04
#Mann= 5 ,-1,0
       0     .06       0    32.5      .1       0   160.3     .05       0
   389.2    .035       0   513.6      .1       0
Bank Sta=389.2,513.6
XS Rating Curve= 0 ,0
Exp/Cntr=0.3,0.1

Type RM Length L Ch R = 1 ,266654  ,128.5,170.4,208.4
BEGIN DESCRIPTION:
channel burned 1.44' for transition from approximate to detailed reach:
lidar = 2435.59
interpolated = 2434.15
END DESCRIPTION:
XS GIS Cut Line= 3
2281538.13606601511904.7040496242280787.98099602512268.923028797
2280669.19187594512495.782549398
#Sta/Elev= 30
       0 2566.74    37.8  2545.9    51.1 2534.39    79.6 2522.05     140 2488.25
   157.5 2486.75     180 2473.52   220.1 2457.53   273.4 2435.48     309  2434.8
   322.3 2439.56   335.7 2440.86     367  2440.5   442.4 2445.45   495.9 2445.48
   513.1 2437.54   522.4 2434.15   660.3 2434.31   669.3  2437.3   704.7  2442.9
   718.1 2440.43   761.2 2440.88   784.8 2450.85   802.6 2453.96   836.9 2455.34
   860.6 2472.84   928.8 2499.48  1023.2 2550.09  1066.3 2575.51    1090 2584.58
#Mann= 7 ,-1,0
       0      .1       0    51.1     .06       0   220.1      .1       0
   273.4     .05       0   442.4    .025       0   513.1    .035       0
   669.3      .1       0
Bank Sta=513.1,669.3
XS Rating Curve= 0 ,0
Exp/Cntr=0.3,0.1

Type RM Length L Ch R = 1 ,266483  ,357,318.7,252.2
BEGIN DESCRIPTION:
start of GRM detailed reach - channel burned 0.64:
lidar invert = 2434.34
effective invert = 2433.70
END DESCRIPTION:
XS GIS Cut Line= 5
2281419.10636355511762.4417602272281121.03407848511975.911614425
2280943.49937513512005.227035806 2280761.8645678512036.079336315
2280517.74235263 512340.89434348
#Sta/Elev= 30
       0 2615.95    81.5 2559.78   118.7 2530.25   141.4 2519.88     166 2500.03
   175.8  2499.2   282.1 2436.18   322.3 2435.74   333.2 2439.78   428.3 2442.01
   436.4 2441.92   448.1 2437.27   460.7  2433.8   570.2  2433.7   586.5 2437.08
     627 2442.04   663.5 2439.11   752.7 2439.75   775.5 2442.65   798.2 2450.97
   812.5 2452.94     845 2453.13   901.3 2450.41   937.7 2453.76   952.6 2459.39
   967.9 2476.38   983.3 2483.11  1037.3 2493.39  1094.2 2492.97  1121.3 2488.47
#Mann= 9 ,-1,0
       0      .1       0     166    .016       0   175.8      .1       0
   282.1     .04       0   322.3     .06       0   448.1    .035       0
   586.5     .08       0   812.5    .016       0     845      .1       0
Bank Sta=448.1,586.5
XS Rating Curve= 0 ,0
Exp/Cntr(USF)=0,0
Minor Loss Coefficient=0
Exp/Cntr=0.3,0.1

Type RM Length L Ch R = 1 ,266165  ,216.2,205.2,173.7
BEGIN DESCRIPTION:
channel burned 0.11':
lidar invert = 2431.80
interpolated invert = 2431.69
END DESCRIPTION:
XS GIS Cut Line= 3
2281169.43474417511526.9809437362280560.87049225511887.789788751
2280329.95283144511933.492242453
#Sta/Elev= 30
       0 2604.54    52.2 2577.71    89.8 2550.26   101.8 2545.57   116.4 2535.75
   133.9 2522.43   142.7 2513.14   148.5  2507.3   164.2 2504.92   187.5 2480.76
   192.5 2473.21   215.6  2451.5   238.6 2434.75   253.6 2431.69   355.8 2431.88
   387.4 2434.63     406 2444.16   480.4 2444.36   591.3 2443.92   600.4 2445.54
   647.7  2445.9   719.5 2452.78   785.7 2454.17   797.9 2458.83   810.1 2459.83
   817.7 2464.33   826.4 2470.61   867.2 2488.67   916.9 2516.17   942.9 2527.12
#Mann= 9 ,-1,0
       0      .1       0   142.7     .06       0   238.6    .035       0
   387.4      .1       0   480.4     .07       0   591.3      .1       0
   600.4     .07       0   719.5     .05       0   817.7      .1       0
Bank Sta=238.6,387.4
XS Rating Curve= 0 ,0
Exp/Cntr(USF)=0,0
Exp/Cntr=0.3,0.1

Type RM Length L Ch R = 1 ,265960  ,221.7,227.6,241.4
BEGIN DESCRIPTION:
channel burned 0.45':
lidar invert = 2430.85
effective invert = 2430.40
END DESCRIPTION:
XS GIS Cut Line= 2
2281032.69923572511312.6698967672280301.86955383511921.324103233
#Sta/Elev= 30
       0 2633.63    29.1 2618.14    82.1 2582.04   111.5 2557.08   122.9 2551.18
   151.3 2527.19   176.8 2500.24   186.9 2499.43   193.9 2495.34   205.2 2483.35
   229.7 2463.59   242.1 2444.13   253.5 2434.09   266.2 2430.47   363.3  2430.4
   378.5 2433.58     387 2437.62   406.7 2440.45     490 2439.65   500.4 2441.32
   588.9 2442.09   663.3 2446.99   682.4 2446.11   700.8 2452.63   710.8 2452.88
   771.1 2454.86   797.1    2470   844.3 2486.25   901.2 2518.48   951.1 2539.26
#Mann= 9 ,-1,0
       0      .1       0   176.8    .016       0   186.9      .1       0
   253.5    .035       0   378.5     .05       0     490     .08       0
   500.4     .05       0   700.8    .016       0   710.8      .1       0
#Block Obstruct= 2 ,-1
   455.4  530.72 2460.22  545.88  622.55  2463.9
Bank Sta=253.5,378.5
XS Rating Curve= 0 ,0
Exp/Cntr=0.7,0.5

Type RM Length L Ch R = 1 ,265732  ,220.6,219.6,217
BEGIN DESCRIPTION:
channel burned 0.83':
lidar invert = 2430.62
interpolated invert = 2429.79
END DESCRIPTION:
XS GIS Cut Line= 2
2280842.30139136511199.8475909222280226.52096253 511637.62898954
#Sta/Elev= 30
       0 2564.35     8.2 2561.73    74.2 2522.04    95.9 2506.99   110.6 2492.19
   114.4 2490.44     123  2489.4   126.6 2487.24   148.8 2467.06   161.1 2444.26
   181.8 2432.83   188.7    2430     194 2429.79   292.2  2429.8     302 2432.84
   311.8 2437.12   326.6 2438.72   351.1 2437.41   360.9 2437.18   381.1 2439.49
   424.7 2437.17   485.5 2438.43   515.9 2444.69   590.5  2448.4   622.1 2451.02
   651.2 2451.01   660.3 2452.74   678.8 2461.24   714.2 2483.45   755.5 2503.42
#Mann= 6 ,-1,0
       0      .1       0   110.6     .06       0   181.8    .035       0
     302    .025       0   351.1     .05       0   590.5      .1       0
Bank Sta=181.8,302
XS Rating Curve= 0 ,0
Exp/Cntr(USF)=0,0
Exp/Cntr=0.3,0.1

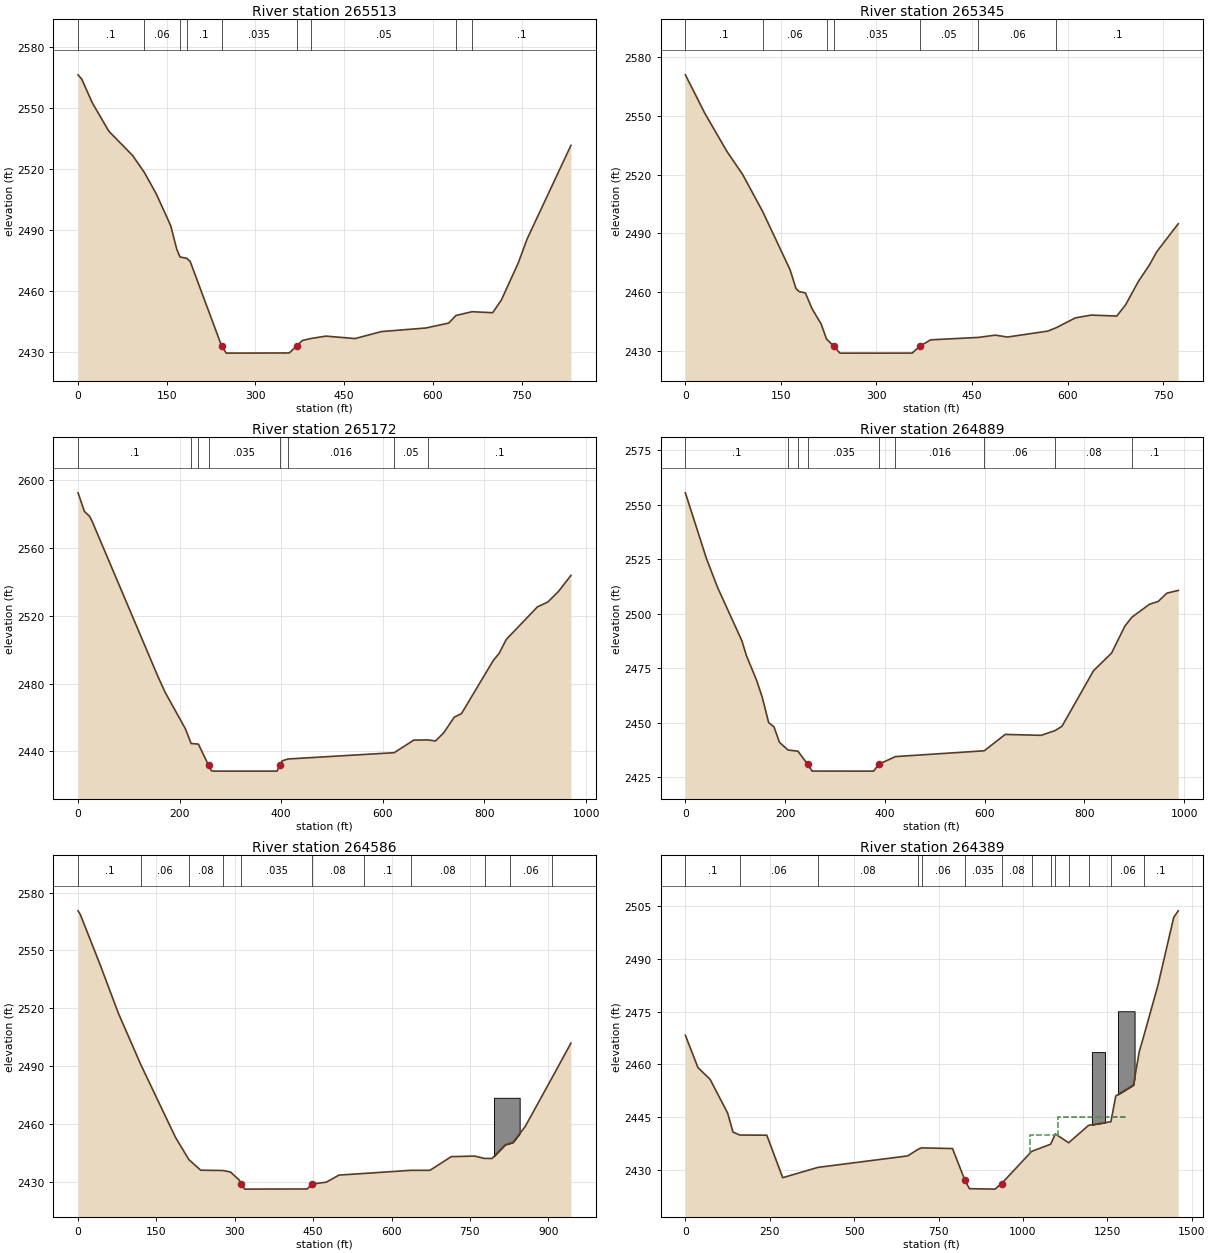
Type RM Length L Ch R = 1 ,265513  ,167.1,167.3,168.2
BEGIN DESCRIPTION:
channel burned 1.14':
lidar invert = 2430.34
effective invert = 2429.20
END DESCRIPTION:
Node Name=W
XS GIS Cut Line= 2
2280746.74635135510994.9053429322280073.13952902511485.595442181
#Sta/Elev= 30
       0 2566.42     6.3 2564.26    24.2 2552.56    52.1 2538.59    92.3 2526.63
   112.1  2518.3   132.3 2507.69   156.6 2492.08   166.9 2480.43   172.4  2476.6
   183.6 2475.97   189.6 2474.41  242.62 2432.83   250.6  2429.2   357.1 2429.28
   369.4 2432.64   379.3 2435.44   394.1 2436.42   418.9 2437.59   468.4 2436.38
   513.1 2439.83   588.1 2441.59   626.7 2444.02   639.1 2447.78   666.3 2449.62
     701 2449.13   715.8  2455.4   744.4  2473.7   759.3 2485.48   833.4 2531.62
#Mann= 9 ,-1,0
       0      .1       0   112.1     .06       0   172.4    .016       0
   183.6      .1       0  242.62    .035       0   369.4     .08       0
   394.1     .05       0   639.1    .016       0   666.3      .1       0
Bank Sta=242.62,369.4
XS Rating Curve= 0 ,0
Exp/Cntr=0.3,0.1

Type RM Length L Ch R = 1 ,265345  ,176.9,173,164.6
BEGIN DESCRIPTION:
channel burned 1.34':
lidar invert = 2430.16
interpolated invert = 2428.82
END DESCRIPTION:
XS GIS Cut Line= 2
2280633.03226125510872.7142381082280005.22487092511324.927990527
#Sta/Elev= 30
       0 2570.99    30.6 2551.31    65.1 2531.93    89.8 2520.13   121.3 2501.18
   164.3 2471.46   173.6 2461.83   178.5 2460.28   188.4 2459.57   198.7 2451.59
     213 2443.77   221.6 2436.03   232.8 2432.41   242.6 2428.82     356 2428.84
   367.7 2432.27   384.9 2435.61     460 2436.85   486.7 2438.02   505.3 2437.03
   568.8 2440.07   582.5 2441.85   612.3 2446.84     637 2448.25   677.2 2447.77
   691.2 2453.59   710.9 2465.32   728.8 2474.04   739.9  2480.6   773.7 2494.92
#Mann= 7 ,-1,0
       0      .1       0   121.3     .06       0   221.6     .08       0
   232.8    .035       0   367.7     .05       0     460     .06       0
   582.5      .1       0
Bank Sta=232.8,367.7
XS Rating Curve= 0 ,0
Exp/Cntr(USF)=0,0
Exp/Cntr=0.7,0.5

Type RM Length L Ch R = 1 ,265172  ,278.7,283.6,293.9
BEGIN DESCRIPTION:
channel burned 1.51':
lidar invert = 2429.94
interpolated invert = 2428.43
END DESCRIPTION:
XS GIS Cut Line= 2
2280545.96359794510701.9713194952279788.63565133511308.551523177
#Sta/Elev= 30
       0  2592.4    12.5 2581.45    22.8 2578.54    27.9  2575.5   157.2 2484.22
   171.5 2474.84   211.3 2453.38   222.6 2444.71   236.9 2444.34   256.8 2431.98
   262.5 2428.66   268.2 2428.43   391.8 2428.44   396.9 2431.78     402 2434.48
   413.3 2435.59   622.4 2439.29   660.9  2446.7     689 2446.81   703.6 2446.19
   719.8 2450.99   740.6 2460.23   754.8 2462.31   817.7 2493.74   828.8 2497.74
     843 2506.01   904.3  2525.2   924.8 2528.08   945.5 2534.19   970.3 2543.74
#Mann= 8 ,-1,0
       0      .1       0   222.6    .016       0   236.9      .1       0
   256.8    .035       0   396.9     .05       0   413.3    .016       0
   622.4     .05       0     689      .1       0
Bank Sta=256.8,396.9
XS Rating Curve= 0 ,0
Exp/Cntr(USF)=0,0
Exp/Cntr=0.3,0.1

Type RM Length L Ch R = 1 ,264889  ,331.6,302.4,271.8
BEGIN DESCRIPTION:
channel burned 1.79':
lidar invert = 2429.59
effective invert = 2427.80
END DESCRIPTION:
XS GIS Cut Line= 3
2280376.79984316510499.0798719552279722.24897383510959.067224495
 2279643.2494382511129.774570226
#Sta/Elev= 30
       0 2555.55    42.2 2525.41    64.3 2512.25   113.2 2487.67   122.5 2480.76
   142.8 2469.48   154.1  2461.7     167 2450.06   177.6 2448.15   188.6 2441.02
   205.8 2437.49   225.7 2436.95   245.2 2430.93   254.1 2427.82   377.2  2427.8
   388.7 2431.06   421.1 2434.47   599.2 2437.14   641.2 2444.65   713.2 2444.23
   741.1  2446.4     755 2448.39   818.2 2473.88   854.4 2481.99   881.1 2494.37
   894.9 2498.41   930.2 2504.36   947.8 2505.69   965.4 2509.51   988.1 2510.75
#Mann= 9 ,-1,0
       0      .1       0   205.8    .016       0   225.7      .1       0
   245.2    .035       0   388.7     .05       0   421.1    .016       0
   599.2     .06       0   741.1     .08       0   894.9      .1       0
Bank Sta=245.2,388.7
XS Rating Curve= 0 ,0
Exp/Cntr=0.3,0.1

Type RM Length L Ch R = 1 ,264586  ,253.4,196.8,179.9
BEGIN DESCRIPTION:
structure xs 4 - channel burned 1.91':
lidar invert = 2428.32
interpolated invert = 2426.41
END DESCRIPTION:
XS GIS Cut Line= 4
2280235.80065629510185.2345462982280060.44755762510308.631171293
2279854.78651596510529.446184442   2279547.37738510826.031055044
#Sta/Elev= 30
       0 2570.54     4.4 2568.59    42.8 2542.24    77.2 2517.48   120.3 2490.77
   186.3 2453.31   212.1  2441.7   234.8 2436.21   277.3 2436.05   291.7 2435.28
   308.1 2431.22  312.48 2429.04     319 2426.41   438.6  2426.5  447.78 2429.02
   475.4 2430.04   499.4 2433.69   547.6 2434.53   636.5 2436.15   673.4 2436.14
   714.3 2443.23   758.8 2443.53   778.1  2442.3   792.2 2442.29   817.7 2449.41
   826.2 2450.04   832.6 2450.66   855.7  2458.8   907.5 2484.25   943.3 2502.02
#Mann= 11 ,-1,0
       0      .1       0   120.3     .06       0   212.1     .08       0
   277.3     .07       0  312.48    .035       0  447.78     .08       0
   547.6      .1       0   636.5     .08       0   778.1     .07       0
   826.2     .06       0   907.5      .1       0
#Block Obstruct= 1 ,-1
  796.03  845.18 2473.72
Bank Sta=312.48,447.78
XS Rating Curve= 0 ,0
Exp/Cntr(USF)=0,0
Exp/Cntr=0.5,0.3

Type RM Length L Ch R = 1 ,264389  ,142.4,93,90.9
BEGIN DESCRIPTION:
structure xs 3
channel burned per surveyed cross section points
END DESCRIPTION:
XS GIS Cut Line= 6
2279683.51081002509503.9175108352279689.23320511 509687.03415369
2279768.03512668509865.0191509642279883.70540758510019.246192167
 2279898.1641927510096.3597127682279492.42493398510795.754165263
#Sta/Elev= 30
       0 2468.25    37.3 2459.04    73.3  2455.7   125.3 2446.07   141.1 2440.69
   161.3 2439.84   241.2  2439.8   288.4  2427.7   392.7 2430.63   658.6  2433.9
   690.5 2435.83   700.3 2436.19   791.5 2435.99  827.76 2427.09  841.53 2424.57
  917.44 2424.44   936.9 2426.02    1026 2435.19  1082.2 2437.23  1096.3 2440.16
  1135.7 2437.64  1194.8  2442.6  1260.8 2443.63  1275.4 2450.99  1327.7 2454.08
  1344.8 2463.55  1358.9 2468.25  1400.5 2482.59    1447 2501.84  1460.4 2503.69
#Mann= 14 ,-1,0
       0      .1       0   161.3     .06       0   392.7     .08       0
   690.5    .016       0   700.3     .06       0  827.76    .035       0
   936.9     .08       0    1026    .016       0  1082.2     .06       0
  1096.3    .016       0  1135.7     .06       0  1194.8    .016       0
  1260.8     .06       0  1358.9      .1       0
#XS Ineff= 3 ,-1
       0     792  2431.5    1022 1103.32  2439.9 1103.32 1311.55    2445
Permanent Ineff=
       F       F       F
#Block Obstruct= 2 ,-1
  1204.6 1243.17 2463.46  1281.7 1330.98 2475.09
Bank Sta=827.76,936.9
XS Rating Curve= 0 ,0
Exp/Cntr=0.5,0.3