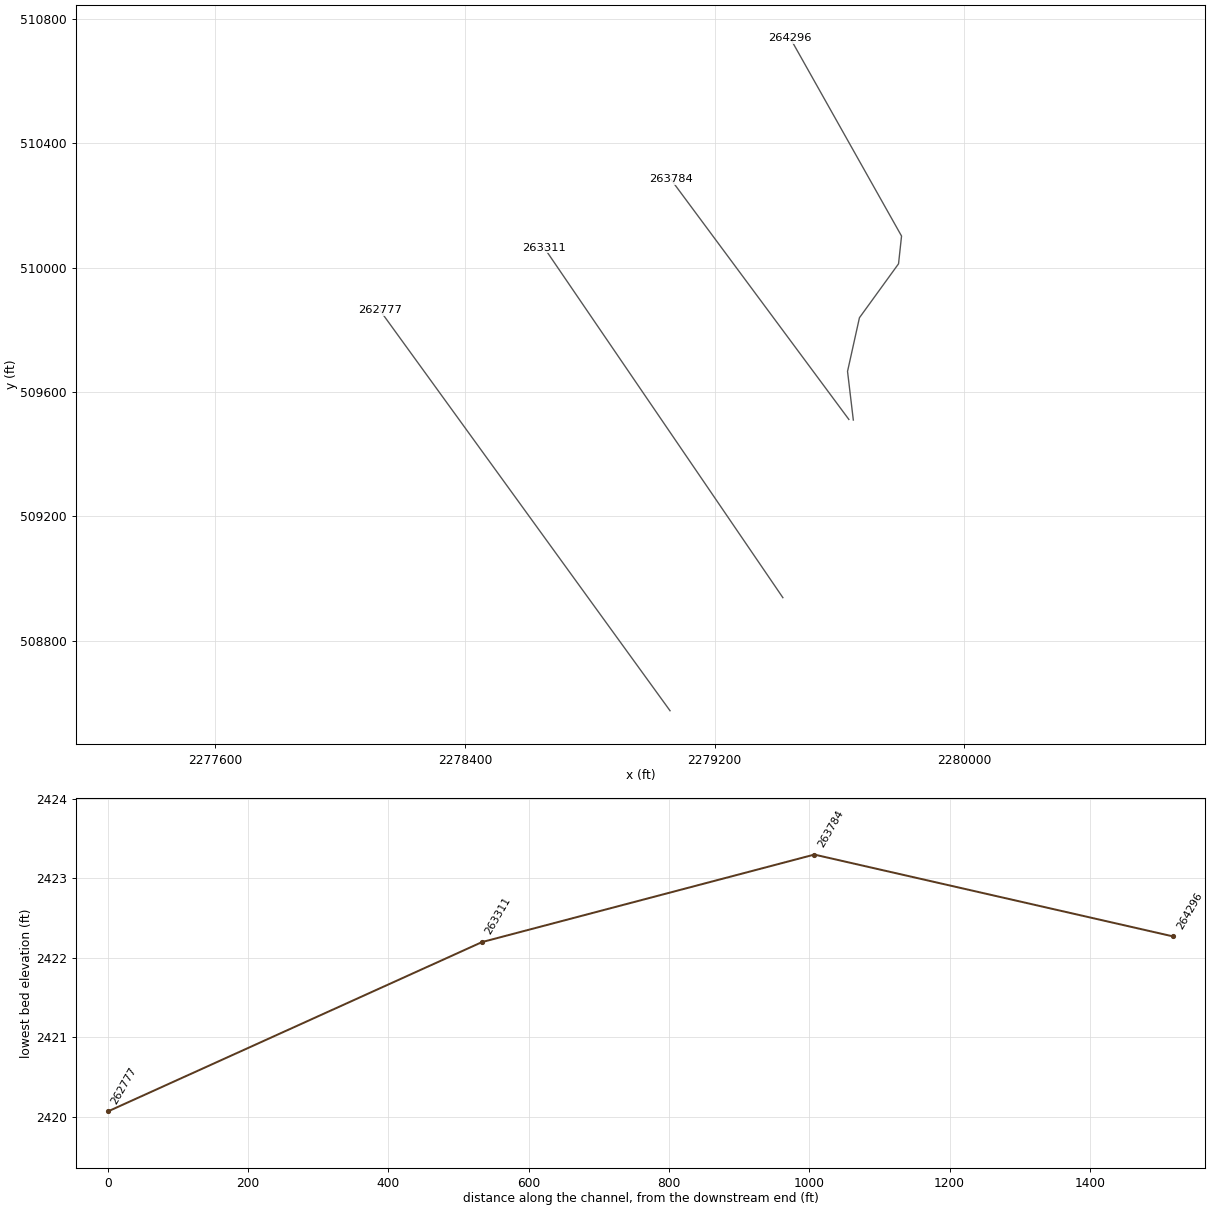
HEC-RAS study GRNBRRRV.prj: GRNBRRRV

--- GRNBRRRV.g01 (geometry) --- (continued)

Type RM Length L Ch R = 3 ,264345  ,,,
BEGIN DESCRIPTION:
Bridge No.: 54075GRM010 Cass Rd (Route 66)
JV notes: road deck updated per surveyed XS data points
channel burned per surveyed cross sections
structure opening based on survey data, photos, and aerial imagery
surveyed inverts are 2-3' below inverts from lidar:
 surveyed invert US is 2424.75
 surveyed invert DS is 2422.27
END DESCRIPTION:
Bridge Culvert--1,0,-1,-1, 0
Deck Dist Width WeirC Skew NumUp NumDn MinLoCord MaxHiCord MaxSubmerge Is_Ogee
27,40,2.6,0, 411, 411, , , 0.98, 0, 0,0,,
      34    36.4    40.4    44.4    45.1    47.6    48.4    49.3    51.5    52.4
    56.4    57.6    59.2    60.4    61.8      63    64.4    68.4    72.4    74.3
    78.4    80.4    82.2    82.7    84.4    88.4    89.9    92.4    96.4    97.6
   100.5   104.5   107.8   109.1   111.9   112.5   116.5   120.5   120.6   124.5
   132.8     136   139.9   140.5   141.2   143.7   145.4   147.5   148.5   149.5
   151.4   152.5   153.7   155.2   156.5   157.9   159.1   162.1   162.9   164.5
   166.2   166.8   168.5   172.5   176.5   180.5   188.5   196.5   208.6   210.9
   213.3   216.9   221.1   222.9   226.1   229.4   233.6   237.8     242   247.7
   248.5   251.8   254.5   259.7   261.4   267.1   267.8   271.7   277.7   279.6
   283.8   297.7   304.7   309.5   317.2   319.1   321.4   325.3   328.6   331.7
   332.6   334.1   336.7   341.1   344.2   346.2   348.1   350.4   351.2   359.9
   362.8   365.9     369     371   372.6   376.8   381.5   384.2   385.9   390.4
     395     396     399   402.5   404.3   405.4   407.6   410.5   413.9   416.3
   418.7     420   422.1   427.4   433.7   436.5   437.7   442.5   445.2   448.1
     451   453.9   457.1   459.7   461.6     464   465.5   468.3   474.1   475.9
     477   480.1   480.7   482.8   485.9   488.4   491.3   491.6     497   501.4
   504.2   506.6   511.7     514   516.9   519.7     522   525.4   527.2   532.4
   535.9   542.2   545.3   547.8   548.5     551     553   558.2   562.4   567.5
   570.9   573.8   579.4   582.3   585.5   588.6   591.1   596.1   597.1   599.3
   601.8   605.9   606.8   609.8   614.1   615.2   623.4   626.4   626.7   630.6
   634.7   636.8   643.4   646.8   650.9   654.9   658.9   660.8   663.4   665.9
   666.9   671.1   673.8   677.3   680.8   681.9   687.7   692.9   697.5   699.9
   700.6   703.6   704.3   706.7   709.7   713.2   717.2     722   725.1   727.9
   728.3   732.2     735   743.5  787.82  814.65  818.74  818.74  867.58  892.28
  906.26  907.38   944.4  995.66  995.66  997.57 1018.33 1062.78  1070.1    1073
  1073.5    1076  1078.9  1081.8  1086.4  1087.4    1092  1099.4  1102.3  1105.2
  1108.1    1111  1111.8  1115.2  1119.7  1119.9  1122.7  1124.5  1125.7  1127.6
  1129.1  1131.5  1133.8  1135.5  1138.4  1140.3  1143.4  1147.7    1149  1151.4
    1152  1153.7  1154.9  1159.3  1160.7  1163.7  1166.2  1167.2  1170.9  1172.4
  1175.3  1178.3  1180.1  1181.2  1184.1    1187  1187.3  1190.9  1192.9  1194.1
  1198.5  1204.6    1208  1210.4  1212.6  1216.3  1219.2  1221.9    1225  1226.5
  1230.4  1232.2  1235.8  1236.7  1238.3  1239.7  1240.4  1243.4  1245.1  1245.5
  1246.3  1248.4  1251.3  1254.2  1257.2    1259    1263  1263.6  1268.2  1268.9
    1270  1272.9  1277.7  1282.2  1285.8  1289.3  1296.1  1299.4  1300.7    1304
  1305.3  1309.8  1314.6  1315.7  1319.3  1321.8  1323.9  1327.3  1328.5    1333
  1336.1  1337.8  1341.2    1342  1342.4  1344.3  1344.9  1347.1  1347.8  1350.7
  1351.7  1356.3    1357  1359.5    1361  1362.4  1364.9  1365.3  1366.7  1370.3
  1371.2  1374.9  1377.9  1379.5    1380  1382.9  1384.2  1388.6  1391.7  1393.4
  1394.6  1396.5  1398.1  1400.4  1402.7  1403.3  1404.4  1409.2  1411.5    1412
  1412.3    1415  1416.6    1418  1420.2  1421.3  1423.8  1425.9  1426.7  1428.1
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                                                 2435.67 2435.67 2436.02 2436.19
 2436.29  2436.3 2436.56 2436.92 2436.92
     -17   -14.6   -10.6    -6.6    -5.9    -3.4    -2.6    -1.7      .5     1.4
     5.4     6.6     8.2     9.4    10.8      12    13.4    17.4    21.4    23.3
    27.4    29.4    31.2    31.7    33.4    37.4    38.9    41.4    45.4    46.6
    49.5    53.5    56.8    58.1    60.9    61.5    65.5    69.5    69.6    73.5
    81.8      85    88.9    89.5    90.2    92.7    94.4    96.5    97.5    98.5
   100.4   101.5   102.7   104.2   105.5   106.9   108.1   111.1   111.9   113.5
   115.2   115.8   117.5   121.5   125.5   129.5   137.5   145.5   157.6   159.9
   162.3   165.9   170.1   171.9   175.1   178.4   182.6   186.8     191   196.7
   197.5   200.8   203.5   208.7   210.4   216.1   216.8   220.7   226.7   228.6
   232.8   246.7   253.7   258.5   266.2   268.1   270.4   274.3   277.6   280.7
   281.6   283.1   285.7   290.1   293.2   295.2   297.1   299.4   300.2   308.9
   311.8   314.9     318     320   321.6   325.8   330.5   333.2   334.9   339.4
     344     345     348   351.5   353.3   354.4   356.6   359.5   362.9   365.3
   367.7     369   371.1   376.4   382.7   385.5   386.7   391.5   394.2   397.1
     400   402.9   406.1   408.7   410.6     413   414.5   417.3   423.1   424.9
     426   429.1   429.7   431.8   434.9   437.4   440.3   440.6     446   450.4
   453.2   455.6   460.7     463   465.9   468.7     471   474.4   476.2   481.4
   484.9   491.2   494.3   496.8   497.5     500     502   507.2   511.4   516.5
   519.9   522.8   528.4   531.3   534.5   537.6   540.1   545.1   546.1   548.3
   550.8   554.9   555.8   558.8   563.1   564.2   572.4   575.4   575.7   579.6
   583.7   585.8   592.4   595.8   599.9   603.9   607.9   609.8   612.4   614.9
   615.9   620.1   622.8   626.3   629.8   630.9   636.7   641.9   646.5   648.9
   649.6   652.6   653.3   655.7   658.7   662.2   666.2     671   674.1   676.9
   677.3   681.2     684   692.5  736.82  763.65  767.74  767.74  816.58  841.28
  855.26  856.38   893.4  944.66  944.66  946.57  967.33 1011.78  1019.1    1022
  1022.5    1025  1027.9  1030.8  1035.4  1036.4    1041  1048.4  1051.3  1054.2
  1057.1    1060  1060.8  1064.2  1068.7  1068.9  1071.7  1073.5  1074.7  1076.6
  1078.1  1080.5  1082.8  1084.5  1087.4  1089.3  1092.4  1096.7    1098  1100.4
    1101  1102.7  1103.9  1108.3  1109.7  1112.7  1115.2  1116.2  1119.9  1121.4
  1124.3  1127.3  1129.1  1130.2  1133.1    1136  1136.3  1139.9  1141.9  1143.1
  1147.5  1153.6    1157  1159.4  1161.6  1165.3  1168.2  1170.9    1174  1175.5
  1179.4  1181.2  1184.8  1185.7  1187.3  1188.7  1189.4  1192.4  1194.1  1194.5
  1195.3  1197.4  1200.3  1203.2  1206.2    1208    1212  1212.6  1217.2  1217.9
    1219  1221.9  1226.7  1231.2  1234.8  1238.3  1245.1  1248.4  1249.7    1253
  1254.3  1258.8  1263.6  1264.7  1268.3  1270.8  1272.9  1276.3  1277.5    1282
  1285.1  1286.8  1290.2    1291  1291.4  1293.3  1293.9  1296.1  1296.8  1299.7
  1300.7  1305.3    1306  1308.5    1310  1311.4  1313.9  1314.3  1315.7  1319.3
  1320.2  1323.9  1326.9  1328.5    1329  1331.9  1333.2  1337.6  1340.7  1342.4
  1343.6  1345.5  1347.1  1349.4  1351.7  1352.3  1353.4  1358.2  1360.5    1361
  1361.3    1364  1365.6    1367  1369.2  1370.3  1372.8  1374.9  1375.7  1377.1
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                                                 2435.67 2435.67 2436.02 2436.19
 2436.29  2436.3 2436.56 2436.92 2436.92
Pier Skew, UpSta & Num, DnSta & Num=  ,897.38, 2 ,848.56, 2 , 0 , 0 , 0 ,,
       3       3
       0    2437
       3       3
       0    2437
BR Coef=-1 ,-1 , 0 ,, 0 ,,,0.8,0,1.33,0,
WSPro=,,,, 1 ,,,, 0 ,,,, 0 ,,,,-1 ,-1 ,-1 , 0 , 0 , 0 , 0 , 0
BR U #Sta/Elev= 414
       0 2468.25     1.9 2467.75     4.7 2466.62     8.9 2465.54    17.3 2463.91
    21.3 2463.03    25.4 2462.06    32.9 2459.85    37.3 2459.04    41.9 2458.48
    45.3  2458.2    53.3 2457.74    61.3 2456.81    69.3 2456.28    73.3  2455.7
    77.3  2455.1    89.3 2452.84    93.3 2451.94   109.3 2448.65   113.3 2447.95
   117.3 2447.09   125.3 2446.07   129.3 2445.16   132.8 2443.77   136.9 2442.03
   141.1 2440.69   145.2 2440.06   149.3 2439.84   161.3 2439.84   173.3 2440.26
   178.3 2440.18     184 2439.86   187.1 2439.85   191.4 2439.98   196.4 2439.85
   202.7 2439.91   208.8 2439.82   215.5 2439.97   219.8 2439.92   224.7 2440.11
   232.7 2440.22   233.5 2440.14     237 2440.02   239.7 2439.82   241.2  2439.8
   242.8 2439.55   244.7 2439.36   245.5 2439.25     249  2438.5   254.1 2437.51
   258.3 2436.46   262.7 2434.62     267 2432.94   267.6 2432.74   271.3  2431.2
   273.8  2430.5   275.5 2429.93   276.9 2429.67   279.9 2428.84     283  2428.4
   284.1 2428.07   288.4  2427.7   292.3 2427.72     297 2427.61   301.3 2427.69
   307.5 2428.03   310.5 2428.03   316.4 2428.44   319.3 2428.52   322.3 2428.88
   323.9 2428.98   328.5 2428.97   331.2 2429.09   337.1 2429.25   346.6 2429.46
   351.2 2429.64   351.8 2429.67   355.7 2429.96   360.2 2430.14   373.9 2430.27
   383.4 2430.55   392.7 2430.63   412.7 2430.98   429.9 2431.11   431.8 2431.17
   433.4  2431.2   445.1 2431.34   458.3 2431.62   458.4 2431.62   461.3 2431.59
   463.4 2431.56   465.1 2431.54   478.3 2431.69   493.4 2431.66   505.1 2431.77
   512.7 2431.75   524.1    2432   538.4 2432.09   555.6 2432.57   572.8 2433.24
   587.9 2433.43   601.4 2433.51   612.9 2433.77   621.8 2433.84   638.1 2434.15
   646.2 2434.12     648 2434.08   651.7 2433.96   653.6 2433.92   654.5  2433.9
     655 2433.89   658.6  2433.9   659.4 2433.93   662.8 2434.04   665.2 2434.21
   666.9 2434.33     671 2434.71   690.5 2435.83   700.3 2436.19   708.5 2436.24
     710 2436.16   712.7 2436.02   713.2 2436.02   716.4 2436.02   716.9 2436.01
   719.7 2436.01   735.3 2436.46   737.1 2436.55   739.6 2436.73     740 2436.75
   740.2 2436.76   744.6 2436.91   747.8 2436.98   748.8 2436.98   749.3 2436.98
   751.7 2436.84   751.7 2436.83     754 2436.64   754.6 2436.58   755.5 2436.49
   758.7 2436.32   760.4 2436.14   763.2 2436.05   763.3 2436.04   768.1 2435.81
   769.1 2435.84   770.8  2435.9     772 2435.88   772.8 2435.87   774.9 2435.95
   777.9  2436.1   780.8 2436.24   782.2 2436.27   786.6 2436.17   786.8 2436.16
   787.9 2436.12   789.5 2436.06   791.5 2435.99   796.2 2435.49   801.1 2434.51
   805.6 2432.88   806.9 2432.44   810.3 2431.43   815.7 2430.11  818.67  2429.4
  827.76 2427.09  834.39 2425.36  841.53 2424.57  865.48 2424.76  892.17 2424.75
  907.27 2424.95  917.44 2424.44  924.35 2424.96   936.9 2426.02  953.65 2427.38
  982.13 2429.79   996.1 2432.57   997.8 2432.77     999 2432.91  1000.8 2433.13
  1002.5 2433.33  1004.8 2433.53  1005.2 2433.58  1007.2  2433.8  1007.7 2433.84
  1013.5 2434.14  1016.2 2434.25  1016.4 2434.27  1016.6 2434.28  1017.3 2434.36
  1019.3 2434.59  1021.3 2434.79  1022.2 2434.92  1023.8 2435.05    1026 2435.19
  1028.1 2435.31  1030.7 2435.39    1031  2435.4  1051.3 2435.76  1053.5 2435.82
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BR U #Mann= 14
       0      .1   161.3     .06   392.7     .08   690.5    .016   700.3     .06
  827.76     .03   936.9     .08    1026    .016  1082.2     .06  1096.3    .016
  1135.7     .06  1194.8    .016  1260.8     .06  1358.9      .1
BR D #Sta/Elev= 416
       0 2452.09     3.8 2451.54     7.9 2450.61      11 2449.74    11.7  2449.6
    14.6 2449.19    19.7 2448.64    23.8 2448.01    27.8 2447.23    36.2 2446.31
    44.5 2445.28    51.9 2444.27      56 2443.29      60 2442.03      65  2440.6
    67.3 2440.17    68.6 2439.88    73.5 2439.85      83 2439.94    88.2 2439.92
    92.2 2439.85    96.3 2439.73   104.7  2439.3   108.3 2439.03   111.9  2438.7
   115.5 2438.22   119.1 2437.59   129.9 2435.32   132.5 2434.88   137.1 2434.31
   141.5 2433.99   152.6 2433.55   157.6 2433.48   165.1 2433.61   177.1 2433.46
   181.2 2433.36   185.5 2433.38   189.4 2433.34   193.5 2433.03   195.3 2432.81
     196 2432.77   198.7 2432.47   201.7 2432.05   203.4 2431.93   205.8 2431.69
   208.7 2430.97   212.1 2430.25     214 2429.81   215.4 2429.87   222.1  2429.9
   226.3 2429.97   230.4 2430.24   235.6 2430.44   240.4  2430.7   243.3 2430.79
   245.6 2430.78   250.9 2430.97     255 2430.92   263.2 2430.18   269.1 2429.93
   272.5 2429.83   274.9 2429.87   275.5 2429.86   279.2 2429.56   279.6 2429.55
   282.5 2429.46   283.7 2429.44   285.4 2429.42   287.8 2429.41   289.2 2429.33
   290.7 2429.27   291.8 2429.21     296 2428.81     300 2428.46     306 2428.41
   308.2 2428.46   311.7 2427.84   312.3 2427.73   314.5 2427.56   316.1 2427.43
   324.6 2426.32   326.2 2426.19   328.7 2425.99   332.7 2426.09   332.8  2426.1
   332.9 2426.11   333.1 2426.16   334.2 2426.43     336 2426.76   337.2 2426.87
   338.9 2427.28   341.8  2427.8   346.4 2428.51   350.2 2428.89     351 2428.99
   353.6 2429.36   358.4 2429.72   360.1 2429.83   362.3 2429.86   362.4 2429.87
   365.4 2429.91   366.6 2430.01   369.3 2430.18   371.3 2430.36   373.8 2430.69
   374.2 2430.71   377.1 2430.98   378.4 2431.18   380.1 2431.31   382.8 2431.55
     383 2431.56   394.8  2431.8   410.4 2431.96   432.5 2431.78   438.7 2431.81
     444 2431.75   454.7 2431.75   455.7 2431.76   456.8 2431.79   458.6 2431.83
   472.7 2431.88   474.9 2431.92   475.6 2431.92   476.1 2431.93   501.1 2431.96
   518.1 2432.15   540.7  2432.2   554.9 2432.36     575 2432.81   575.7 2432.83
   577.1 2432.88   578.2 2432.92   579.9 2432.98   581.4 2433.04     583 2433.09
   584.6 2433.15   586.5 2433.26   587.8 2433.34   588.2 2433.36   588.9 2433.38
   591.1 2433.45   592.2 2433.49   596.4 2433.74   597.7 2433.81   599.1 2433.89
   600.4 2433.97   601.5 2434.04   604.4 2434.22   605.3 2434.28   607.6 2434.46
   608.4 2434.52   612.4 2434.87     616 2434.95   616.4 2434.96   616.8 2434.96
   620.2 2434.95   624.4 2434.94   628.2 2434.78   628.4 2434.77   632.4 2434.65
   632.9 2434.64   637.1  2434.6   663.4 2435.34     668 2435.51   686.3 2436.34
   686.9 2436.37   687.9 2436.42   689.8 2436.51   690.9 2436.57   692.7 2436.66
   694.8 2436.77   695.5 2436.81   695.7 2436.82     696 2436.84   698.6 2436.97
   700.1 2437.05   701.6  2437.1   704.5 2437.18   712.4 2437.36   713.3 2437.38
   713.8 2437.38   715.6 2437.38   718.4 2437.43   719.2 2437.45   722.1 2437.55
     723  2437.6   725.1 2437.69   726.1 2437.73   727.6 2437.79     728  2437.8
   728.8 2437.81   732.2 2437.92   733.9 2437.96   736.5 2437.99   736.7    2438
   741.3 2437.96   742.7 2437.91   745.1 2437.82   745.9 2437.79   746.9 2437.66
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BR D #Mann= 11
       0      .1      83    .016    96.3      .1   410.4    .016   715.6     .06
  786.44     .03  909.71     .07  935.56     .08   979.8    .016  1181.6     .06
  1317.7      .1
BR D Banks=786.44,
BC Design=,, 0 ,, 0 ,,,,,,
BC Use User HTab Curves=0
BC User HTab FreeFlow(D)= 0

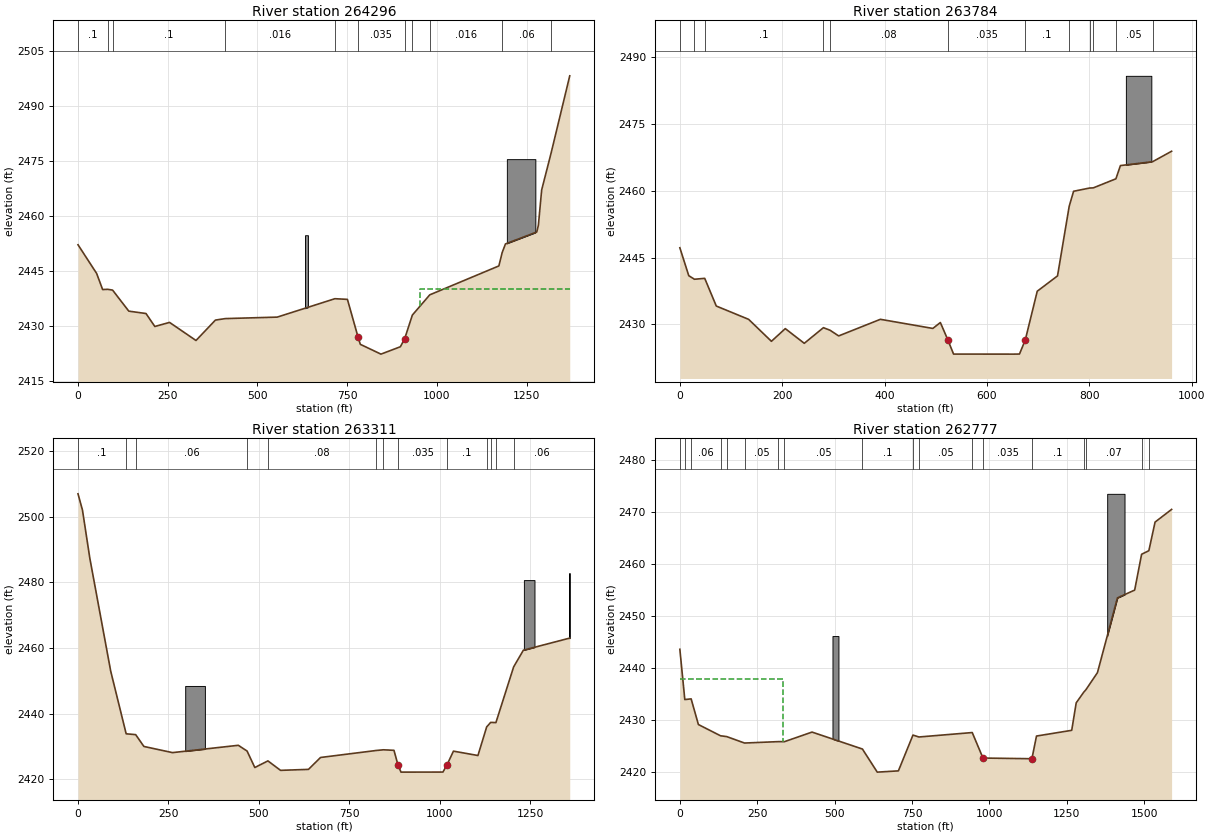
Type RM Length L Ch R = 1 ,264296  ,446.4,512,522.2
BEGIN DESCRIPTION:
structure xs 2
channel burned per surveyed cross section points
END DESCRIPTION:
XS GIS Cut Line= 6
2279644.82985845509509.5914973012279626.28685913509666.052038363
2279664.41383337509838.5113782582279789.72330435510012.016799611
2279799.36249443510101.1793078062279442.71246165510737.365852767
#Sta/Elev= 30
       0 2452.09    51.9 2444.27    68.6 2439.88      83 2439.94    96.3 2439.73
   141.5 2433.99   189.4 2433.34     214 2429.81     255 2430.92   328.7 2425.99
   382.8 2431.55   410.4 2431.96   554.9 2432.36   715.6 2437.38   750.5  2437.2
  780.39 2426.82  786.44 2424.94  843.85 2422.27  897.98 2424.28  909.71 2426.39
  931.33 2432.91   979.8 2438.43  1172.4 2446.32  1181.6 2449.97  1190.7 2452.31
  1277.9 2455.57  1282.4 2457.38  1291.6 2467.04  1317.7 2477.03  1369.8 2498.15
#Mann= 11 ,-1,0
       0      .1       0      83    .016       0    96.3      .1       0
   410.4    .016       0   715.6     .06       0  780.39    .035       0
  909.71     .07       0  931.33     .08       0   979.8    .016       0
  1181.6     .06       0  1317.7      .1       0
#XS Ineff= 2 , 0
             759  2431.5   953.3          2439.9
Permanent Ineff=
       F       F
#Block Obstruct= 2 ,-1
  632.38  640.45 2454.69  1194.6 1273.98 2475.43
Bank Sta=780.39,909.71
XS Rating Curve= 0 ,0
Exp/Cntr(USF)=0,0
Exp/Cntr=0.5,0.3

Type RM Length L Ch R = 1 ,263784  ,503.9,473.7,470.2
BEGIN DESCRIPTION:
xs 1 - channel burned 0.66':
lidar invert = 2423.96
effective invert = 2423.30
END DESCRIPTION:
XS GIS Cut Line= 2
2279630.50653587509511.5940303752279059.55465616510284.323919234
#Sta/Elev= 30
       0 2447.19    17.4 2440.92    28.5 2440.12    48.6 2440.32    71.2  2434.1
   134.4 2431.11   178.9 2426.18     206 2429.03   243.1 2425.73   280.5 2429.24
   293.4 2428.67   310.3 2427.39   391.8 2431.12   494.3 2429.07     509  2430.4
   523.3 2426.58   534.8 2423.31   652.1  2423.3   663.6 2423.32   674.9 2426.47
   698.3 2437.43   737.9 2440.87   760.7 2456.49   769.3 2459.88   800.8 2460.61
   807.7 2460.64     852 2462.68   860.8 2465.65   923.8 2466.53   960.8 2468.87
#Mann= 12 ,-1,0
       0      .1       0    28.5    .016       0    48.6      .1       0
   280.5    .016       0   293.4     .08       0   523.3    .035       0
   674.9      .1       0   760.7     .05       0   800.8     .06       0
   807.7    .016       0     852     .05       0   923.8     .07       0
#Block Obstruct= 1 ,-1
  871.45  921.21 2485.81
Bank Sta=523.3,674.9
XS Rating Curve= 0 ,0
Exp/Cntr(USF)=0,0
Exp/Cntr=0.3,0.1

Type RM Length L Ch R = 1 ,263311  ,531.8,533.5,536.6
BEGIN DESCRIPTION:
channel burned 0.21':
lidar invert = 2422.41
effective invert = 2422.20
END DESCRIPTION:
XS GIS Cut Line= 2
2279419.08231368508938.5395002262278654.56597917510063.139520601
#Sta/Elev= 30
       0 2506.96    12.3 2502.04    32.8 2487.28    90.5 2452.93   133.2 2433.87
   159.5 2433.62   182.2 2430.02   261.3 2428.14   443.3 2430.37   467.6 2428.62
     489  2423.6   525.2 2425.62   560.1 2422.74   637.4 2423.04   670.7 2426.66
   825.4  2428.8   844.7    2429   873.8 2428.84  884.73 2424.46   893.2  2422.2
  1009.2 2422.22  1020.4 2424.41  1038.3 2428.59    1106 2427.26  1130.2 2435.98
  1141.3 2437.35  1155.7 2437.28  1204.7 2454.24  1231.7 2459.34  1359.9 2463.02
#Mann= 13 ,-1,0
       0      .1       0   133.2    .016       0   159.5     .06       0
   467.6      .1       0   525.2     .08       0   825.4    .016       0
   844.7      .1       0  884.73    .035       0  1020.4      .1       0
  1130.2     .07       0  1141.3    .016       0  1155.7     .08       0
  1204.7     .06       0
#Block Obstruct= 3 ,-1
  296.46   350.9 2448.45 1233.04 1262.41 2480.68  1358.3 1359.86 2482.81
Bank Sta=884.73,1020.4
XS Rating Curve= 0 ,0
Exp/Cntr=0.3,0.1

Type RM Length L Ch R = 1 ,262777  ,340.9,575.1,616.7
BEGIN DESCRIPTION:
channel burned 0.14':
lidar invert = 2420.84
effective invert = 2420.70
END DESCRIPTION:
Node Name=V
XS GIS Cut Line= 2
2279057.52665662508574.9175870692278127.44649579509863.058041203
#Sta/Elev= 30
       0 2443.63      16 2433.99    36.5 2434.12    59.9  2429.2   131.5 2427.04
   151.6 2426.88   208.9 2425.65   318.5 2425.92   337.8 2425.91   427.1 2427.75
   589.9  2424.5   637.8 2420.07   706.1 2420.31   753.2 2427.18   772.4 2426.81
   944.7 2427.66   979.4 2422.77  1137.5 2422.64  1152.3 2426.99  1266.1 2428.09
  1280.6 2433.36  1305.3 2435.43  1311.9 2435.87  1349.2 2439.15  1413.8 2453.49
  1469.5 2454.99  1491.9 2461.86  1515.3 2462.54  1535.4 2468.03  1588.8 2470.46
#Mann= 18 ,-1,0
       0      .1       0      16    .016       0    36.5     .06       0
   131.5     .07       0   151.6    .016       0   208.9     .05       0
   318.5    .016       0   337.8     .05       0   589.9      .1       0
   753.2     .07       0   772.4     .05       0   944.7     .08       0
   979.4    .035       0  1137.5      .1       0  1305.3    .016       0
  1311.9     .07       0  1491.9    .016       0  1515.3     .07       0
#XS Ineff= 2 , 0
           332.7 2437.98
Permanent Ineff=
       F       F
#Block Obstruct= 2 ,-1
  493.13  512.41 2446.17  1380.7 1436.72 2473.45
Bank Sta=979.4,1137.5
XS Rating Curve= 0 ,0
Exp/Cntr=0.3,0.1