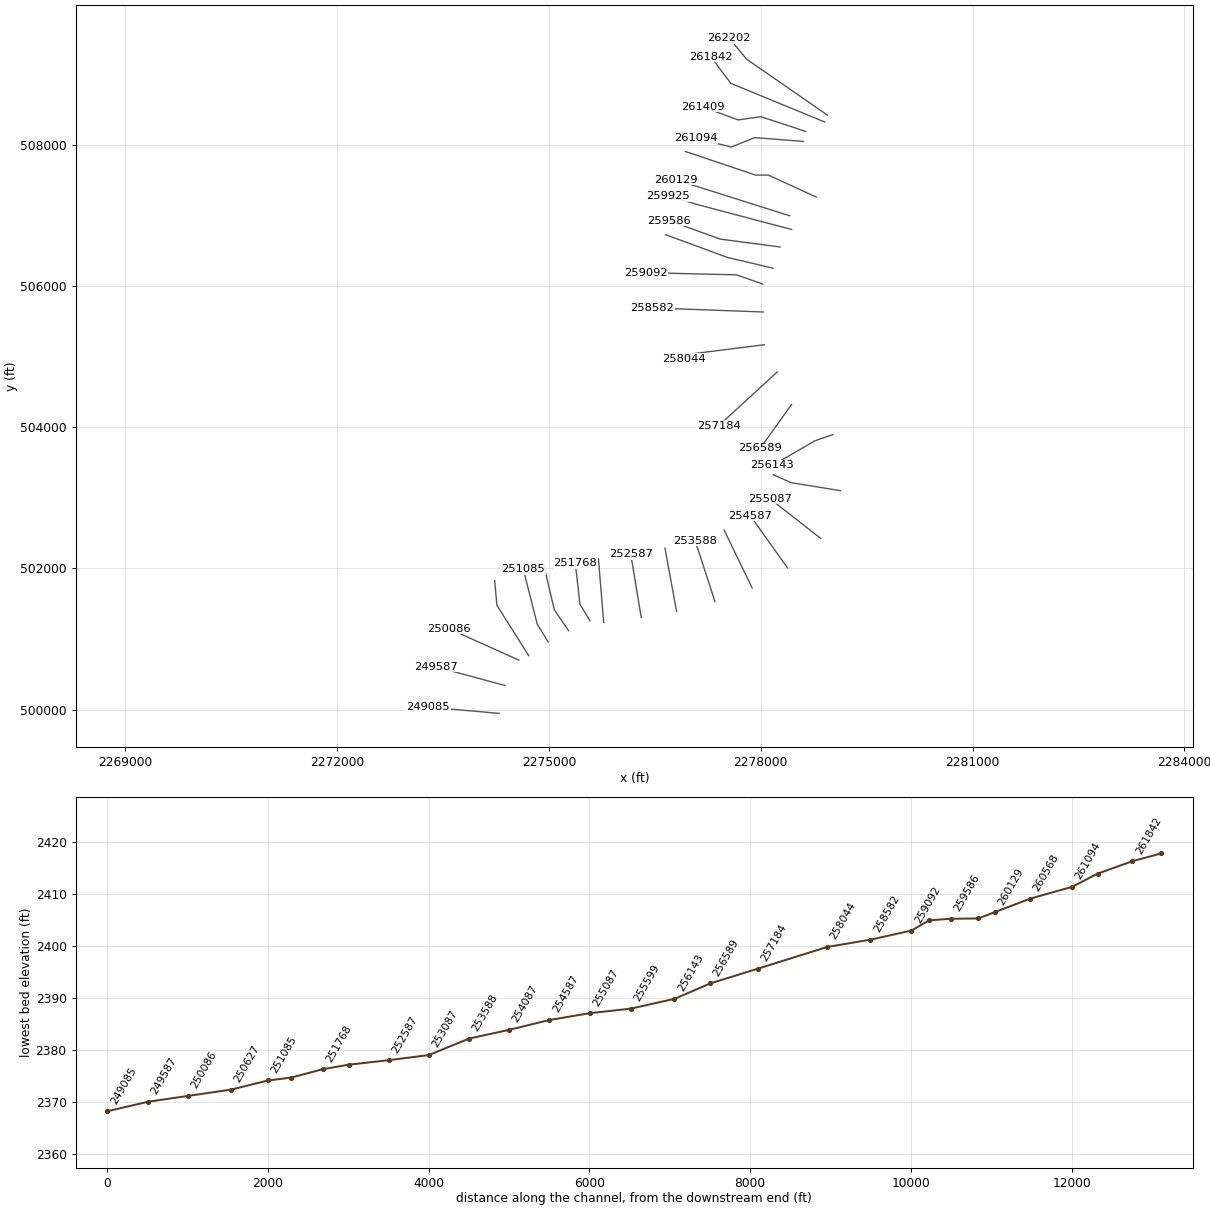
HEC-RAS study GRNBRRRV.prj: GRNBRRRV

--- GRNBRRRV.g01 (geometry) --- (continued)

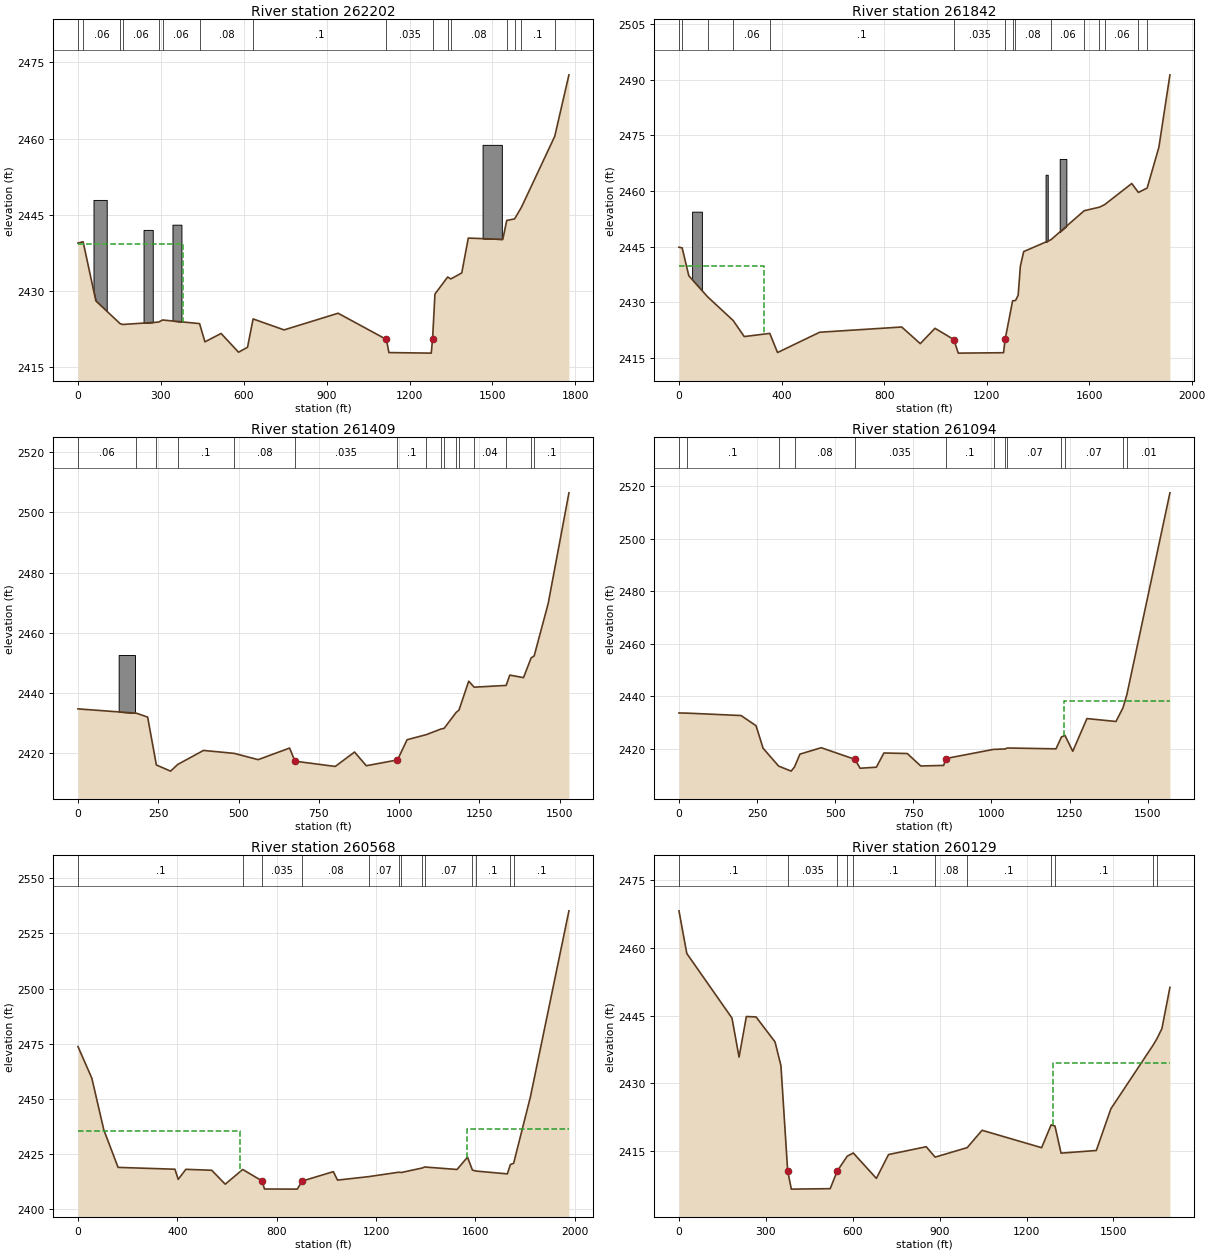
Type RM Length L Ch R = 1 ,262202  ,216.7,359.7,381.7
BEGIN DESCRIPTION:
channel burned 1.35':
lidar invert = 2419.15
effective invert = 2417.80
END DESCRIPTION:
XS GIS Cut Line= 3
2278945.91533007508416.8819300012277798.80092158509211.765371729
2277555.36158263509505.411929548
#Sta/Elev= 30
       0 2439.46    18.7 2439.71    64.7 2428.09     153 2423.58   162.4 2423.44
   291.8 2423.91   306.2 2424.32   440.1 2423.61   459.6 2420.02     518 2421.67
   581.2 2417.98   613.7 2418.95   633.9 2424.53     746 2422.37   941.5 2425.65
  1116.5 2420.49  1125.4 2417.91  1278.7  2417.8  1283.5 2420.62  1292.1 2429.43
  1338.1 2432.78  1349.6  2432.4  1389.1 2433.58  1412.7 2440.44  1537.7 2440.19
  1551.9 2443.92  1580.3 2444.21  1605.3 2446.53  1725.6 2460.46    1777 2472.57
#Mann= 16 ,-1,0
       0    .016       0    18.7     .06       0     153    .016       0
   162.4     .06       0   291.8    .016       0   306.2     .06       0
   440.1     .08       0   633.9      .1       0  1116.5    .035       0
  1283.5     .01       0  1338.1    .016       0  1349.6     .08       0
  1551.9    .016       0  1580.3     .05       0  1605.3      .1       0
  1725.6     .06       0
#XS Ineff= 2 , 0
          380.95 2439.33
Permanent Ineff=
       F       F
#Block Obstruct= 4 ,-1
   56.19  104.04 2447.95  237.35  270.66 2442.05  342.06  374.54 2443.08
 1464.44 1534.16 2458.79
Bank Sta=1116.5,1283.5
XS Rating Curve= 0 ,0
Exp/Cntr=0.3,0.1

Type RM Length L Ch R = 1 ,261842  ,256.1,433.3,458
BEGIN DESCRIPTION:
channel burned 1.86':
lidar invert = 2418.16
interpolated invert = 2416.30
END DESCRIPTION:
XS GIS Cut Line= 3
2278907.73741247508320.338941419 2277577.5291821508867.362978185
2277290.76327737509248.110986154
#Sta/Elev= 30
       0 2444.85    12.5 2444.67    38.5 2437.14     112 2431.46   211.5 2425.09
   254.6 2420.76   354.2 2421.62   384.5 2416.46   548.8 2421.93   868.9 2423.34
   941.2 2418.86   998.6 2422.99  1072.1 2419.96  1089.4  2416.3    1266 2416.41
 1272.25 2420.02  1301.4 2430.41  1312.6 2430.47    1323 2431.89  1331.6 2439.72
  1344.6 2443.67  1450.6 2446.84  1580.5 2454.68    1640 2455.64    1660 2456.31
  1766.1 2462.02  1791.9 2459.62  1826.1 2460.78  1871.9 2471.79    1915 2491.31
#Mann= 15 ,-1,0
       0    .016       0    12.5     .06       0     112    .016       0
   211.5     .06       0   354.2      .1       0  1072.1    .035       0
 1272.25      .1       0  1301.4    .016       0  1312.6     .08       0
  1450.6     .06       0  1580.5      .1       0    1640    .016       0
    1660     .06       0  1791.9    .016       0  1826.1      .1       0
#XS Ineff= 2 , 0
          333.33  2439.8
Permanent Ineff=
       F       F
#Block Obstruct= 3 ,-1
   51.28   89.44 2454.43 1429.94 1438.29 2464.38  1485.1 1510.99 2468.64
Bank Sta=1072.1,1272.25
XS Rating Curve= 0 ,0
Exp/Cntr(USF)=0,0
Exp/Cntr=0.3,0.1

Type RM Length L Ch R = 1 ,261409  ,236,315.2,368.2
BEGIN DESCRIPTION:
channel burned 0.66':
lidar invert = 2415.16
effective invert = 2414.50
END DESCRIPTION:
XS GIS Cut Line= 4
2278638.35199106 508187.186127072278001.82175818508396.265400645
 2277681.2335387 508349.803339852277179.44328212508535.651583028
#Sta/Elev= 30
       0 2434.63   182.1 2433.19     217 2431.89   244.2 2415.95   288.4 2413.91
   310.7 2416.13   390.9  2420.8   486.5 2419.82   561.1 2417.73   659.1 2421.59
   675.7 2417.22   801.3 2415.47   861.3 2420.26     898  2415.7   995.1 2417.64
  1024.9 2424.36  1084.3 2426.04  1131.2 2427.96  1140.1 2428.12  1177.9 2433.47
  1186.5  2434.2  1216.9 2443.85  1233.9 2441.85  1333.5 2442.44  1344.8 2445.87
  1387.5 2445.03  1411.4  2451.6  1420.7 2452.24  1464.3 2469.65    1529 2506.54
#Mann= 16 ,-1,0
       0     .06       0   182.1      .1       0   244.2     .04       0
   310.7      .1       0   486.5     .08       0   675.7    .035       0
   995.1      .1       0  1084.3     .07       0  1131.2    .016       0
  1140.1     .07       0  1177.9    .016       0  1186.5     .05       0
  1233.9     .04       0  1333.5     .05       0  1411.4    .016       0
  1420.7      .1       0
#Block Obstruct= 1 ,-1
  126.73  177.52 2452.55
Bank Sta=675.7,995.1
XS Rating Curve= 0 ,0
Exp/Cntr(USF)=0,0
Exp/Cntr=0.3,0.1

Type RM Length L Ch R = 1 ,261094  ,547,525.4,318.1
BEGIN DESCRIPTION:
channel burned 1.19':
lidar invert = 2413.67
interpolated invert = 2412.48
END DESCRIPTION:
XS GIS Cut Line= 4
2278606.08200797508045.4899712032277914.55548338508099.808545413
2277582.34877714507966.0987061572277078.65510767508093.332181654
#Sta/Elev= 30
       0 2433.56      26 2433.49   198.7 2432.58   246.7 2428.69   269.3  2420.1
   318.9 2413.31     359 2411.38   369.8 2412.99   387.1 2417.86   455.3 2420.31
   563.2 2415.87   579.7 2412.48   631.8 2412.88   655.9  2418.3   730.7 2418.09
   773.8 2413.34   847.1 2413.56   854.3 2416.19  1006.7 2419.67  1043.5 2419.82
  1051.1  2420.2  1206.7 2419.88  1224.1 2424.41  1235.5 2424.98  1260.3 2418.94
  1305.7 2431.42  1398.6 2430.31  1421.2 2435.56  1433.6  2440.6  1571.3 2517.49
#Mann= 13 ,-1,0
       0     .05       0      26      .1       0   318.9     .04       0
   369.8     .08       0   563.2    .035       0   854.3      .1       0
  1006.7     .08       0  1043.5    .016       0  1051.1     .07       0
  1224.1    .016       0  1235.5     .07       0  1421.2    .016       0
  1433.6     .01       0
#XS Ineff= 2 , 0
                         1233.13         2438.02
Permanent Ineff=
       F       F
Bank Sta=563.2,854.3
XS Rating Curve= 0 ,0
Exp/Cntr=0.3,0.1

Type RM Length L Ch R = 1 ,260568  ,450.8,439.8,420.9
BEGIN DESCRIPTION:
channel burned 1.43':
lidar invert = 2410.53
effective invert = 2409.10
END DESCRIPTION:
XS GIS Cut Line= 4
2278787.03058561507257.9449111852278108.68449801507569.240718506
2277927.48246091507569.2407185062276933.19435991507903.767556225
#Sta/Elev= 30
       0 2473.73    55.9 2459.37   104.1 2435.95   161.5 2418.96   390.4 2418.12
   403.6 2413.53   434.4 2418.08   538.5 2417.65   592.9 2411.34   663.3 2418.01
  740.93 2412.83   750.9 2409.16   882.9  2409.1   902.9 2412.76  1028.1 2417.02
    1045 2413.19  1171.6 2414.78  1291.1 2416.76  1302.4 2416.64  1386.9  2418.7
  1395.3 2419.14  1526.1 2418.01  1568.3  2423.6    1588 2417.73  1602.1  2417.3
  1728.7 2416.01  1740.7 2420.22    1754 2420.81  1821.5 2450.91  1976.6 2535.25
#Mann= 13 ,-1,0
       0      .1       0   663.3     .12       0  740.93    .035       0
   902.9     .08       0  1171.6     .07       0  1291.1    .016       0
  1302.4     .07       0  1386.9    .016       0  1395.3     .07       0
    1588    .016       0  1602.1      .1       0  1740.7    .016       0
    1754      .1       0
#XS Ineff= 2 , 0
          650.82 2435.58 1566.96         2436.43
Permanent Ineff=
       F       F
Bank Sta=740.93,902.9
XS Rating Curve= 0 ,0
Exp/Cntr(USF)=0,0
Exp/Cntr=0.3,0.1

Type RM Length L Ch R = 1 ,260129  ,199.5,203.2,225.6
BEGIN DESCRIPTION:
channel burned 1.24':
lidar invert = 2407.75
interpolated invert = 2406.51
END DESCRIPTION:
XS GIS Cut Line= 2
2278410.02293876506993.1877736022276793.80817753507504.193833394
#Sta/Elev= 30
       0 2468.23    27.1 2458.77   183.1 2444.44   207.5 2435.79   232.7 2444.79
   266.2  2444.7   331.7 2439.16   352.1 2433.89   375.3 2410.58   387.9 2406.51
   522.1 2406.61  546.35 2410.51   580.9 2413.81   601.8 2414.53   681.6 2408.89
   723.5 2414.18   853.6 2415.91   884.4 2413.61   995.1 2415.71  1046.5 2419.56
  1252.1  2415.7    1285 2420.77  1298.2  2420.5  1319.2 2414.49  1440.9 2415.08
  1491.2 2424.32  1636.6  2438.4  1650.6 2439.91  1667.4 2442.12  1695.1 2451.26
#Mann= 11 ,-1,0
       0      .1       0   375.3    .035       0  546.35      .1       0
   580.9    .016       0   601.8      .1       0   884.4     .08       0
   995.1      .1       0    1285    .016       0  1298.2      .1       0
  1636.6    .016       0  1650.6      .1       0
#XS Ineff= 2 , 0
                         1290.93         2434.46
Permanent Ineff=
       F       F
Bank Sta=375.3,546.35
XS Rating Curve= 0 ,0
Exp/Cntr(USF)=0,0
Exp/Cntr=0.3,0.1

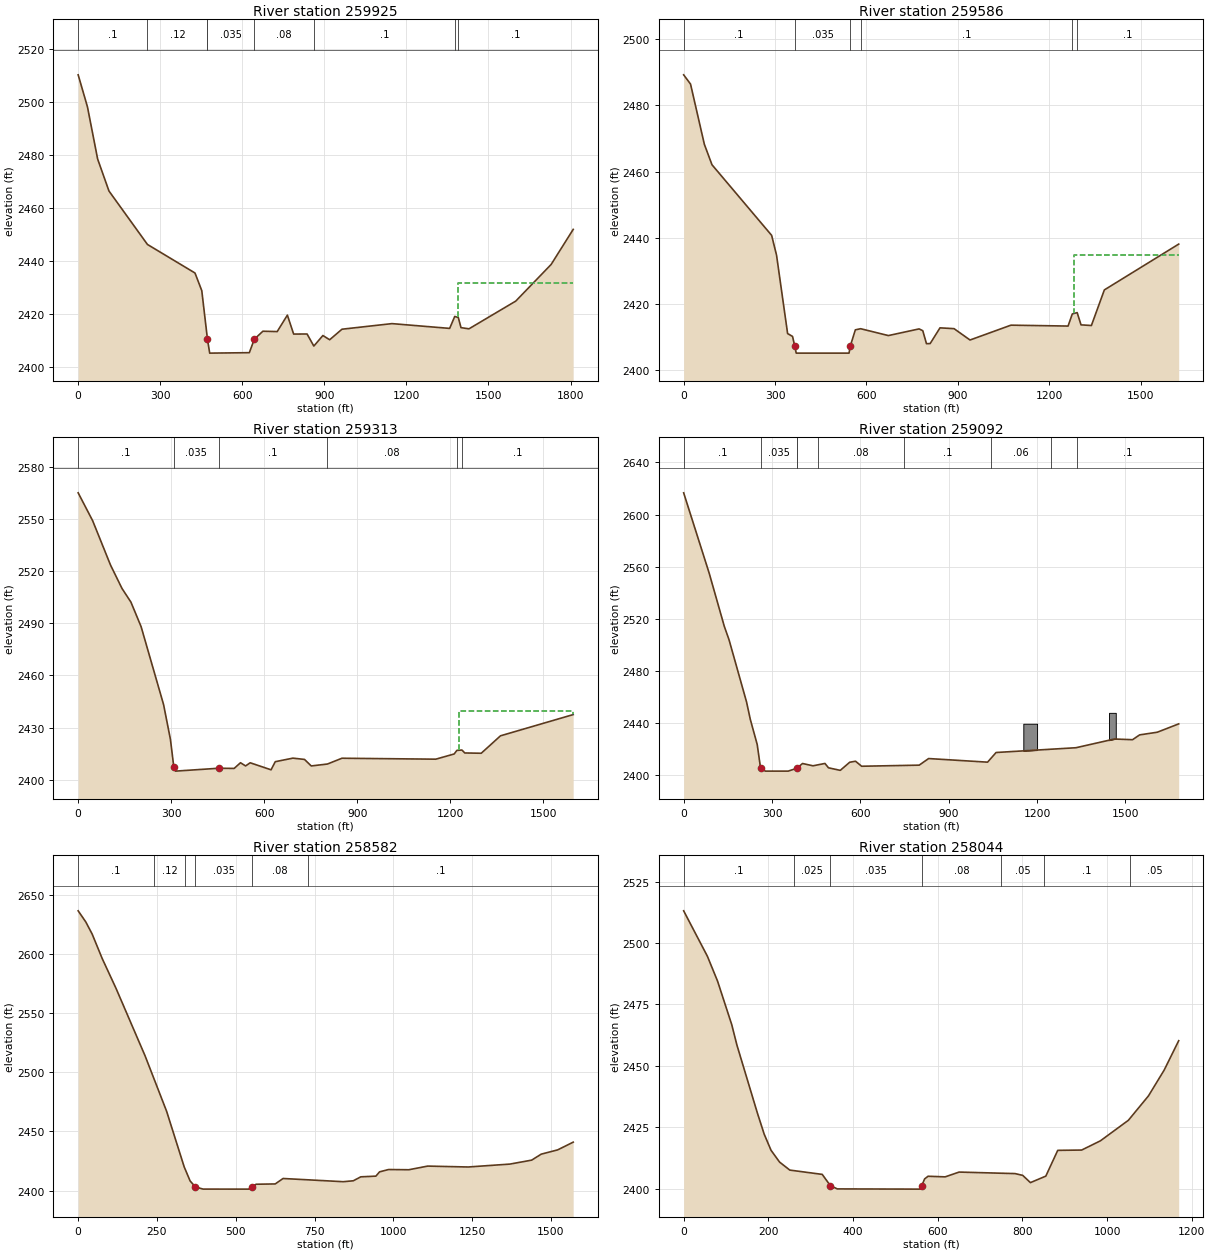
Type RM Length L Ch R = 1 ,259925  ,326.4,339.8,382.1
BEGIN DESCRIPTION:
channel burned 1.86':
lidar invert = 2407.16
effective invert = 2405.30
END DESCRIPTION:
XS GIS Cut Line= 3
2278437.02535534506799.0897935342277101.16646738507152.514408255
2276690.79203188507273.616046069
#Sta/Elev= 30
       0 2510.38      34 2498.27    71.2 2478.58   112.6 2466.51   253.3 2446.33
   427.1 2435.55   451.9 2428.88   472.32410.892   472.6 2410.57   480.8  2405.3
   625.7 2405.47   644.1 2410.57   675.3 2413.57   727.6 2413.44   764.8 2419.65
   787.7  2412.5   836.8 2412.52   861.5 2407.97   894.6 2411.95   919.4 2410.35
   964.4 2414.33    1147 2416.44    1358 2414.64  1376.6 2419.15  1389.6 2418.76
  1399.5 2414.92  1428.7 2414.48  1599.7 2424.95    1729 2438.78  1809.7 2452.03
#Mann= 8 ,-1,0
       0      .1       0   253.3     .12       0   472.3      .1       0
   472.6    .035       0   644.1     .08       0   861.5      .1       0
  1376.6    .016       0  1389.6      .1       0
#XS Ineff= 2 , 0
                         1387.28          2431.9
Permanent Ineff=
       F       F
Bank Sta=472.6,644.1
XS Rating Curve= 0 ,0
Exp/Cntr=0.3,0.1

Type RM Length L Ch R = 1 ,259586  ,280.5,272.8,242.4
BEGIN DESCRIPTION:
channel burned 0.85':
lidar invert = 2406.09
interpolated invert = 2405.24
END DESCRIPTION:
Node Name=U
XS GIS Cut Line= 3
     2278274.585      506551.2832277428.12173594506662.398248491
2276702.73528978506925.260739473
#Sta/Elev= 30
       0 2489.25    22.6 2486.46      68 2468.27      93 2462.11   288.9 2440.79
     305  2434.8   341.3 2411.15   357.5 2410.28  364.732407.377   369.6 2405.24
     543 2405.24   547.1 2407.38   563.7 2412.27   581.1 2412.61   672.1 2410.54
     773 2412.55   785.1 2412.01   797.2 2408.09   809.3 2408.12   841.6 2412.87
   887.7 2412.63   940.2  2409.2  1074.5 2413.68  1262.1 2413.41    1276 2417.07
  1291.9 2417.47  1304.6 2413.77  1338.7 2413.58  1381.2 2424.32  1625.3 2438.15
#Mann= 6 ,-1,0
       0      .1       0  364.73    .035       0   547.1     .08       0
   581.1      .1       0    1276    .016       0  1291.9      .1       0
#XS Ineff= 2 , 0
                         1280.79         2434.83
Permanent Ineff=
       F       F
Bank Sta=364.73,547.1
XS Rating Curve= 0 ,0
Exp/Cntr=0.3,0.1

Type RM Length L Ch R = 1 ,259313  ,228.8,221.3,246.3
BEGIN DESCRIPTION:
channel from lidar:
lidar invert = 2404.94
effective invert =2405.20
END DESCRIPTION:
XS GIS Cut Line= 4
2278173.63910122506250.3632174732277805.67198938506338.714418724
2277529.85593997506403.0459829722276651.99581905506725.876702145
#Sta/Elev= 30
       0 2564.94    46.8 2548.88   104.3 2523.44   141.4 2509.96   170.2 2502.11
   203.1 2487.97   275.6 2443.16   297.7 2423.14   308.7 2407.05   314.1 2404.94
   453.9  2406.6   503.2 2406.49   523.7 2409.76   540.1 2407.93   554.9 2409.74
   622.3  2405.7   635.8 2410.36   692.7 2412.41   730.1 2411.67   751.9 2407.92
   804.1 2409.02     851 2412.35  1153.6 2411.81    1213  2414.8  1221.7 2416.88
    1238 2417.06  1247.3 2415.38  1300.3 2415.22  1362.4 2425.24    1597 2437.45
#Mann= 6 ,-1,0
       0      .1       0   308.7    .035       0   453.9      .1       0
   804.1     .08       0  1221.7    .016       0    1238      .1       0
#XS Ineff= 2 , 0
                         1227.72         2439.35
Permanent Ineff=
       F       F
Bank Sta=308.7,453.9
XS Rating Curve= 0 ,0
Exp/Cntr(USF)=0,0
Minor Loss Coefficient=0
Exp/Cntr=0.3,0.1

Type RM Length L Ch R = 1 ,259092  ,480.1,509.9,510.1
XS GIS Cut Line= 4
2278029.69899466506026.700300136 2277658.0025083 506156.79407036
2276981.83420775506172.4248660382276371.49643402506188.583839939
#Sta/Elev= 30
       0  2616.7    86.4 2555.22   138.1  2514.1   154.2 2503.77   213.5 2456.12
   226.2 2442.81   249.7 2423.45   260.1 2406.85   263.7 2405.16   277.1 2402.98
   354.7 2402.97   384.42405.139   403.5 2408.83     439 2407.06   479.7 2408.86
   491.7 2405.53   531.7 2403.55   563.7 2409.78   583.5 2410.59   604.2 2406.72
   799.7 2407.56   831.7 2412.63  1031.8 2409.86  1060.8 2417.27  1331.9 2420.94
  1462.3 2427.63    1524  2427.1    1548  2430.8    1608 2432.85  1680.7 2439.25
#Mann= 9 ,-1,0
       0      .1       0   263.7    .035       0   384.4    .035       0
  384.42    .025       0     457     .08       0   747.8      .1       0
  1043.9     .06       0  1246.5     .05       0    1335      .1       0
#Block Obstruct= 2 ,-1
 1153.14 1199.89 2439.37  1444.2 1467.05 2447.73
Bank Sta=263.7,384.4
XS Rating Curve= 0 ,0
Exp/Cntr(USF)=0,0
Exp/Cntr=0.3,0.1

Type RM Length L Ch R = 1 ,258582  ,519.7,537.4,557.8
XS GIS Cut Line= 2
     2278036.505      505630.8422276466.75297633505688.328410656
#Sta/Elev= 30
       0 2636.32    24.3  2626.9    44.4  2616.7    76.4 2595.94   120.4 2570.66
   212.5 2513.71   280.6 2467.02   336.6 2419.88   355.2 2408.14   371.9 2403.07
   396.4 2401.25   540.7 2401.22   552.32403.164   564.7 2405.35   625.3 2405.61
   650.2  2410.2   840.9  2407.5   872.9 2408.26   896.9 2411.61   944.7 2412.19
   956.3 2415.82     985 2417.78    1049 2417.59  1109.1 2420.68  1237.2 2419.92
  1369.5 2422.36    1439 2425.71  1469.3 2430.77  1521.3 2434.36  1570.8  2440.9
#Mann= 6 ,-1,0
       0      .1       0     240     .12       0     340      .1       0
   371.9    .035       0   552.3     .08       0     730      .1       0
Bank Sta=371.9,552.3
XS Rating Curve= 0 ,0
Exp/Cntr=0.3,0.1

Type RM Length L Ch R = 1 ,258044  ,702.6,860.8,901.3
XS GIS Cut Line= 3
2278052.93002505505167.1521754412277016.82606934505037.058405217
2276909.96332952504972.011520105
#Sta/Elev= 30
       0 2513.08    56.2 2494.55    80.1 2484.47   113.6 2466.76   125.7 2458.52
   174.1 2430.82   190.2 2422.21   206.4 2415.63   226.5 2410.84   250.7 2407.57
   327.3 2405.82   346.3 2401.29   362.8 2399.91   557.1 2399.82  562.49 2401.25
   569.2 2403.98   577.3 2405.06   617.6 2404.81   650.7 2406.76   782.9 2406.14
   800.8 2405.42   819.1 2402.47   855.4 2405.11   883.6  2415.6   940.1 2415.72
   984.4 2419.48  1050.4 2427.83  1097.9 2437.77  1134.9 2448.24  1169.3 2460.23
#Mann= 7 ,-1,0
       0      .1       0     260    .025       0   346.3    .035       0
  562.49     .08       0     750     .05       0     850      .1       0
 1054.24     .05       0
Bank Sta=346.3,562.49
XS Rating Curve= 0 ,0
Exp/Cntr(USF)=0,0
Exp/Cntr=0.3,0.1

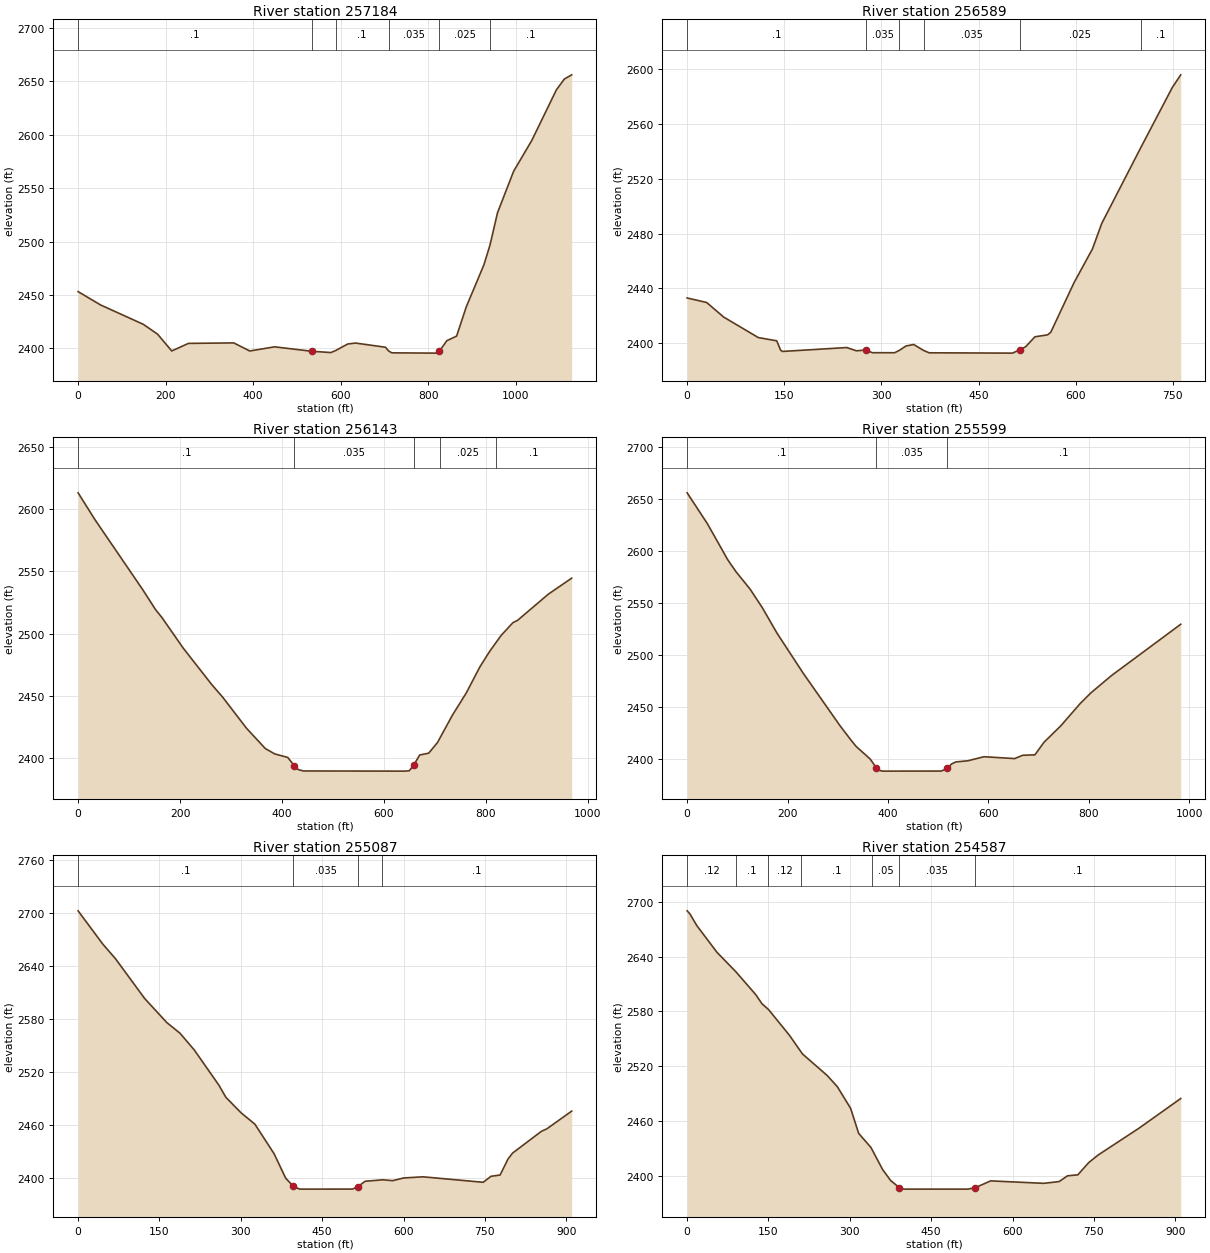
Type RM Length L Ch R = 1 ,257184  ,540.2,594.9,610.4
XS GIS Cut Line= 2
2278234.13206215504781.5170708482277402.46117393504019.539273822
#Sta/Elev= 30
       0  2453.2    51.5  2440.7   149.1 2422.59   181.7 2413.38     214 2397.68
   252.2 2404.77   355.8 2405.22   392.3 2397.66   448.9 2401.55   533.9 2397.41
   577.7  2396.2   588.6  2398.1   616.3 2404.22   634.1 2405.08   702.5 2401.16
   709.4 2397.77     717 2395.93     817 2395.66   825.5 2397.26   842.5 2407.25
     865 2411.58   886.9 2438.74   927.4 2478.25   941.2  2496.6   958.5 2526.99
   995.4 2565.85  1036.7 2594.51  1093.1 2641.98  1111.4 2652.09    1128 2655.97
#Mann= 6 ,-1,0
       0      .1       0   533.9    .035       0   588.6      .1       0
   709.4    .035       0   825.5    .025       0   941.2      .1       0
Bank Sta=533.9,825.5
XS Rating Curve= 0 ,0
Exp/Cntr(USF)=0,0
Exp/Cntr=0.3,0.1

Type RM Length L Ch R = 1 ,256589  ,522.2,445.5,406.6
XS GIS Cut Line= 2
     2278437.112      504321.6512277993.08564262503701.991405272
#Sta/Elev= 30
       0 2433.07    30.1 2429.79    56.5 2419.12   109.9 2404.17   138.4  2401.8
   144.3 2395.01   147.2 2394.04   246.6 2396.88   261.4 2394.51   276.2 2395.09
   276.2 2395.08     286 2393.12   320.4 2393.09   327.9 2394.86   338.1 2398.05
     350  2399.1   365.1 2394.79   373.7 2393.05   502.5 2392.81   514.2 2395.36
   522.8 2397.48   537.1 2404.72   556.6 2406.15   561.6 2408.06   597.3 2444.02
     626  2468.9   640.3 2487.48   700.5 2542.71   749.2 2586.63   762.3 2595.95
#Mann= 6 ,-1,0
       0      .1       0   276.2    .035       0   327.9      .1       0
   365.1    .035       0   514.2    .025       0   700.5      .1       0
Bank Sta=276.2,514.2
XS Rating Curve= 0 ,0
Exp/Cntr=0.3,0.1

Type RM Length L Ch R = 1 ,256143  ,625.5,543.7,481.9
XS GIS Cut Line= 3
2279023.98709566503895.2532611972278768.44576129503808.136897208
2278164.43897096503457.348338211
#Sta/Elev= 30
       0  2612.9    33.6 2591.07   126.6 2535.43   151.9 2519.35   164.6 2512.89
   206.3 2488.43   261.8 2459.46   284.2 2448.86   330.4 2424.25   367.4 2407.94
   385.9 2403.63   411.3 2400.85   424.5 2394.12   432.2 2391.04   442.1 2389.98
     641 2389.85   649.8 2390.16   658.2 2394.49   670.3 2402.78   687.9 2404.24
   705.1 2412.72   734.7 2434.85   761.7 2452.55   788.4 2473.42   807.8 2485.98
     830 2498.57   853.1 2508.82   862.4 2510.74   922.5 2531.63   968.5 2544.52
#Mann= 5 ,-1,0
       0      .1       0   424.5    .035       0   658.2      .1       0
  709.98    .025       0  819.98      .1       0
Bank Sta=424.5,658.2
XS Rating Curve= 0 ,0
Exp/Cntr(USF)=0,0
Exp/Cntr=0.3,0.1

Type RM Length L Ch R = 1 ,255599  ,555.3,512,469.6
XS GIS Cut Line= 3
     2279128.276      503101.3462278432.76280706503213.316696632
2278177.81117869503326.436581268
#Sta/Elev= 30
       0 2655.63    40.6 2625.76    81.1  2591.1    97.3 2579.81   125.6 2562.91
     150    2545     179 2520.73     231 2482.32   304.5  2431.7   326.1 2418.05
   336.4 2411.86   364.7 2399.61   376.9 2391.15   380.9 2388.96     389 2387.97
   506.5 2388.04   518.7 2390.83   526.8 2394.84   534.9 2396.78   559.2 2397.92
   591.6 2401.83   652.4 2400.03   668.6 2403.21   692.9 2403.63   710.9 2415.69
   744.5 2431.55     783 2452.94   804.8 2463.41   845.1 2479.74   983.4 2529.22
#Mann= 3 ,0,0
       0      .1       0   376.9    .035       0   518.7      .1       0
Bank Sta=376.9,518.7
XS Rating Curve= 0 ,0
Exp/Cntr=0.3,0.1

Type RM Length L Ch R = 1 ,255087  ,523,500.4,475.5
XS GIS Cut Line= 2
     2278848.877      502425.354     2278132.191      502986.123
#Sta/Elev= 30
       0 2702.68    45.2 2665.22    68.8 2648.48   122.8 2603.21   163.4 2576.05
     188 2563.81   214.1 2544.97   259.7 2504.88   272.3 2491.34   300.5 2473.61
   325.9 2460.81   361.5 2427.09   382.7 2399.48     397 2390.25   408.7 2387.09
     506 2387.14   516.1 2390.01   529.1 2395.99   561.7 2397.66   579.9 2396.71
   600.2 2399.74   635.8 2401.06   746.9 2394.84   761.2 2401.65     778 2403.08
   792.5 2421.13   801.1 2428.02   854.2 2452.65   864.3 2455.52     910 2475.55
#Mann= 4 ,-1,0
       0      .1       0     397    .035       0   516.1    .025       0
     560      .1       0
Bank Sta=397,516.1
XS Rating Curve= 0 ,0
Exp/Cntr=0.3,0.1

Type RM Length L Ch R = 1 ,254587  ,513.6,500,483.1
XS GIS Cut Line= 2
      2278379.22      502007.667     2277851.054      502748.707
#Sta/Elev= 30
       0 2689.95     5.2 2686.54    17.6 2674.03    54.9 2644.71    90.3 2623.09
   126.6 2598.29   138.1 2588.29     150 2582.12   188.5 2554.01   212.6 2533.56
   258.5 2509.82   276.9 2497.75   301.5 2473.98   316.2 2446.76   338.8 2431.38
   360.4  2407.2   375.2  2395.2   391.2 2387.43   399.7 2385.78   517.6 2385.78
     531 2387.32   559.6 2394.79   657.2 2392.12   685.8 2394.03   701.3 2400.34
   720.3  2401.4   740.3 2414.74   757.5 2422.98   832.3 2452.07     910 2484.81
#Mann= 7 ,-1,0
       0     .12       0      90      .1       0     150     .12       0
     210      .1       0     340     .05       0   391.2    .035       0
     531      .1       0
Bank Sta=391.2,531
XS Rating Curve= 0 ,0
Exp/Cntr=0.3,0.1

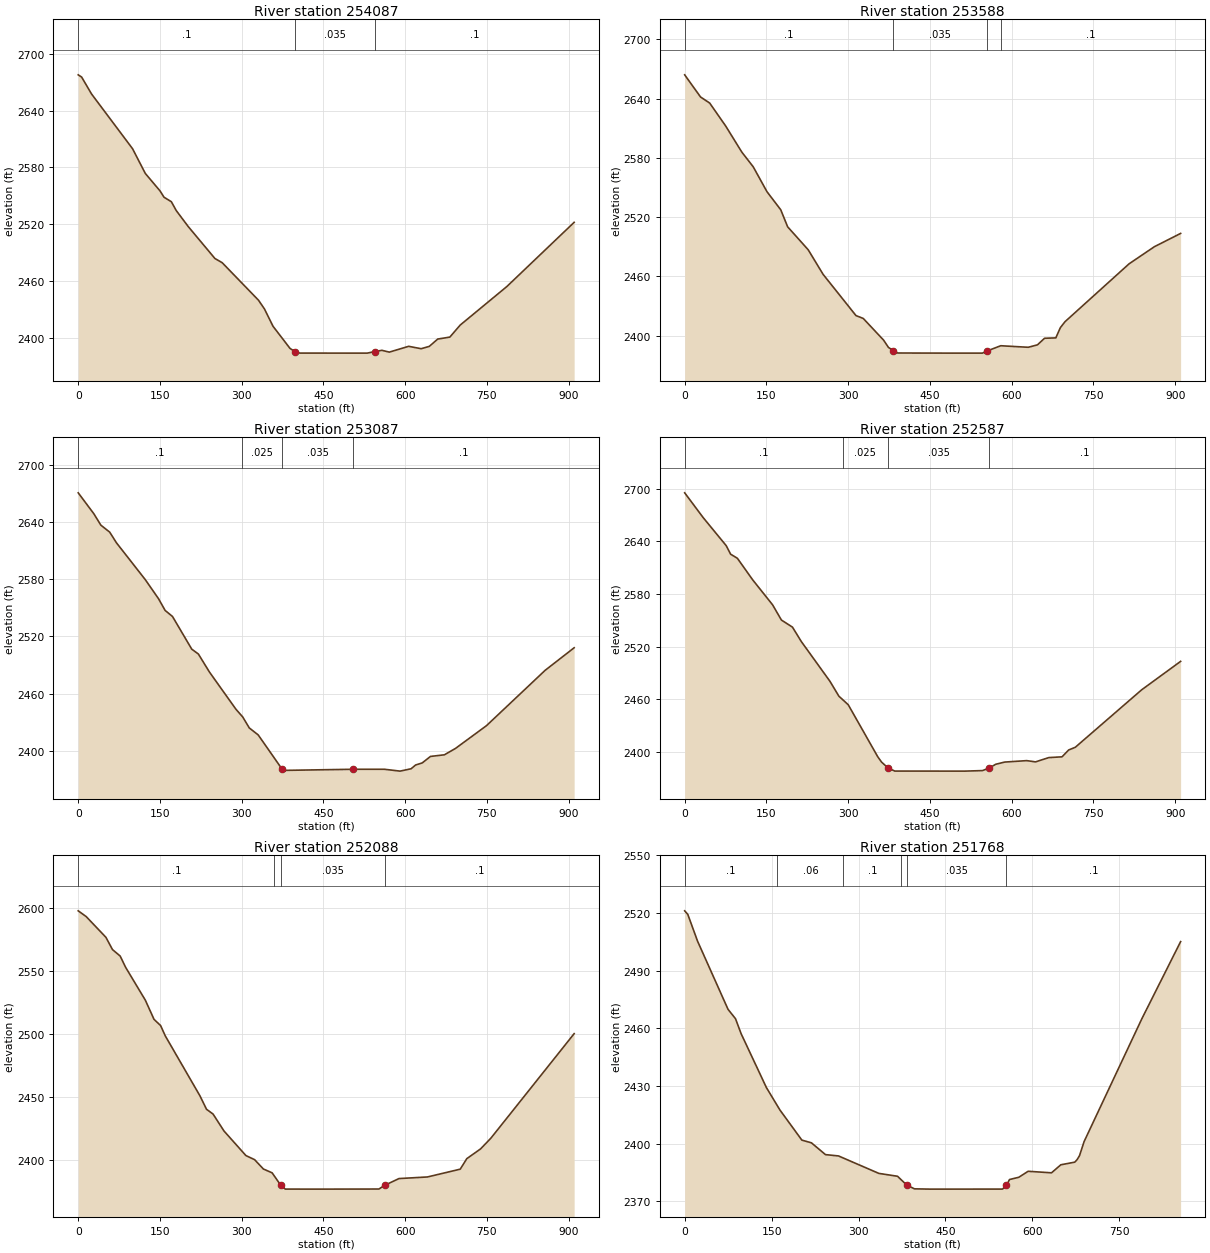
Type RM Length L Ch R = 1 ,254087  ,510.3,499.1,483.9
XS GIS Cut Line= 2
      2277878.81      501723.381     2277482.374      502542.489
#Sta/Elev= 30
       0 2677.88     6.3  2675.5    24.4  2657.7    99.8 2599.75   123.1 2573.73
   150.1 2555.29   157.5 2548.57   170.9 2543.85     180  2534.4     202 2517.51
   250.9 2483.83   264.2 2479.42   330.8  2439.8   341.7 2430.61   357.5 2412.25
   388.6 2388.92   397.5 2385.56   406.4 2383.94   530.4  2383.9   544.1 2385.57
   557.3 2386.85   570.8 2384.97   606.4 2391.09   629.2 2388.57   644.2 2391.03
   659.7 2398.77   681.9 2400.84     701 2413.58   786.5 2454.24     910 2522.07
#Mann= 3 ,-1,0
       0      .1       0   397.5    .035       0   544.1      .1       0
Bank Sta=397.5,544.1
XS Rating Curve= 0 ,0
Exp/Cntr=0.3,0.1

Type RM Length L Ch R = 1 ,253588  ,513.8,500.9,491.1
XS GIS Cut Line= 2
     2277352.553      501529.522     2277071.455       502395.02
#Sta/Elev= 30
       0  2664.1    29.1 2641.67    45.9  2635.5    75.3 2612.22   104.8 2585.87
   125.8 2570.93     151 2545.73   176.3  2527.4   188.9 2510.19   226.7 2486.87
     254 2462.01   314.3 2420.26   327.7 2417.33   365.1 2395.32   373.9 2388.02
   382.4 2384.88   390.8 2382.34   490.9 2382.22   546.4 2382.23   555.6 2384.56
     580  2389.7   630.5 2388.14   647.3 2390.61   660.3 2397.27     681 2397.65
   689.4 2408.07   697.8 2414.01   815.5  2472.7   861.8 2489.99     910 2503.46
#Mann= 4 ,-1,0
       0      .1       0   382.4    .035       0   555.6    .025       0
     580      .1       0
Bank Sta=382.4,555.6
XS Rating Curve= 0 ,0
Exp/Cntr=0.3,0.1

Type RM Length L Ch R = 1 ,253087  ,501.7,500,501.7
XS GIS Cut Line= 2
     2276808.687      501392.325     2276644.674      502287.422
#Sta/Elev= 30
       0 2670.41    28.7  2648.5    41.5 2636.61    57.8 2629.24    70.1 2618.14
   122.9 2579.65   147.3 2559.63   159.5 2547.28     173 2540.96   208.3 2506.79
   220.5 2501.64   240.8 2482.79   289.6  2443.7   301.8 2435.82   313.9 2424.28
   330.3 2416.94   373.8 2381.36   379.2 2379.84   505.1    2381   562.1 2380.99
   590.5 2379.05   610.9 2381.54     619 2385.45   631.2 2387.63   646.4 2394.44
   671.9 2396.13   692.2 2402.79   749.1 2426.62   856.9 2484.65     910  2508.2
#Mann= 4 ,-1,0
       0      .1       0     300    .025       0   373.8    .035       0
   505.1      .1       0
Bank Sta=373.8,505.1
XS Rating Curve= 0 ,0
Exp/Cntr=0.3,0.1

Type RM Length L Ch R = 1 ,252587  ,507.7,499.3,488.9
XS GIS Cut Line= 2
     2276308.262      501306.046     2276159.669      502203.832
#Sta/Elev= 30
       0 2695.08    34.1 2666.73    76.2  2634.9    84.3 2625.19    96.7 2620.53
   124.8 2595.96   161.3 2567.51   177.5 2550.18   197.8 2542.08     214  2525.7
   266.7 2480.27   282.9 2463.47   300.1  2453.7   354.1 2394.63   361.1 2388.45
     373 2381.76   385.5 2378.13   513.8 2378.06   546.5 2378.67   558.6 2381.58
   570.8 2385.89   587.2 2388.38   627.6 2390.01   643.8 2388.59   668.1 2393.48
   692.4 2394.35   704.6 2402.16   716.8 2405.25   838.4 2470.63     910 2503.08
#Mann= 4 ,-1,0
       0      .1       0     290    .025       0     373    .035       0
   558.6      .1       0
Bank Sta=373,558.6
XS Rating Curve= 0 ,0
Exp/Cntr=0.3,0.1

Type RM Length L Ch R = 1 ,252088  ,316.9,319.2,322.7
XS GIS Cut Line= 2
      2275776.59      501234.533     2275702.126      502141.482
#Sta/Elev= 30
       0 2598.11    14.7 2593.52    50.8  2577.1    62.9 2567.34      77 2562.21
    86.9 2553.35   123.1 2527.26   139.1 2511.97   151.2 2507.04   159.8 2498.81
   223.4 2451.23   235.4 2440.61   247.5 2436.75   267.5 2423.33   307.7 2403.84
   323.7 2400.56   339.8 2393.16   355.8 2390.13   371.9 2380.13   379.9 2377.22
     445 2377.19   551.8 2377.27   562.1 2380.16   588.6 2385.57   640.8 2386.84
     701 2393.04     713 2401.37   738.3 2409.12   757.2 2417.63     910 2500.61
#Mann= 4 ,-1,0
       0      .1       0     360    .025       0   371.9    .035       0
   562.1      .1       0
Bank Sta=371.9,562.1
XS Rating Curve= 0 ,0
Exp/Cntr=0.3,0.1

Type RM Length L Ch R = 1 ,251768  ,383.1,395.7,409.7
XS GIS Cut Line= 3
2275582.95074559501258.1669019032275440.91473566501492.526318285
2275375.57817109502070.612878694
#Sta/Elev= 30
       0 2521.06     5.4 2519.19    22.2 2505.31    74.8 2469.85    87.7 2464.97
    97.4 2457.17   141.1 2429.11   164.4 2417.48   202.2 2401.83   218.7 2400.42
     243 2394.28   265.4  2393.6   335.1 2384.52   367.3 2383.03   382.9 2378.54
   396.5 2376.49   423.7 2376.34   548.4 2376.36   555.3 2378.26   560.5 2381.33
   576.6 2382.51   592.7 2385.62     633 2384.82   649.1    2389   673.2 2390.37
   677.2  2391.7   681.3 2393.72   689.3 2401.09   788.9 2464.93   855.8 2505.04
#Mann= 6 ,-1,0
       0      .1       0     160     .06       0  274.04      .1       0
  374.04    .025       0   382.9    .035       0   555.3      .1       0
Bank Sta=382.9,555.3
XS Rating Curve= 0 ,0
Exp/Cntr(USF)=0,0
Exp/Cntr=0.3,0.1

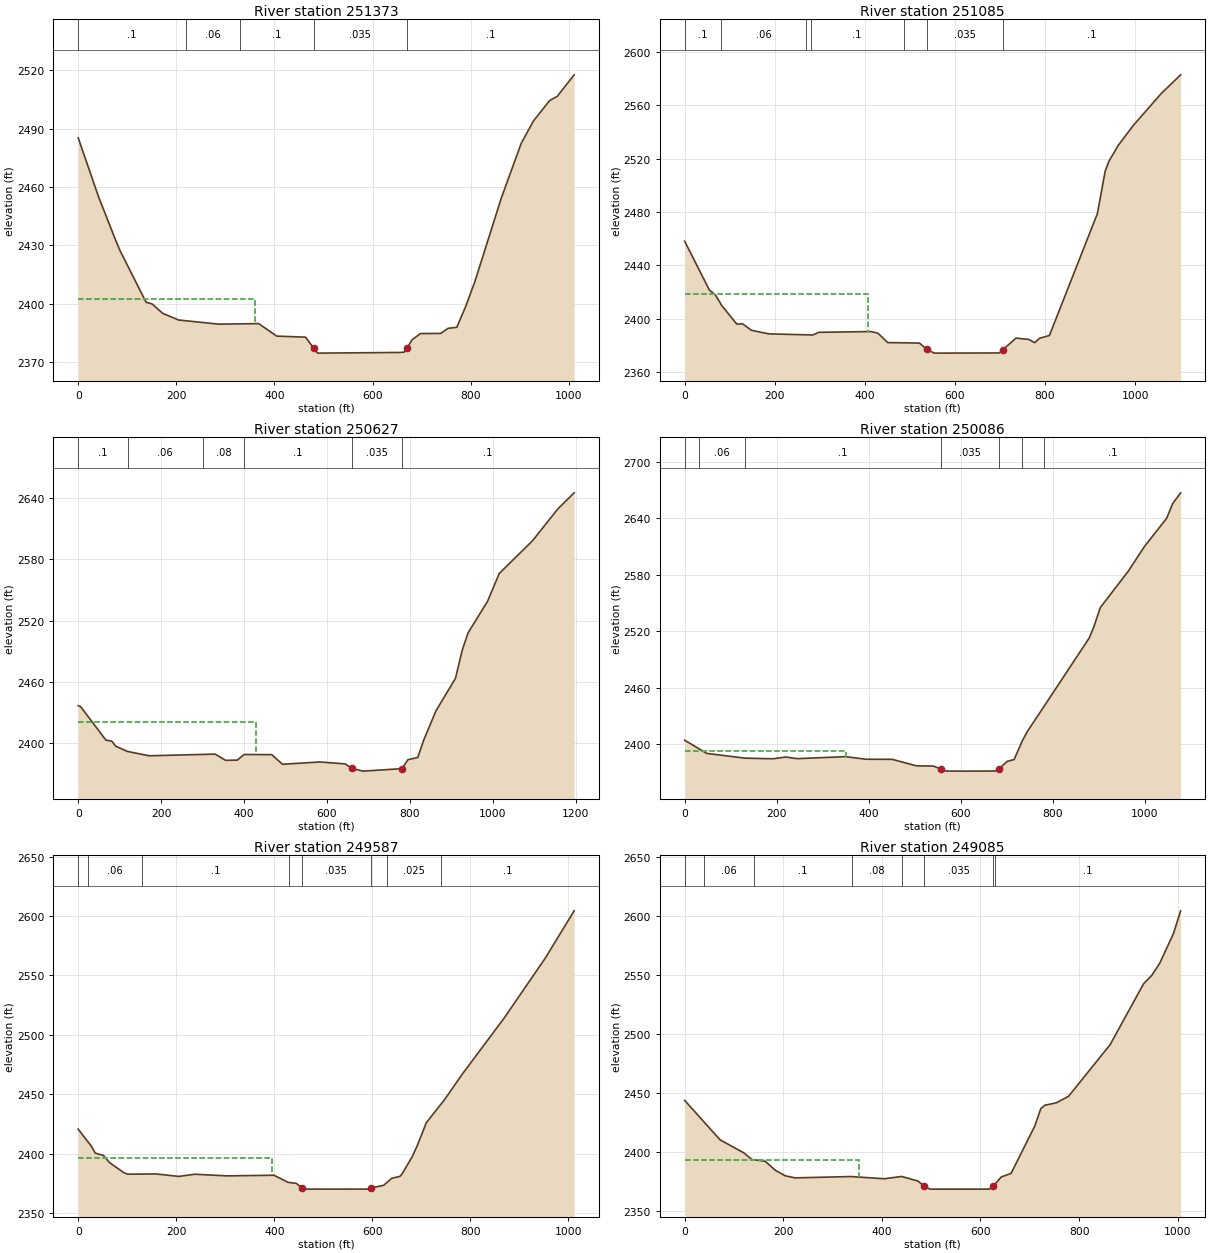
Type RM Length L Ch R = 1 ,251373  ,286.6,287.9,292.8
XS GIS Cut Line= 3
 2275279.3013601501118.7963940432275077.30255024501415.826872924
2274927.66314074502049.875515731
#Sta/Elev= 30
       0 2485.28    41.4 2455.03    75.4 2433.25    85.1 2427.42   138.3 2400.84
   150.8 2399.94   172.2 2395.14   204.7 2391.72   286.1  2389.6   367.9 2389.87
   404.5 2383.46   463.3 2382.92   479.8 2377.28     488 2374.72   656.5 2375.07
   664.7 2375.26   670.5 2377.41   680.5  2381.6   697.6 2384.78   738.7 2384.83
   753.6 2387.45   771.6 2387.98   789.9 2398.83   808.6 2411.62     862 2454.16
   902.8 2482.42   927.8 2493.94   960.6 2504.37   976.4 2506.61  1010.7 2517.62
#Mann= 5 ,-1,0
       0      .1       0     220     .06       0     330      .1       0
   479.8    .035       0   670.5      .1       0
#XS Ineff= 2 , 0
          360.79 2402.75
Permanent Ineff=
       F       F
Bank Sta=479.8,670.5
XS Rating Curve= 0 ,0
Exp/Cntr=0.3,0.1

Type RM Length L Ch R = 1 ,251085  ,426.4,458.3,481.3
XS GIS Cut Line= 3
2274990.74446394500958.7410080762274835.91688087501211.102214969
     2274637.851      501991.459
#Sta/Elev= 30
       0 2458.08    54.5 2421.65    68.6 2417.59    82.6 2409.74   115.5 2395.99
   128.7 2396.09   148.3 2391.26   186.9  2388.6   284.4 2387.77   298.2 2389.77
   413.8 2390.32   429.2 2389.11   450.9 2382.07   521.4  2381.7   537.1 2377.07
   554.1 2374.16   698.5 2374.29   706.8 2376.79   735.7 2385.44   764.5 2384.41
   776.9 2381.99     788 2385.28   809.9 2387.39   916.4 2478.79   933.7 2510.62
     942    2518     963 2530.05   995.6 2544.65  1057.9  2568.7  1101.2 2582.81
#Mann= 7 ,-1,0
       0      .1       0      80     .06       0     270     .08       0
     280      .1       0  486.07    .025       0   537.1    .035       0
   706.8      .1       0
#XS Ineff= 2 , 0
          406.99 2418.47
Permanent Ineff=
       F       F
Bank Sta=537.1,706.8
XS Rating Curve= 0 ,0
Exp/Cntr=0.3,0.1

Type RM Length L Ch R = 1 ,250627  ,488,541,583.3
XS GIS Cut Line= 3
2274715.56193326500764.7494241162274264.70561715501478.857494835
2274233.32181324501828.988759955
#Sta/Elev= 30
       0 2436.61     5.7 2435.73    66.7 2402.88    81.1  2401.8    90.4 2396.88
   118.8 2391.72     171 2387.47   330.4  2389.1   355.3 2383.01   383.7 2383.21
     400 2388.72   466.7 2388.59   492.8 2379.15   582.7  2381.4   643.6 2379.52
     661 2375.03   687.1 2372.41     781 2374.84   795.2 2383.59   818.9  2385.8
   833.1 2402.67   862.9 2431.62   909.8 2463.33   925.9 2490.61   940.1 2507.89
   987.4  2539.1  1015.5 2566.29  1095.8 2598.46  1156.7  2629.6  1196.1  2645.4
#Mann= 6 ,-1,0
       0      .1       0     120     .06       0     300     .08       0
     400      .1       0     661    .035       0     781      .1       0
#XS Ineff= 2 , 0
          428.62 2420.85
Permanent Ineff=
       F       F
Bank Sta=661,781
XS Rating Curve= 0 ,0
Exp/Cntr=0.3,0.1

Type RM Length L Ch R = 1 ,250086  ,483.5,498.8,510.5
XS GIS Cut Line= 2
2274575.10199192500701.399592036     2273592.669      501144.322
#Sta/Elev= 30
       0  2404.1    30.3 2395.21    48.1 2390.03   130.5 2385.02   191.9 2384.32
   219.8  2386.2   244.5 2384.46   349.9 2386.59   393.7 2383.83   450.8 2383.75
   503.4 2376.84   540.4 2376.56   556.1 2373.62   569.2 2371.25   603.9 2371.19
   676.5 2371.28   683.3 2373.76   700.9 2381.61   715.8 2383.47   733.9  2403.6
   744.7  2413.4   781.3 2440.34   879.1 2512.81   888.2 2523.45   903.3 2545.22
   963.8 2583.77   999.2 2610.16  1047.5 2640.29  1060.5 2655.84  1077.7 2667.22
#Mann= 7 ,-1,0
       0      .1       0    30.3     .06       0   130.5      .1       0
   556.1    .035       0   683.3      .1       0   733.9    .025       0
   781.3      .1       0
#XS Ineff= 2 , 0
          350.47 2393.02
Permanent Ineff=
       F       F
Bank Sta=556.1,683.3
XS Rating Curve= 0 ,0
Exp/Cntr=0.3,0.1

Type RM Length L Ch R = 1 ,249587  ,485.1,501.6,516.9
XS GIS Cut Line= 2
2274377.82193595500343.240472013     2273401.001      500606.838
#Sta/Elev= 30
       0 2420.54    26.6 2406.31    34.9 2400.32    51.4 2398.44    63.9 2392.37
    92.9 2383.99   101.1 2382.63   159.1 2382.83   205.2 2380.76   237.7 2382.59
   304.2 2381.21   399.4 2381.75   428.4 2375.75     445 2374.91   456.4 2371.02
   461.6 2370.06     590 2370.09   596.7 2370.96   623.2 2373.28   639.7 2379.22
   656.3 2380.78   660.5  2382.7   681.6 2397.52   691.9 2406.81   710.2 2425.97
   747.5 2445.43   782.6  2466.3   867.8 2513.34   952.4 2564.18  1011.8  2604.3
#Mann= 8 ,-1,0
       0      .1       0      20     .06       0     130      .1       0
     430    .025       0   456.4    .035       0   596.7      .1       0
     630    .025       0     740      .1       0
#XS Ineff= 2 , 0
          395.38 2396.11
Permanent Ineff=
       F       F
Bank Sta=456.4,596.7
XS Rating Curve= 0 ,0
Exp/Cntr=0.3,0.1

Type RM Length L Ch R = 1 ,249085  ,467.8,487.8,506.2
XS GIS Cut Line= 2
2274295.72387729499947.719765339     2273293.743      500036.123
#Sta/Elev= 30
       0 2443.42    71.8 2410.02     120 2398.99   136.1  2393.4   163.3 2391.84
   184.3 2384.11   204.3  2379.5   224.4 2377.79     337 2378.91   405.1 2377.06
     440 2378.97   473.4 2375.09   485.4 2370.79   497.5 2368.25   617.9 2368.25
     626 2370.66     630 2372.73     642 2378.51   662.1 2381.62   710.3 2421.93
   722.3  2436.4   730.4 2439.32   753.7 2441.36   778.6 2446.88   862.9 2490.65
   930.8 2542.23   947.2 2549.28   963.3 2559.44   991.4 2584.81  1005.9 2604.05
#Mann= 8 ,-1,0
       0      .1       0      40     .06       0     140      .1       0
     340     .08       0     440      .1       0   485.4    .035       0
     626    .025       0     630      .1       0
#XS Ineff= 2 , 0
          354.25 2393.34
Permanent Ineff=
       F       F
Bank Sta=485.4,626
XS Rating Curve= 0 ,0
Exp/Cntr=0.3,0.1