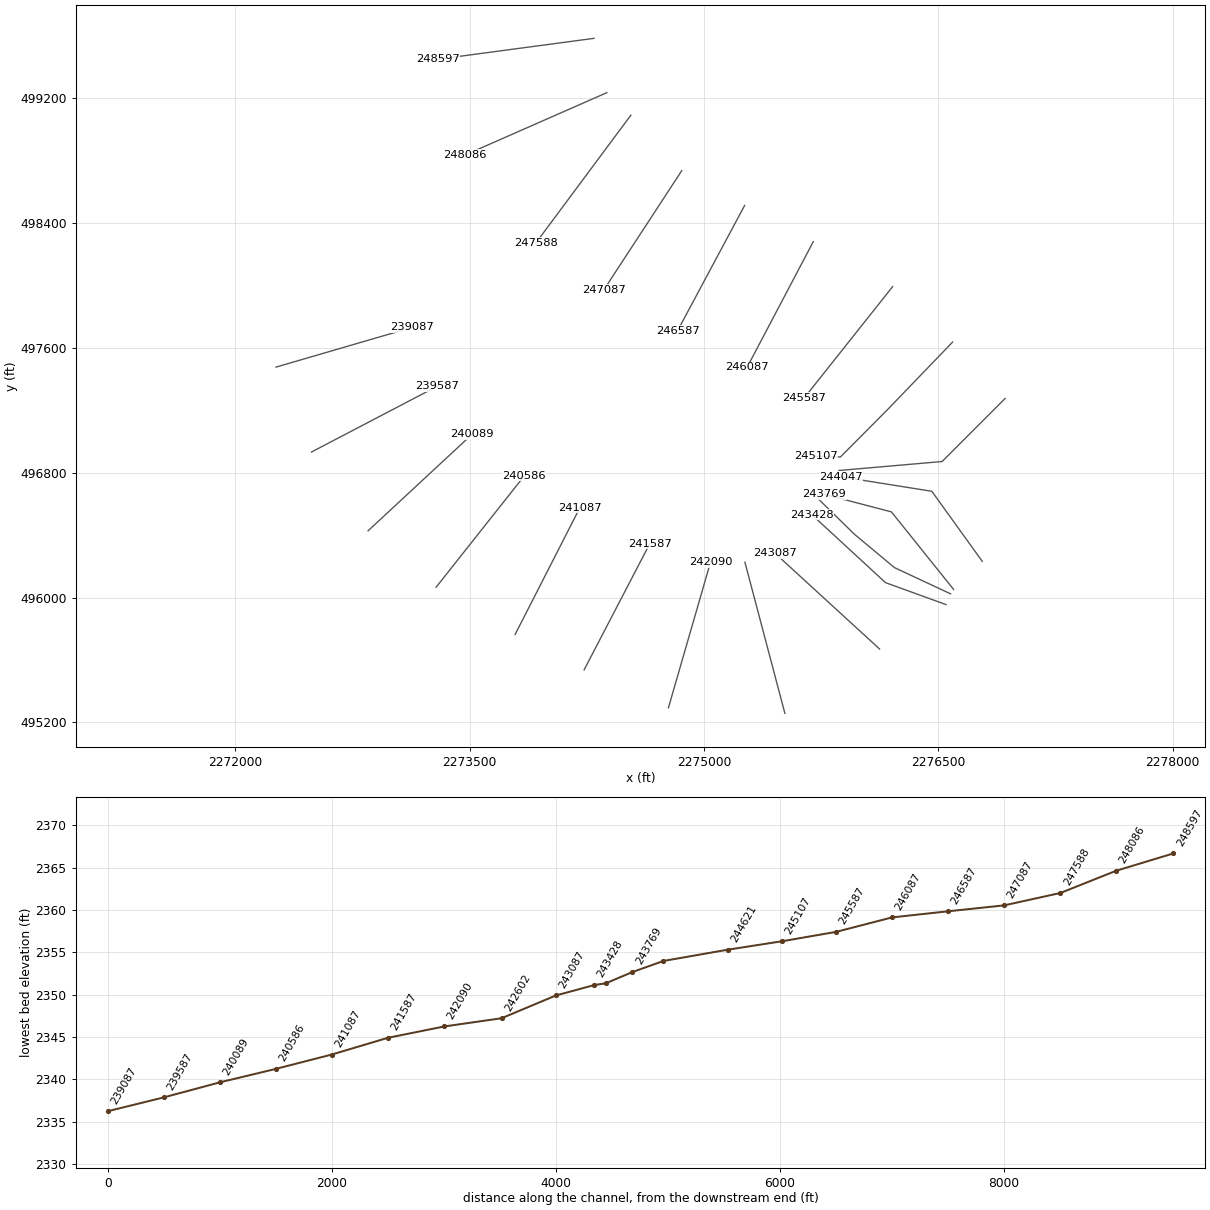
HEC-RAS study GRNBRRRV.prj: GRNBRRRV

--- GRNBRRRV.g01 (geometry) --- (continued)

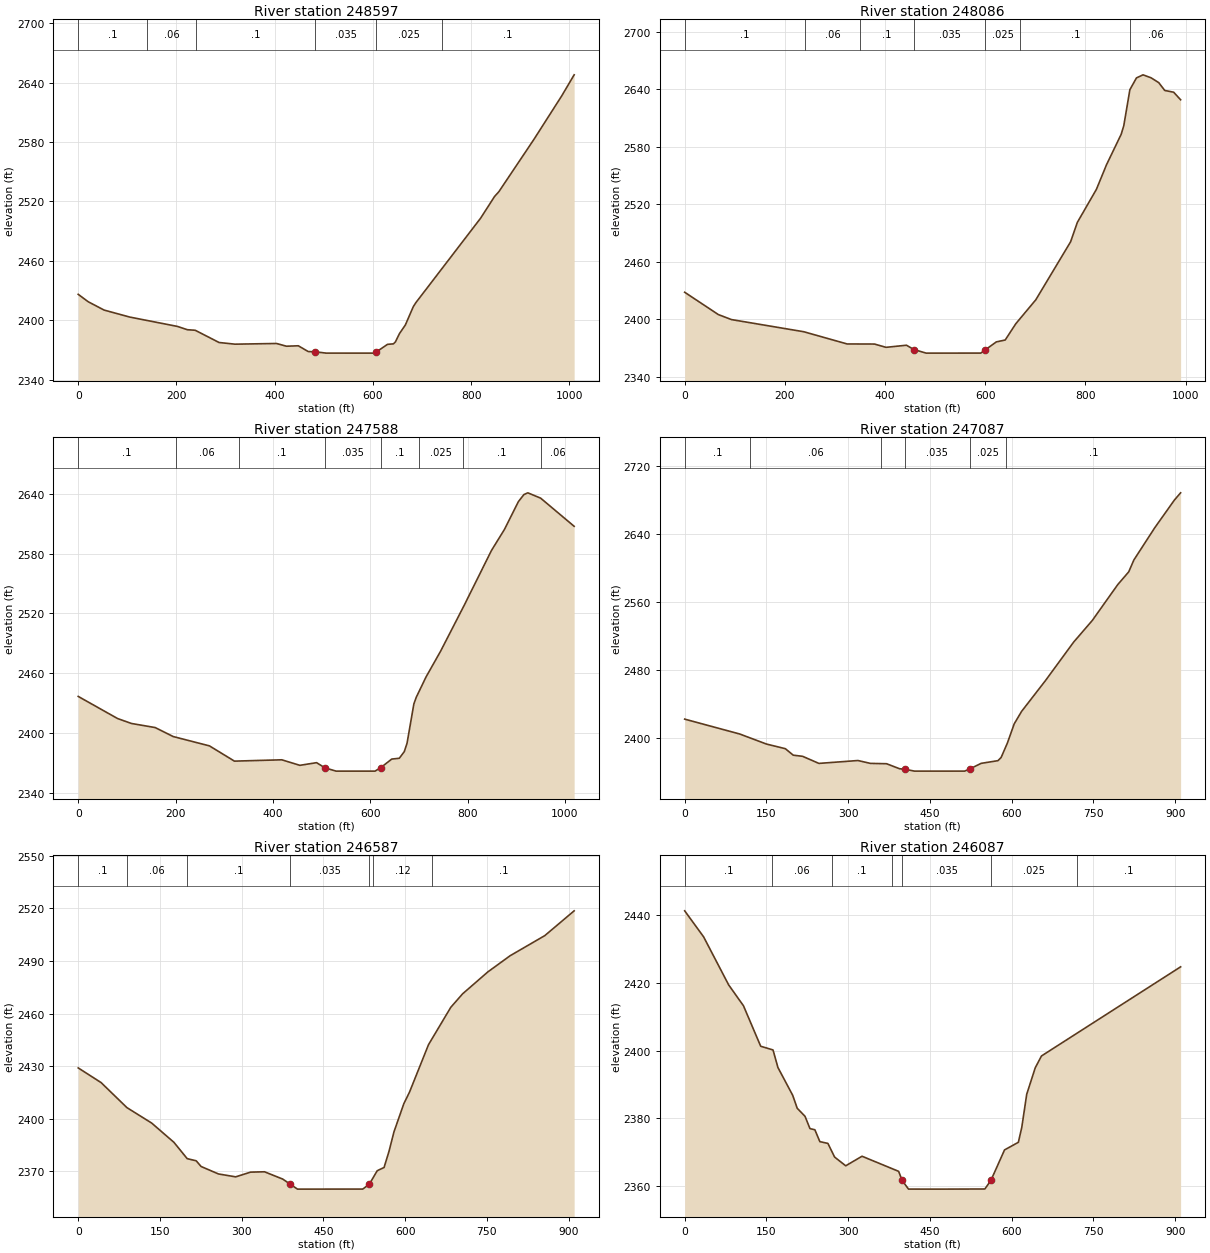
Type RM Length L Ch R = 1 ,248597  ,484.9,511.8,533.9
XS GIS Cut Line= 2
2274296.41093595499583.343351991     2273295.527       499449.37
#Sta/Elev= 30
       0 2426.08    20.4 2418.57    52.7 2410.17   105.2 2403.07     202 2393.66
   222.2 2390.32   238.3 2389.76   286.8 2377.41   319.1 2375.72   403.8 2376.41
     424 2373.65   448.2 2374.09   468.3 2368.26   482.6 2368.01   504.7 2366.69
   601.6 2366.67   607.2 2367.91   629.8 2375.55   641.9 2376.02   645.9 2378.05
     654 2386.31   666.1 2395.09   682.3 2413.62   687.3 2417.53   819.5 2503.11
   847.7  2524.9   856.4 2529.68   927.5 2582.32   984.5 2626.57  1009.8 2647.84
#Mann= 6 ,-1,0
       0      .1       0     140     .06       0     240      .1       0
   482.6    .035       0   607.2    .025       0     740      .1       0
Bank Sta=482.6,607.2
XS Rating Curve= 0 ,0
Exp/Cntr=0.3,0.1

Type RM Length L Ch R = 1 ,248086  ,451.5,497.1,538.6
XS GIS Cut Line= 2
2274377.70346663499235.109586652     2273471.529      498836.288
#Sta/Elev= 30
       0  2428.1    67.2 2404.83    93.4  2399.6   237.7 2386.93   324.3 2374.18
   378.9 2374.09     402 2370.66   442.7 2372.86   457.8 2368.34   482.1 2364.62
   591.3 2364.66   600.4 2368.17   622.2 2376.34   639.9  2378.3   661.1  2395.3
   700.9 2420.17   770.4 2480.65   783.9 2500.92     822 2535.42   842.2 2561.13
   871.4 2592.77   876.6 2601.69   888.8  2639.3   901.9 2651.59   915.1 2654.83
   931.2 2651.69   946.4  2646.7   958.5  2638.5   976.2 2636.72   990.1 2628.81
#Mann= 7 ,-1,0
       0      .1       0     240     .06       0     350      .1       0
   457.8    .035       0   600.4    .025       0     670      .1       0
     890     .06       0
Bank Sta=457.8,600.4
XS Rating Curve= 0 ,0
Exp/Cntr=0.3,0.1

Type RM Length L Ch R = 1 ,247588  ,497,501.5,506.5
XS GIS Cut Line= 2
2274531.72223197499090.778759955     2273924.252      498272.774
#Sta/Elev= 30
       0 2436.86    80.9 2414.69   109.5 2409.73   158.1 2405.66   195.2 2396.64
   269.6  2387.3     321 2372.01   418.2 2373.35   455.4 2367.81   489.7 2370.47
   506.9  2365.3   529.8    2362   609.8    2362   621.2 2365.35   644.1 2374.07
   659.7 2374.88   669.9 2381.52   675.6 2389.97   689.6 2429.33   694.5 2435.97
   714.5 2456.27   744.4 2482.06   792.8 2527.96     849 2583.06   875.7 2604.18
   904.3    2632   915.7 2639.12   923.7 2640.86     950 2635.55  1018.9 2607.32
#Mann= 8 ,-1,0
       0      .1       0     200     .06       0     330      .1       0
   506.9    .035       0   621.2      .1       0     700    .025       0
     790      .1       0     950     .06       0
Bank Sta=506.9,621.2
XS Rating Curve= 0 ,0
Exp/Cntr=0.3,0.1

Type RM Length L Ch R = 1 ,247087  ,493.8,500,507.9
XS GIS Cut Line= 2
     2274857.618      498735.396     2274360.091      497973.447
#Sta/Elev= 30
       0 2421.74   100.9 2404.25     150 2392.42   184.7 2386.95   199.2 2379.33
   216.5 2377.95   246.3 2369.62   317.9 2373.02   340.8 2369.65   370.5 2369.24
   394.4 2363.33   403.9 2362.82   421.7 2360.54   513.8 2360.56   522.9 2363.02
     544 2369.69   574.9 2372.87   580.7 2376.65   592.2 2393.69   604.6 2416.09
   618.2 2430.84   661.9 2467.01   713.6 2512.29   747.9 2537.83   794.5 2579.93
   814.8 2595.09   824.3 2609.13   862.5 2646.93   898.6 2679.57     910 2688.07
#Mann= 6 ,-1,0
       0      .1       0     120     .06       0     360      .1       0
   403.9    .035       0   522.9    .025       0     590      .1       0
Bank Sta=403.9,522.9
XS Rating Curve= 0 ,0
Exp/Cntr=0.3,0.1

Type RM Length L Ch R = 1 ,246587  ,499.5,500,501.5
XS GIS Cut Line= 2
     2275259.969      498512.051     2274830.811      497709.602
#Sta/Elev= 30
       0 2428.99      42 2420.62    89.4 2406.33   134.8 2397.52   175.6 2386.55
     200 2377.22   216.5    2376   225.5 2372.75   257.3  2368.5     289 2366.85
   316.2 2369.53   341.9 2369.73   375.2 2365.58   388.8  2362.7   402.4 2359.84
   522.1 2359.87   534.1 2362.61   548.7 2370.35   561.2 2372.19   570.3 2381.41
   579.3 2392.43   597.5  2408.6   607.8 2415.11   642.8 2442.27   683.7 2463.58
   705.4 2471.27   751.7 2483.77   792.5 2492.98   856.2 2504.47     910  2518.6
#Mann= 7 ,-1,0
       0      .1       0      90     .06       0     200      .1       0
   388.8    .035       0   534.1    .025       0     540     .12       0
     650      .1       0
Bank Sta=388.8,534.1
XS Rating Curve= 0 ,0
Exp/Cntr=0.3,0.1

Type RM Length L Ch R = 1 ,246087  ,520,500.4,484
XS GIS Cut Line= 2
     2275699.626      498280.637      2275276.05      497475.229
#Sta/Elev= 30
       0  2441.3    34.7 2433.63    80.7 2419.43   107.9 2413.26   139.5 2401.31
   162.1 2400.22   171.1 2395.04   198.2 2386.83   206.5    2383   220.8 2380.63
   229.9 2376.99   238.9 2376.65     248 2373.15   262.8 2372.62   275.1 2368.59
   295.5 2366.01   325.4 2368.83   392.6 2364.37     399 2361.69   410.7 2359.13
   470.1 2359.12   550.8 2359.16   561.9 2361.69   586.9  2370.7   612.3 2372.95
   618.6 2377.41   627.6 2387.13   643.3 2394.97   654.7 2398.44     910 2424.76
#Mann= 7 ,-1,0
       0      .1       0     160     .06       0     270      .1       0
     380    .025       0     399    .035       0   561.9    .025       0
     720      .1       0
Bank Sta=399,561.9
XS Rating Curve= 0 ,0
Exp/Cntr=0.3,0.1

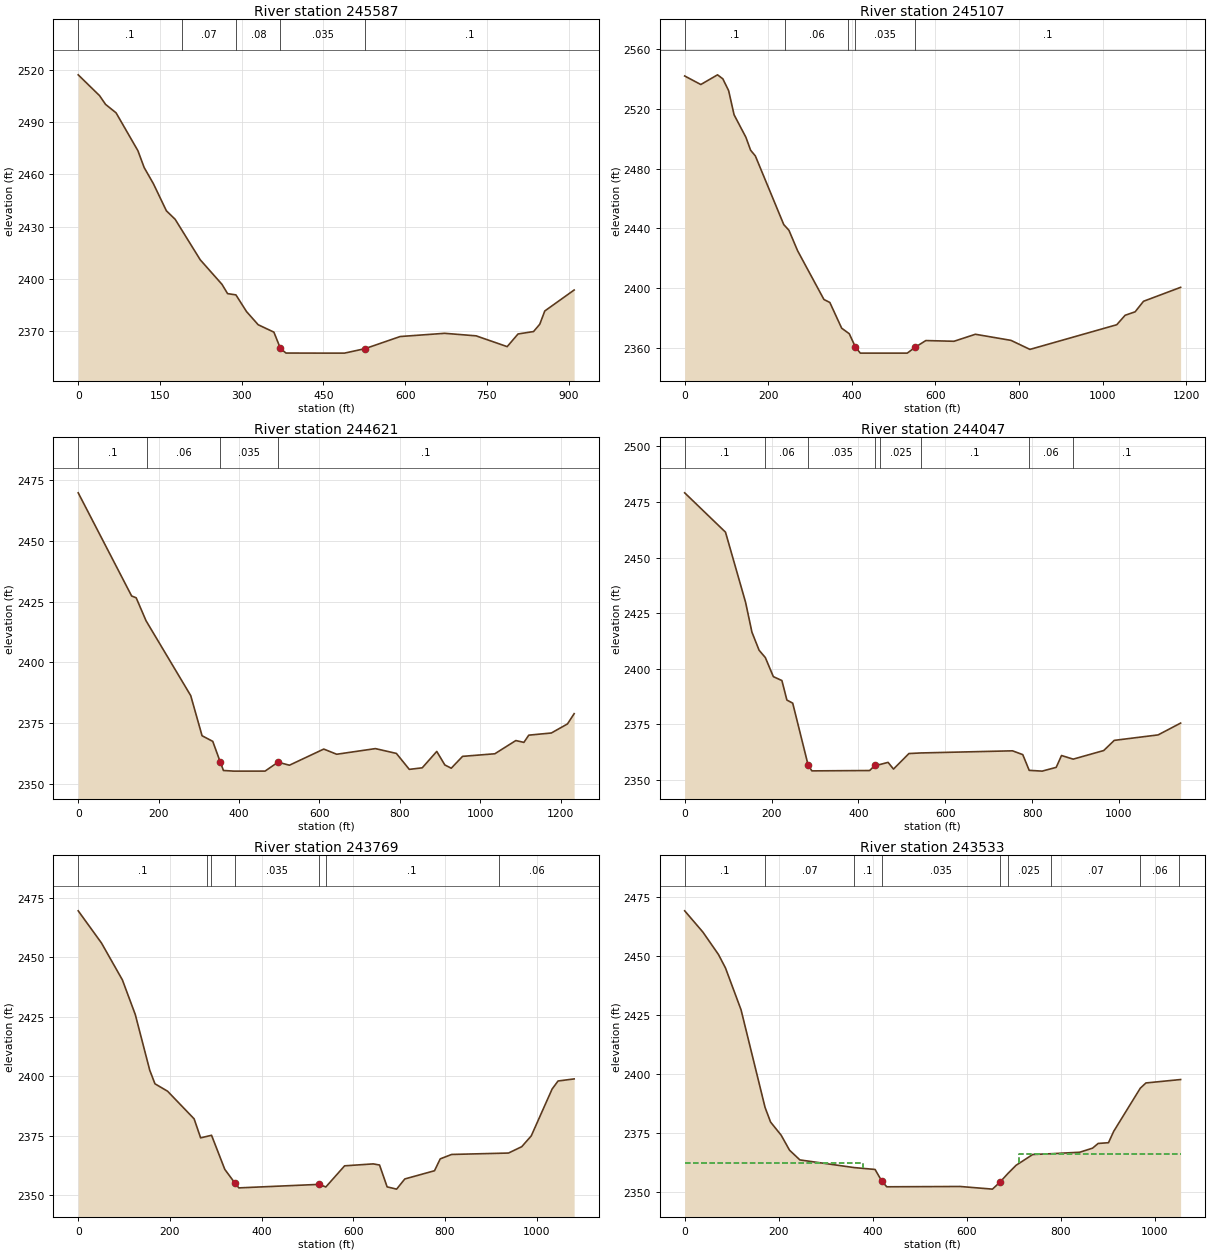
Type RM Length L Ch R = 1 ,245587  ,490.6,479.7,471.2
XS GIS Cut Line= 2
     2276207.372       497991.91     2275641.677      497278.949
#Sta/Elev= 30
       0 2517.21    39.2 2505.25    50.2 2500.23    69.5 2495.38   109.6 2473.61
     121 2463.99     138 2454.68   161.8 2439.14   177.9 2434.25   223.9 2411.02
   263.9 2396.88   274.1 2391.58   289.4 2390.86   308.9 2381.25   330.3  2373.7
   359.1 2369.46   371.1 2360.09   381.3 2357.45   462.6 2357.41   488.6 2357.41
   526.4 2359.98   590.8 2366.94   672.4 2368.79   730.2 2367.33   787.2 2361.14
   807.1  2368.4   835.6  2369.8     847    2374   856.2 2381.61   910.1 2393.65
#Mann= 5 ,-1,0
       0      .1       0     190     .07       0     290     .08       0
   371.1    .035       0   526.4      .1       0
Bank Sta=371.1,526.4
XS Rating Curve= 0 ,0
Exp/Cntr=0.3,0.1

Type RM Length L Ch R = 1 ,245107  ,487.5,486,484.1
XS GIS Cut Line= 4
     2276591.502      497636.9622276171.71822153497200.723134314
2275873.42184371496900.5728887012275715.44699384496904.436998904
#Sta/Elev= 30
       0  2542.2    38.6 2536.47    78.6 2542.97    91.3 2540.27   105.2 2532.34
   118.2 2516.18   146.5 2501.08   157.8 2492.38   169.1 2488.56     237 2442.57
   249.5 2438.68   270.2 2424.97   333.2 2392.28   347.3 2390.29   375.6 2373.05
   393.8 2369.32   408.6 2360.37   420.2 2356.31   532.6 2356.31     551 2360.17
     577 2364.74   644.4 2364.26   695.6 2368.96   780.7 2364.87   826.1 2358.81
  1033.8 2375.35  1053.8 2381.69  1077.8 2384.03  1097.8 2391.08  1186.6 2400.44
#Mann= 5 ,-1,0
       0      .1       0     240     .06       0     390      .1       0
   408.6    .035       0     551      .1       0
Bank Sta=408.6,551
XS Rating Curve= 0 ,0
Exp/Cntr=0.3,0.1

Type RM Length L Ch R = 1 ,244621  ,727.6,574.2,399.4
XS GIS Cut Line= 3
2276927.42994403497275.2305866522276524.30724274 496871.47518138
2275863.70053875496813.915709366
#Sta/Elev= 30
       0 2469.75   132.9 2427.33   144.2 2426.59   168.8 2417.13   279.9 2386.36
   308.1 2369.86   334.7 2367.55   353.3 2359.09   361.3 2355.57   387.3 2355.31
   464.8 2355.32   497.1 2358.99   525.4 2357.74   610.8 2364.38     643 2362.25
   739.3 2364.57   791.5 2362.59   823.6 2356.03   855.8 2356.67   891.9 2363.41
     912 2357.85     928 2356.51   956.1 2361.38  1036.4 2362.45  1088.6 2367.88
  1108.7 2367.13  1120.8  2370.1    1177 2370.99  1217.1 2374.72  1233.7 2378.93
#Mann= 4 ,-1,0
       0      .1       0     170     .06       0   353.3    .035       0
   497.1      .1       0
Bank Sta=353.3,497.1
XS Rating Curve= 0 ,0
Exp/Cntr=0.3,0.1

Type RM Length L Ch R = 1 ,244047  ,271.4,277.6,287
XS GIS Cut Line= 3
2276781.58576803496231.3681759962276458.60041873496680.721229277
2275877.26412541      496773.609
#Sta/Elev= 30
       0 2479.12      94 2461.43   140.2 2429.93   154.9 2416.46   171.4 2408.33
   185.7 2405.06   204.2 2396.47   223.9 2394.71   235.4 2385.94   248.8 2384.55
  284.22 2356.76   292.9 2354.09   425.9 2354.25   437.9 2356.52   450.5    2357
   468.4 2357.92   480.9 2354.91   516.4 2361.89   543.8 2362.15     755 2363.11
   778.6  2361.4   793.4 2354.33   823.2 2353.98   855.6 2355.68   867.8    2361
   894.7 2359.37     965 2363.24   989.3 2367.81  1090.3 2370.27  1142.1 2375.58
#Mann= 8 ,-1,0
       0      .1       0   185.7     .06       0  284.22    .035       0
   437.9      .1       0   450.5    .025       0   543.8      .1       0
   793.4     .06       0   894.7      .1       0
Bank Sta=284.22,437.9
XS Rating Curve= 0 ,0
Exp/Cntr=0.3,0.1

Type RM Length L Ch R = 1 ,243769  ,210.2,235.7,281.8
BEGIN DESCRIPTION:
xs 4
END DESCRIPTION:
XS GIS Cut Line= 3
2276597.99157459496051.6614280772276199.92145316496548.673834019
2275769.63756468  496661.4220187
#Sta/Elev= 30
       0 2469.46    50.7 2455.97    96.3 2440.49   124.5 2425.93     156 2402.57
   167.4 2396.87   194.9 2393.76   252.8 2382.16     267 2374.18   290.8 2375.27
   319.7 2360.96     342 2355.15   350.4 2353.19     526 2354.67     540 2353.57
     581 2362.45   643.5 2363.26   657.2 2362.78   673.7 2353.62   694.4 2352.67
   712.3 2356.94   777.1 2360.39   789.5 2365.36   814.3 2367.22   938.4 2367.81
   967.3 2370.48     988    2375  1033.5 2394.66  1046.5 2398.05  1081.6 2398.92
#Mann= 7 ,-1,0
       0      .1       0     280     .08       0     290     .07       0
     342    .035       0     526    .025       0     540      .1       0
  916.77     .06       0
Bank Sta=342,526
XS Rating Curve= 0 ,0
Exp/Cntr(USF)=0,0
Exp/Cntr=0.5,0.3

Type RM Length L Ch R = 1 ,243533  ,110.7,105.5,94.8
BEGIN DESCRIPTION:
structure xs 3
END DESCRIPTION:
XS GIS Cut Line= 4
2276578.16856488496023.7777706462276219.01773913496191.761253672
2275963.88027653496404.5994298852275730.82682175496632.797750981
#Sta/Elev= 30
       0 2469.33    38.7 2460.33    71.8 2450.84    86.8 2445.11   119.9 2427.38
     171 2385.98   182.7 2379.79   205.3 2374.19     223 2367.87   245.1 2363.73
   360.6 2360.48     405 2359.69   419.4  2354.7   429.9 2352.34     586 2352.47
   654.7 2351.35   671.1 2354.39   686.7 2357.81   704.7 2361.42   740.3 2366.03
   779.9 2366.36   840.3 2366.99   867.6 2368.72   879.5 2370.71   901.5 2371.03
   912.5 2375.83   969.1 2394.13   981.1 2396.36  1051.4 2397.74  1054.9 2397.81
#Mann= 9 ,-1,0
       0      .1       0     171     .07       0   360.6      .1       0
   419.4    .035       0   671.1     .07       0   686.7    .025       0
   779.9     .07       0   969.1     .06       0  1051.4      .1       0
#XS Ineff= 2 , 0
             379 2362.43     711         2366.32
Permanent Ineff=
       F       F
Bank Sta=419.4,671.1
XS Rating Curve= 0 ,0
Exp/Cntr=0.5,0.3

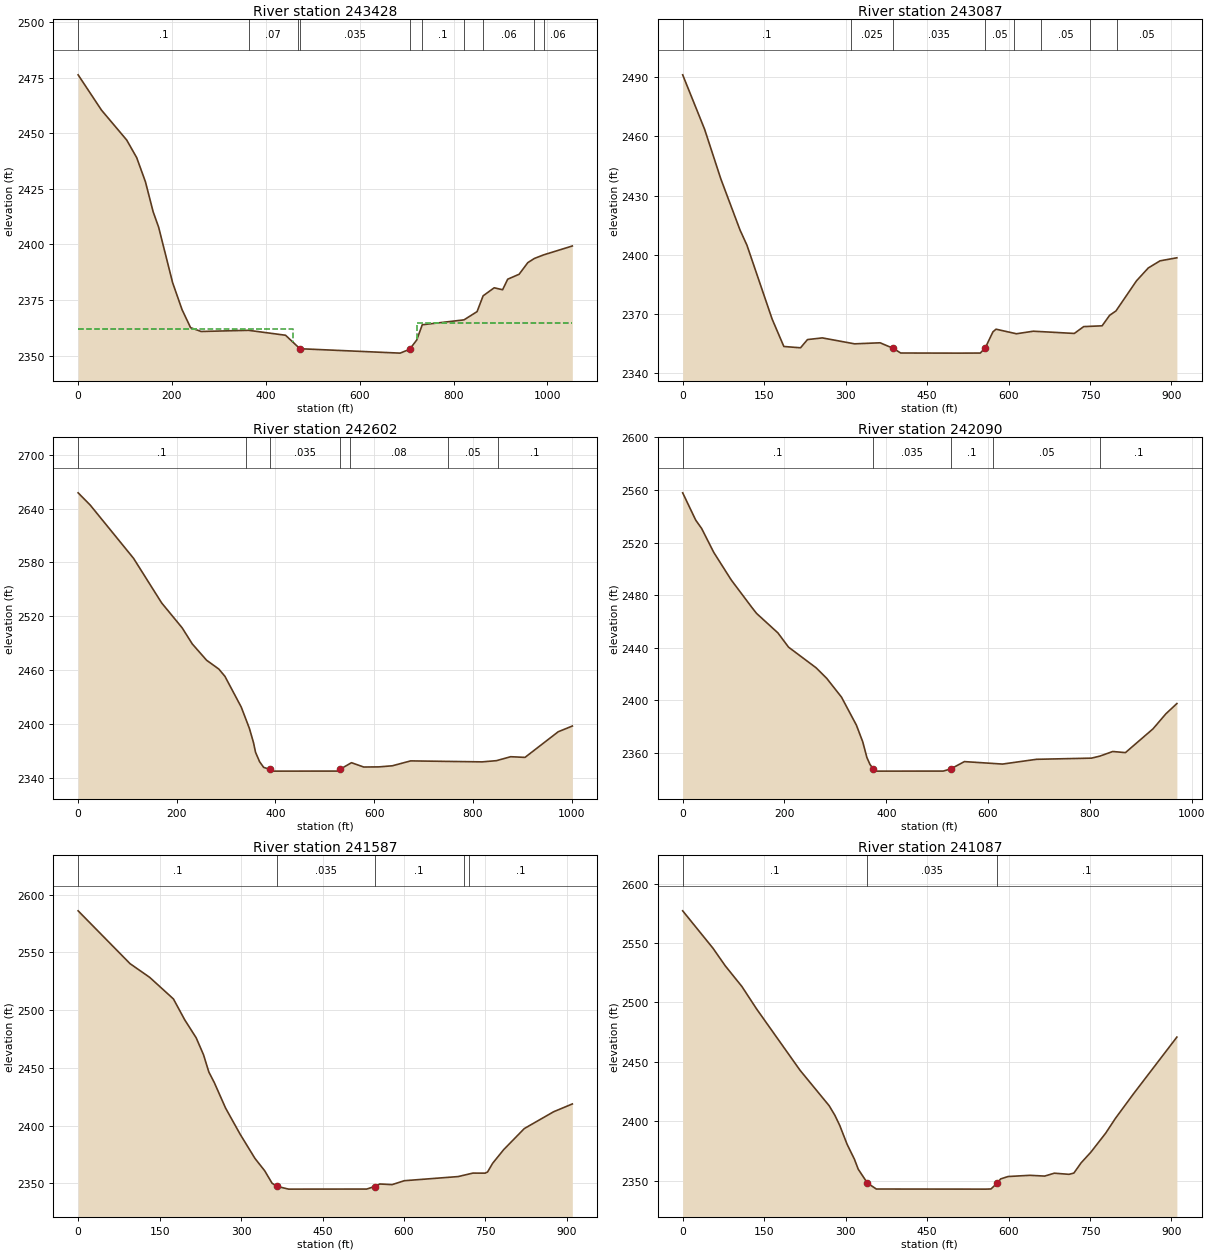
Type RM Length L Ch R = 1 ,243428  ,346,340.9,340.6
BEGIN DESCRIPTION:
structure xs 2
END DESCRIPTION:
XS GIS Cut Line= 3
2276549.46098291 495954.601030862276162.09928565496095.316096395
2275690.94097633496530.109838217
#Sta/Elev= 30
       0 2476.22    49.8 2460.35   103.5 2446.92   124.8    2439   143.5 2428.12
   159.8 2414.71   171.6 2407.72   201.4 2382.78   221.5 2370.67   239.7 2362.57
   262.1 2360.86   363.1 2361.38     442 2359.17     468 2354.04   473.9  2353.1
   686.2 2351.13   706.4 2352.83   721.6 2357.03   733.4 2363.88   822.4 2366.08
   850.2 2369.79   863.1 2376.89   886.7  2380.5   904.6 2379.62   915.5 2384.36
   939.8 2386.58   958.3  2391.8   972.5  2393.7   992.3 2395.31  1053.2 2399.29
#Mann= 10 ,-1,0
       0      .1       0   363.1     .07       0     468    .025       0
   473.9    .035       0   706.4     .07       0   733.4      .1       0
   822.4     .07       0   863.1     .06       0   972.5     .07       0
   992.3     .06       0
#XS Ineff= 2 , 0
             458 2361.85     722          2364.8
Permanent Ineff=
       F       F
Bank Sta=473.9,706.4
XS Rating Curve= 0 ,0
Exp/Cntr(USF)=0,0
Exp/Cntr=0.5,0.3

Type RM Length L Ch R = 1 ,243087  ,534.1,485.3,424.9
XS GIS Cut Line= 2
     2276124.104      495669.881     2275453.355      496284.858
#Sta/Elev= 30
       0 2491.33    40.4 2463.65    70.2 2438.47   105.5 2412.53   118.4 2404.71
   164.7 2367.22   186.3 2353.28     217 2352.62   229.8 2356.79   257.1 2357.65
   316.5 2354.63   363.5 2355.16   387.3 2352.39   401.4 2349.97     509 2349.91
     548 2349.95   557.2 2352.59   571.3 2360.73     577 2362.07   614.5 2359.75
   645.7 2361.05   721.1 2359.91   738.4 2363.39   772.3 2363.79   786.2 2369.14
   797.8 2371.34   835.6 2386.64   857.3 2393.18     879 2396.81     910 2398.36
#Mann= 8 ,-1,0
       0      .1       0     310    .025       0   387.3    .035       0
   557.2     .05       0     610      .1       0     660     .05       0
     750      .1       0     800     .05       0
Bank Sta=387.3,557.2
XS Rating Curve= 0 ,0
Exp/Cntr=0.3,0.1

Type RM Length L Ch R = 1 ,242602  ,560.5,511.8,459.9
XS GIS Cut Line= 2
     2275517.794      495257.5352275261.99459109496225.931884668
#Sta/Elev= 30
       0 2657.66    24.5    2644   112.3 2584.62   169.3 2534.85   210.9 2507.02
   231.3 2489.15   260.3 2470.94   285.1  2461.1   297.5    2453   330.6 2418.67
   347.2 2394.76   355.4  2379.1   359.6  2368.2   367.8 2357.71   376.1 2351.38
   388.5  2349.2     397 2347.22   524.7 2347.26   531.2 2349.39     554 2356.62
   578.8 2351.79   609.8 2351.96   636.8 2353.17     674 2358.64   818.8 2357.54
   847.8 2358.89   876.7  2363.3   905.7 2362.55     973 2391.15  1001.6 2397.52
#Mann= 7 ,-1,0
       0      .1       0     340    .025       0   388.5    .035       0
   531.2    .025       0     550     .08       0     750     .05       0
     850      .1       0
Bank Sta=388.5,531.2
XS Rating Curve= 0 ,0
Exp/Cntr=0.3,0.1

Type RM Length L Ch R = 1 ,242090  ,523,502.9,484.1
XS GIS Cut Line= 2
     2274772.253      495293.3872275041.66574967496226.308521627
#Sta/Elev= 30
       0 2557.91    25.6 2537.17    37.3 2530.76    61.1 2512.59    95.5 2491.59
   135.5 2470.98   145.1 2466.22   187.1 2451.38     208 2440.54   262.1 2424.86
   282.9 2416.86     312 2402.55   341.2 2381.33   353.7 2368.65     362 2356.56
     368 2351.34   374.5 2347.96   378.7 2346.25   511.9 2346.28   526.7 2347.93
   553.5 2353.49   628.5 2351.62   695.1 2355.24   803.3 2356.13     820 2357.71
     845 2361.18   869.9 2360.32   924.1 2378.41   949.5 2389.89     971 2397.64
#Mann= 5 ,-1,0
       0      .1       0   374.5    .035       0   526.7      .1       0
     610     .05       0     820      .1       0
Bank Sta=374.5,526.7
XS Rating Curve= 0 ,0
Exp/Cntr=0.3,0.1

Type RM Length L Ch R = 1 ,241587  ,499.8,500,502.1
XS GIS Cut Line= 2
     2274232.431      495536.293     2274652.172      496343.707
#Sta/Elev= 30
       0 2586.09    95.7 2540.27   131.7 2528.46   175.5 2509.72   196.2 2491.71
   217.4 2476.02   230.9 2461.36   240.7  2446.4   250.9  2437.1   271.5 2415.16
   298.5 2392.35   325.6 2371.54   343.6 2360.78   357.1 2350.03   366.2 2347.32
   387.6 2344.91   531.4 2344.98   545.8 2347.17   555.5 2349.35   578.1  2348.8
   600.6  2352.2   699.8 2355.79   726.8  2358.8   749.4 2358.75   753.9 2359.75
   763.2 2367.25   783.5 2379.07   821.5 2397.37   875.5 2411.95     910 2418.72
#Mann= 5 ,-1,0
       0      .1       0   366.2    .035       0   545.8      .1       0
     710     .06       0     720      .1       0
Bank Sta=366.2,545.8
XS Rating Curve= 0 ,0
Exp/Cntr=0.3,0.1

Type RM Length L Ch R = 1 ,241087  ,525.9,500.9,477.3
XS GIS Cut Line= 2
     2273790.962      495763.523     2274204.514      496574.124
#Sta/Elev= 30
       0 2577.05    55.7 2545.65    78.2 2530.91   109.2  2513.3   135.9 2494.64
   216.2 2442.86   269.7 2413.13   280.3 2405.01   289.3 2396.43   302.7 2380.71
   316.2 2368.13   323.3 2359.65   340.2 2348.04   356.6 2343.03   558.2 2342.94
   567.7 2343.08   578.6 2347.75   585.6 2351.55   599.1 2353.53   639.5 2354.57
   666.5 2353.91   684.4 2356.34   711.4 2355.39   720.3 2356.45   733.6 2365.01
   751.5 2373.97   778.7  2389.9   796.7 2402.38     830 2423.06     910 2470.83
#Mann= 3 ,0,0
       0      .1       0   340.2    .035       0   578.6      .1       0
Bank Sta=340.2,578.6
XS Rating Curve= 0 ,0
Exp/Cntr=0.3,0.1

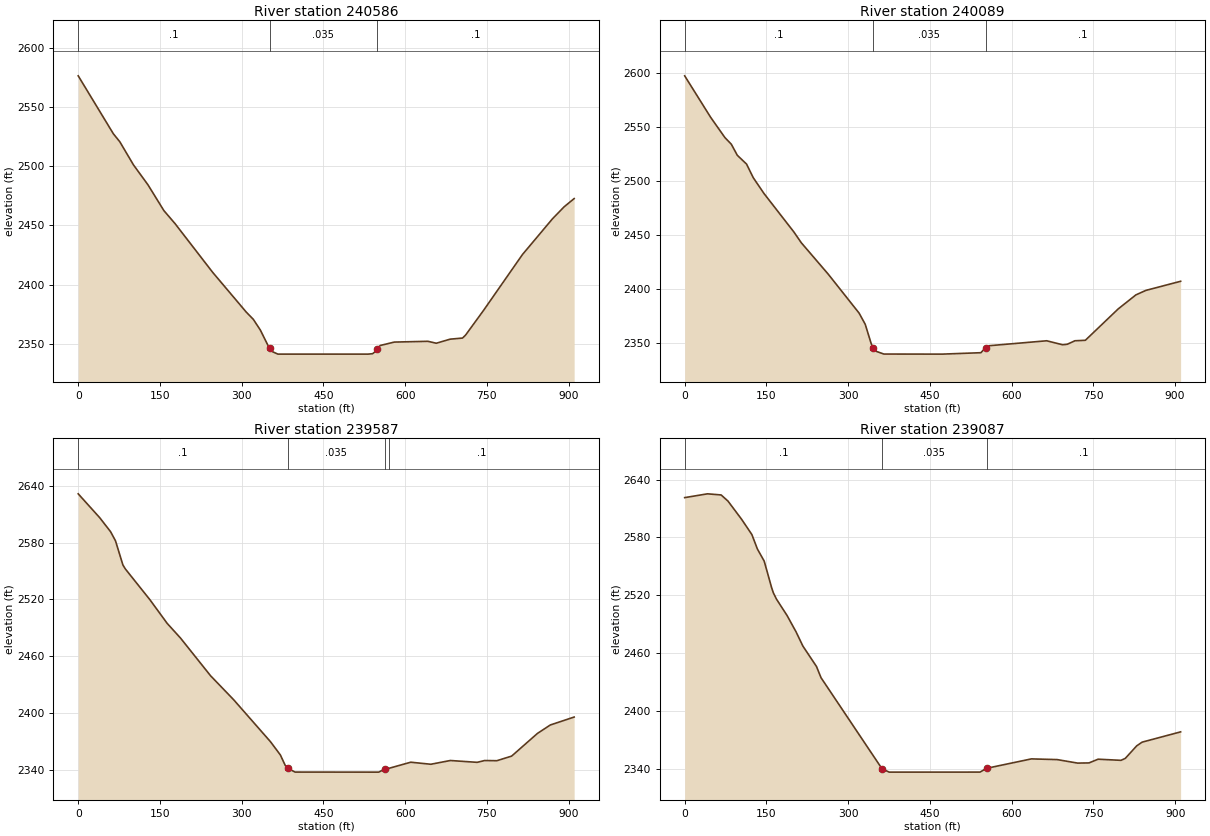
Type RM Length L Ch R = 1 ,240586  ,516.7,497.3,479.2
XS GIS Cut Line= 2
     2273284.855      496065.897     2273849.428      496779.592
#Sta/Elev= 30
       0  2576.3    64.5 2527.35    76.3 2520.63   101.5 2501.01   127.9 2484.31
   157.2 2462.48   177.6 2451.52   246.7 2410.33   308.4 2376.71   321.3 2370.63
   334.2 2361.58     351    2346   356.1  2343.4   366.3 2341.25   531.5 2341.24
   540.1  2341.6   544.8 2343.26   548.6 2345.96   554.3 2348.55   579.9 2351.41
   641.7 2352.07     657 2350.44   682.5 2353.88   705.2 2354.81   710.9 2357.39
   743.7 2378.14   815.1 2425.33   870.4 2455.63   891.6 2465.66     910 2472.62
#Mann= 3 ,0,0
       0      .1       0     351    .035       0   548.6      .1       0
Bank Sta=351,548.6
XS Rating Curve= 0 ,0
Exp/Cntr=0.3,0.1

Type RM Length L Ch R = 1 ,240089  ,531.9,501.5,468.7
XS GIS Cut Line= 2
     2272849.416      496427.445     2273516.311      497047.198
#Sta/Elev= 30
       0 2597.45    47.5 2559.15    73.9 2540.23    85.7 2534.04    96.6 2523.86
   113.6 2515.69   125.9 2503.08   145.7 2488.38   200.3 2452.92   214.1 2442.81
   263.6  2413.7   320.2 2377.64   331.4 2367.35   342.3 2349.55   345.6  2345.6
   351.3  2342.3   365.5 2339.74   472.6 2339.66   543.8 2340.98   552.3 2345.64
   555.3 2347.29   664.5 2352.03   693.8 2348.33   702.3  2348.8   716.4 2352.03
   735.5 2352.47   795.8 2381.52   828.3 2394.53   846.6 2398.69   910.4 2407.13
#Mann= 3 ,0,0
       0      .1       0   345.6    .035       0   552.3      .1       0
Bank Sta=345.6,552.3
XS Rating Curve= 0 ,0
Exp/Cntr=0.3,0.1

Type RM Length L Ch R = 1 ,239587  ,521.1,500.3,475.7
XS GIS Cut Line= 2
     2272487.555      496932.522     2273293.808      497354.559
#Sta/Elev= 30
       0 2631.37    39.5 2606.18    59.4 2591.44    68.4 2581.84      82 2556.35
    86.5 2552.14   131.6 2519.67   163.2 2494.78   187.7 2479.26   242.9 2439.49
   285.4 2414.13   352.9 2369.89   370.9 2356.03   379.9 2344.95   384.5 2341.83
     398 2337.94   533.5 2337.88   551.5 2337.88   562.1 2341.03   570.7 2341.99
   610.2 2348.34     647 2346.18   682.8 2350.13   732.1 2348.21   745.7 2350.11
   768.2 2349.92   795.3 2354.78   842.6 2378.67   866.3 2387.62     910 2395.96
#Mann= 4 ,-1,0
       0      .1       0   384.5    .035       0   562.1    .025       0
   570.7      .1       0
Bank Sta=384.5,562.1
XS Rating Curve= 0 ,0
Exp/Cntr=0.3,0.1

Type RM Length L Ch R = 1 ,239087  ,509.3,498.6,486.2
XS GIS Cut Line= 2
     2272259.987      497476.499     2273133.574      497731.342
#Sta/Elev= 30
       0 2621.33    41.9 2625.27    66.9  2624.1    79.4 2617.78   104.4 2598.87
   123.3 2582.97   133.5 2567.89   145.9 2555.41   159.5 2527.93   162.7 2522.46
   168.4 2515.94   187.8 2498.99   204.4  2481.9   216.9 2467.17   241.9 2445.91
   250.2 2434.31     362  2339.8   375.2 2336.25   541.9 2336.28   554.4 2340.27
   636.2 2349.99   683.5 2349.27     721 2345.63   741.9 2345.82   758.5 2349.66
   800.7  2348.5   808.5 2350.55   829.4 2363.51   839.4 2367.39     910 2378.06
#Mann= 3 ,0,0
       0      .1       0     362    .035       0   554.4      .1       0
Bank Sta=362,554.4
XS Rating Curve= 0 ,0
Exp/Cntr=0.3,0.1