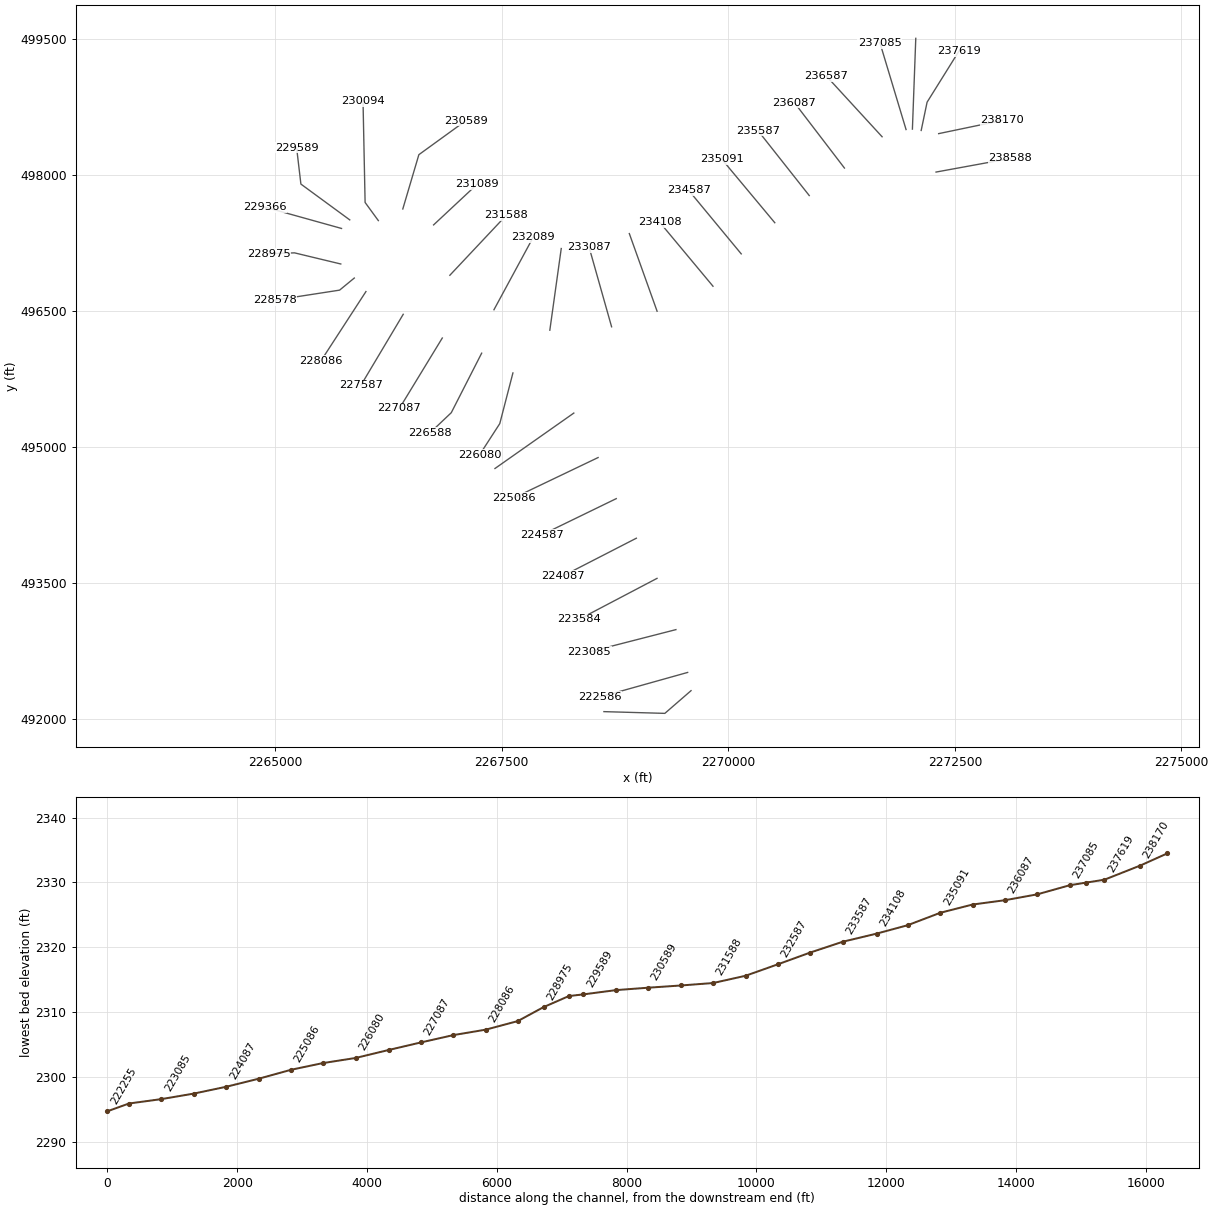
HEC-RAS study GRNBRRRV.prj: GRNBRRRV

--- GRNBRRRV.g01 (geometry) --- (continued)

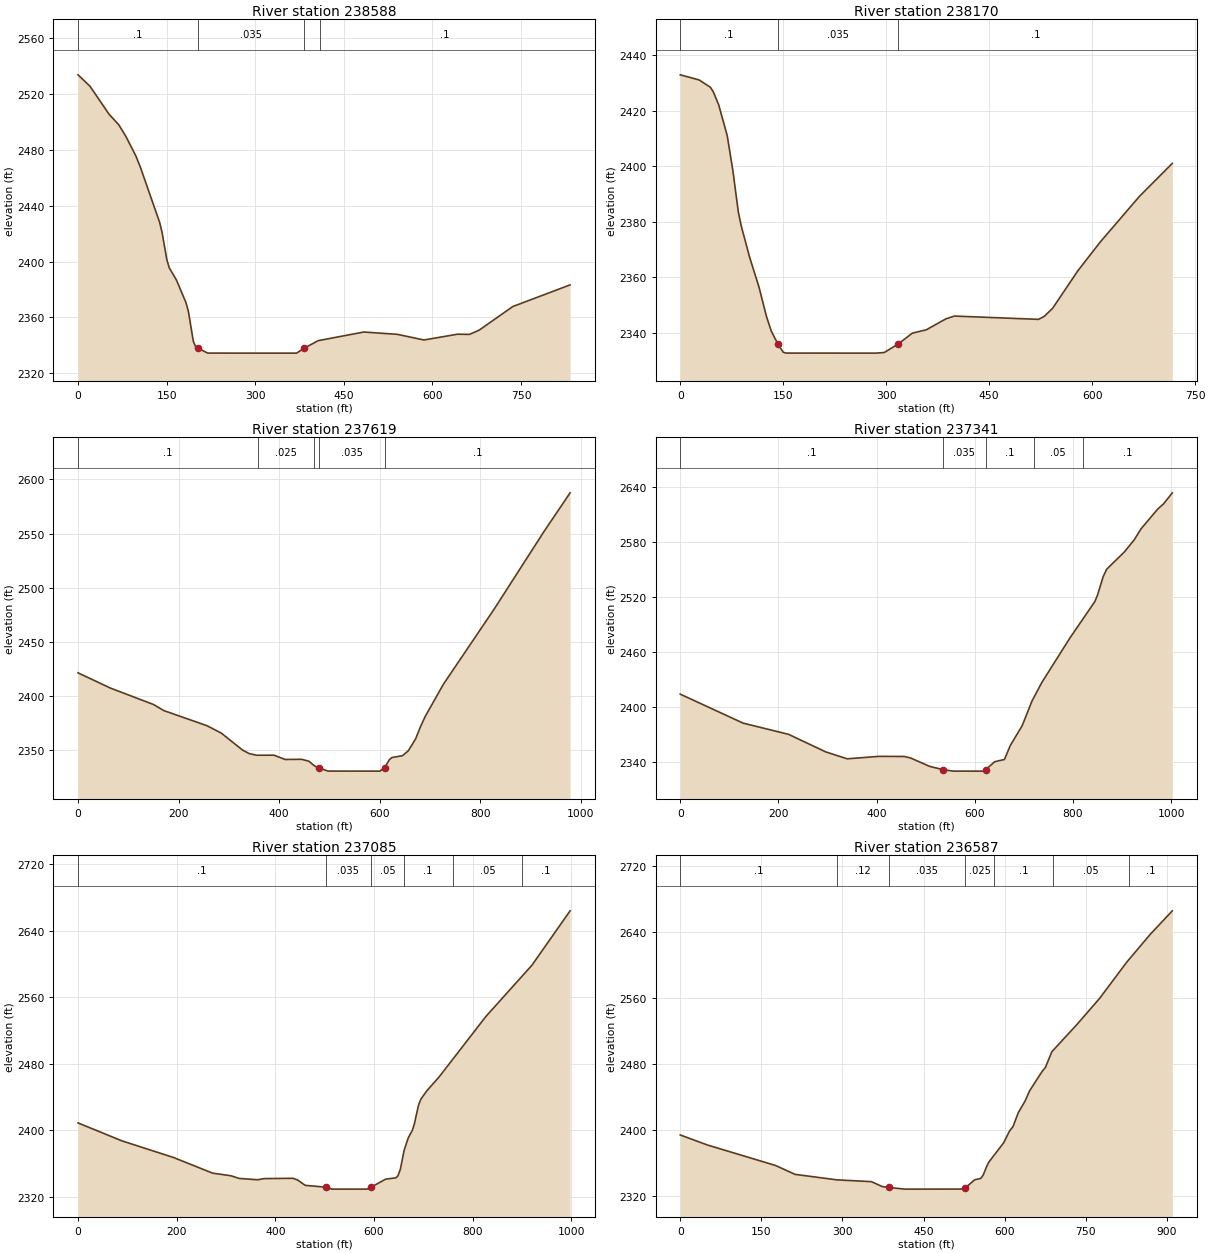
Type RM Length L Ch R = 1 ,238588  ,417.5,418.1,422.2
XS GIS Cut Line= 2
2272292.30425192498034.9741682592273111.58289278498184.938667396
#Sta/Elev= 30
       0  2533.8    20.2 2525.68    52.7  2505.5      69 2498.02    81.2 2489.57
      98 2475.61   105.6 2467.61   138.1 2428.21   142.2 2421.09   150.3 2401.53
   154.4 2395.63   166.6 2386.83   182.9 2370.46   186.9 2364.16   195.1 2343.09
   199.1 2338.94   203.2 2337.99   219.5  2334.5   300.7 2334.47   369.9 2334.47
   383.3 2338.12   406.5 2343.39   483.8 2349.59   540.7 2347.92   585.4 2343.88
   642.4 2348.03   662.7 2347.89     679 2350.94   735.9 2367.83   832.9 2383.35
#Mann= 4 ,-1,0
       0      .1       0   203.2    .035       0   383.3    .025       0
     410      .1       0
Bank Sta=203.2,383.3
XS Rating Curve= 0 ,0
Exp/Cntr=0.3,0.1

Type RM Length L Ch R = 1 ,238170  ,482.8,551.2,629.9
XS GIS Cut Line= 2
2272321.22182215498459.0985315662273022.94472308498605.335276917
#Sta/Elev= 30
       0 2432.98    27.5 2431.14    43.9  2428.5      48 2426.95    56.1 2422.11
    68.4  2411.1    76.6 2398.56    84.7 2383.42    88.8 2378.55   101.1 2367.17
   114.7 2356.46   125.6 2345.83   132.7  2340.5   141.9 2336.04   150.1  2332.9
   154.2 2332.61   284.7 2332.59   297.2 2332.81   317.6 2335.89   338.1  2339.8
   358.5 2341.01   387.1 2344.97   399.4 2345.96   521.9 2344.77   530.1 2345.82
   542.4 2348.74   579.1 2362.26   611.8 2372.66     669 2389.16   716.8 2401.04
#Mann= 3 ,0,0
       0      .1       0   141.9    .035       0   317.6      .1       0
Bank Sta=141.9,317.6
XS Rating Curve= 0 ,0
Exp/Cntr=0.3,0.1

Type RM Length L Ch R = 1 ,237619  ,242.4,277.6,318.4
XS GIS Cut Line= 3
2272128.34206601498494.0362272932272193.50255365498806.109374272
     2272542.708      499365.907
#Sta/Elev= 30
       0 2421.25    64.5 2407.16   150.3 2391.95   170.7 2386.35   256.6 2372.37
   285.2 2365.48   327.1 2349.91   340.4 2346.61   355.4 2345.09   389.7 2345.14
     412 2341.19   444.8 2341.33   459.1 2339.57     471 2335.01   479.8 2333.33
   496.9 2330.48   552.3 2330.41   600.6 2330.41     610 2333.75   619.1 2340.96
   624.1 2342.95   645.2 2344.67   656.9 2349.27   671.4  2360.2   680.7  2371.1
   690.1  2380.6   726.5  2410.6   828.2 2480.58   925.9 2551.28   978.6 2587.63
#Mann= 5 ,-1,0
       0      .1       0   358.8    .025       0   468.8      .1       0
   479.8    .035       0     610      .1       0
Bank Sta=479.8,610
XS Rating Curve= 0 ,0
Exp/Cntr=0.3,0.1

Type RM Length L Ch R = 1 ,237341  ,237,256.2,278.8
XS GIS Cut Line= 2
2272031.51729773498509.1527477612272068.68636221499510.761222052
#Sta/Elev= 30
       0 2414.05   128.1 2382.38   220.7 2370.14   296.2 2351.01   340.2 2343.41
   404.3 2346.09   456.1 2345.98   469.1 2344.35   508.4 2335.09   535.6 2331.57
   556.4 2329.97   616.5 2329.97     622  2331.4   640.5 2340.26   660.5  2342.7
   672.2 2357.88   696.5 2379.58   716.5 2406.54   736.5 2426.72   793.3 2474.98
   844.6 2515.18   849.8 2521.93   861.3 2542.07   868.6 2550.43   904.6 2569.29
   924.7 2582.54   938.8 2594.65   972.7 2616.19   984.6 2621.88  1002.3 2633.85
#Mann= 5 ,-1,0
       0      .1       0   535.6    .035       0     622      .1       0
     720     .05       0     820      .1       0
Bank Sta=535.6,622
XS Rating Curve= 0 ,0
Exp/Cntr(USF)=0,0
Exp/Cntr=0.3,0.1

Type RM Length L Ch R = 1 ,237085  ,464.3,498.3,531.8
XS GIS Cut Line= 2
2271961.37190075498504.210632256     2271673.617      499459.446
#Sta/Elev= 30
       0 2409.07    88.7  2387.6   193.2 2367.62   272.6 2348.81   310.2 2345.58
   326.9 2342.41   364.3 2340.82   377.4 2342.19   435.5 2342.58   444.8 2340.69
   460.5 2334.13   501.9 2331.91   514.9 2329.58   585.9 2329.56   594.2 2331.88
   623.5  2341.5   644.4 2343.14   648.5 2345.41   653.5 2353.41   661.1 2376.09
   669.4 2390.98   677.8 2400.23     682 2408.23   690.3 2430.39   695.2 2437.71
     707 2447.53   732.1 2464.32   826.8 2536.81   920.4 2598.55   997.6 2663.75
#Mann= 6 ,-1,0
       0      .1       0   501.9    .035       0   594.2     .05       0
     660      .1       0     760     .05       0     900      .1       0
Bank Sta=501.9,594.2
XS Rating Curve= 0 ,0
Exp/Cntr=0.3,0.1

Type RM Length L Ch R = 1 ,236587  ,507.9,500,491.4
XS GIS Cut Line= 2
     2271696.907      498424.602     2271081.509      499094.964
#Sta/Elev= 30
       0 2393.96    49.7  2381.9   176.4 2356.83   212.5 2346.07   289.7 2339.43
   353.7 2337.22   373.7 2331.25   385.5 2330.23   415.1 2328.16     519 2328.22
   527.5 2329.97   544.5 2339.46   555.8 2341.22   560.1 2345.04   567.1  2356.3
   570.9 2361.16   598.1 2384.46   608.9 2398.66   615.3 2403.96   625.2 2421.03
   637.9 2435.32   645.8 2447.24     669 2470.87   675.4 2476.02   687.2 2494.98
   734.2 2528.53   775.9  2560.1   826.1 2604.12     870 2638.19     910 2666.15
#Mann= 7 ,-1,0
       0      .1       0     290     .12       0   385.5    .035       0
   527.5    .025       0     580      .1       0     690     .05       0
     830      .1       0
Bank Sta=385.5,527.5
XS Rating Curve= 0 ,0
Exp/Cntr=0.3,0.1

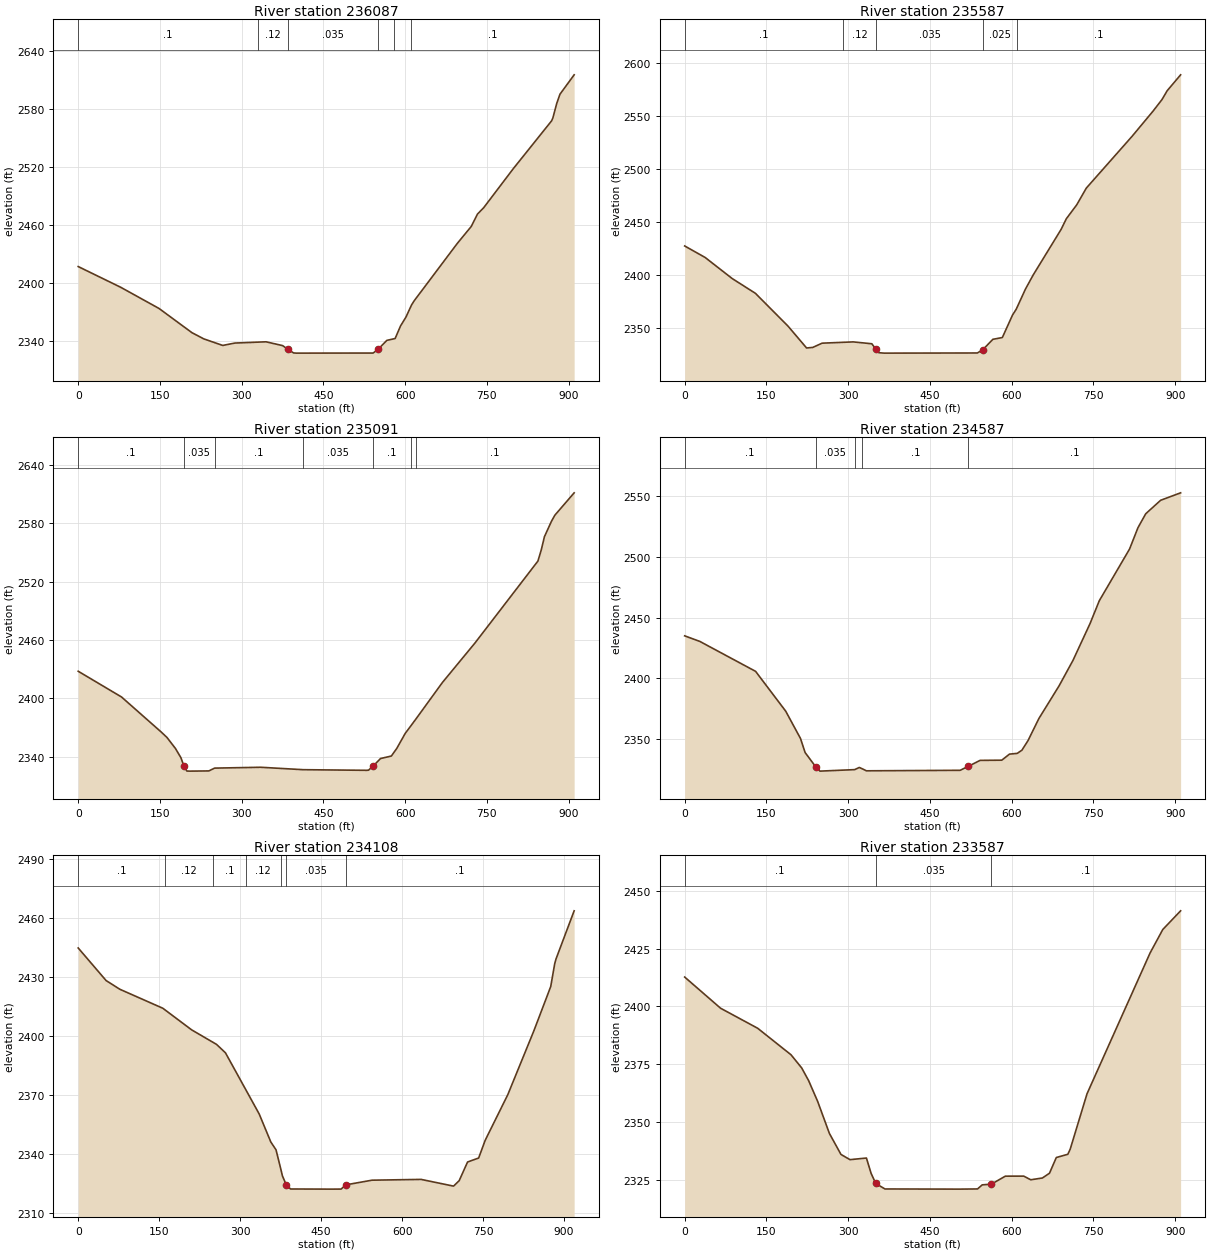
Type RM Length L Ch R = 1 ,236087  ,499.7,500,501.8
XS GIS Cut Line= 2
      2271281.35      498079.392     2270728.372      498802.105
#Sta/Elev= 30
       0 2416.84    77.8 2395.45   148.3 2373.47   208.7 2348.41   230.4    2342
   265.2 2335.21   287.4 2337.67   344.7 2338.96     375 2335.04   384.5 2331.31
   395.1 2327.45   400.1 2327.25   541.2 2327.34     550 2331.05   566.3 2340.44
   581.5 2342.36   591.5 2355.46   601.3 2364.46   611.7 2377.17   616.7 2381.59
   695.5 2440.73   721.2 2458.34   732.6 2471.13     744 2477.73   798.4 2518.19
   868.5 2567.53   870.8 2570.31   878.1 2585.78     884 2595.21     910 2615.25
#Mann= 6 ,-1,0
       0      .1       0     330     .12       0   384.5    .035       0
     550     .05       0     580    .025       0     610      .1       0
Bank Sta=384.5,550
XS Rating Curve= 0 ,0
Exp/Cntr=0.3,0.1

Type RM Length L Ch R = 1 ,235587  ,514.7,496.4,499.2
XS GIS Cut Line= 2
     2270893.004      497775.743     2270328.939      498489.838
#Sta/Elev= 30
       0 2427.65    37.5 2416.82      87 2396.99   129.8 2382.98   189.6 2352.06
   223.7 2331.43   235.1 2331.98   252.2 2335.97   309.2 2337.18   343.4 2335.41
  351.33 2330.01   356.3 2326.98   366.1 2326.58   537.1 2326.72   547.2 2329.89
   565.5 2339.61   582.9 2341.29   601.5 2362.41   608.4 2368.05   625.3 2386.97
   639.5 2400.31   690.8 2443.35   700.2 2453.25   719.3  2466.4     737 2482.25
   820.9 2531.04   859.6 2554.95   875.9  2565.8   885.4  2574.1     910 2589.06
#Mann= 5 ,-1,0
       0      .1       0     290     .12       0  351.33    .035       0
   547.2    .025       0     610      .1       0
Bank Sta=351.33,547.2
XS Rating Curve= 0 ,0
Exp/Cntr=0.3,0.1

Type RM Length L Ch R = 1 ,235091  ,504.1,503.6,504.7
XS GIS Cut Line= 2
     2270512.579       497476.01     2269929.552      498175.148
#Sta/Elev= 30
       0    2428    79.6 2401.51   152.6  2365.4     163 2359.88   178.6 2348.51
   188.6 2339.02   194.2 2330.24   199.4 2325.41   204.6 2325.31   239.7 2325.52
   250.5 2328.41   334.9 2329.28   412.8 2326.79   529.4 2326.14   532.8 2326.28
   540.7 2330.13   554.9 2338.25   574.8 2340.84   584.9 2348.82   600.2 2364.08
   610.9 2372.11   620.2 2379.16   668.5 2416.45   728.2 2457.02   843.8 2541.31
     850 2552.88   855.7 2566.28   868.8 2582.39     875 2588.54   910.3 2611.48
#Mann= 7 ,-1,0
       0      .1       0   194.2    .035       0   250.5      .1       0
   412.8    .035       0   540.7      .1       0   610.9    .025       0
   620.2      .1       0
Bank Sta=194.2,540.7
XS Rating Curve= 0 ,0
Exp/Cntr=0.3,0.1

Type RM Length L Ch R = 1 ,234587  ,474.1,479,483.7
XS GIS Cut Line= 2
     2270142.343       497132.17     2269562.338      497833.379
#Sta/Elev= 30
       0 2434.91    27.8 2430.32   130.1 2405.65   185.4 2372.81   212.5 2350.31
     221 2338.71   240.1 2327.15   248.2 2323.39   311.9 2324.63   320.5 2326.42
   326.1 2325.26   333.5 2323.65   505.5 2324.07   520.4 2327.35   542.1 2332.25
   581.8 2332.41     596 2337.41   610.2 2338.02   618.8 2340.65   630.1 2348.65
     650  2366.8     687  2393.7   712.6 2414.77   743.8 2445.02   760.8 2463.86
   816.3 2506.47   831.8 2524.13     846 2535.56   873.4 2546.68     910 2552.81
#Mann= 5 ,-1,0
       0      .1       0   240.1    .035       0   311.9      .1       0
   326.1      .1       0   520.4      .1       0
Bank Sta=240.1,520.4
XS Rating Curve= 0 ,0
Exp/Cntr=0.3,0.1

Type RM Length L Ch R = 1 ,234108  ,553.3,521,501.6
XS GIS Cut Line= 2
     2269830.721      496775.085     2269242.724      497480.777
#Sta/Elev= 30
       0 2444.84    51.6 2428.28    77.1 2423.83   156.7 2414.17   210.2 2403.15
   256.1 2395.79   272.7  2391.5   335.2 2360.36   356.8 2346.06   366.4  2342.1
   375.3 2332.25   378.2 2328.88   385.1 2324.42   393.2 2322.16   466.2 2322.09
   486.9 2322.11     496 2324.28   544.2 2326.64   635.1 2327.04   695.2 2323.62
   705.6 2326.38   721.2  2335.9   741.7 2337.92   753.8 2346.93   795.7 2370.17
     844 2402.68   875.2  2425.2   882.6 2436.85     885 2439.25   918.6 2463.76
#Mann= 7 ,-1,0
       0      .1       0     160     .12       0     250      .1       0
     310     .12       0   375.3      .1       0   385.1    .035       0
     496      .1       0
Bank Sta=385.1,496
XS Rating Curve= 0 ,0
Exp/Cntr=0.3,0.1

Type RM Length L Ch R = 1 ,233587  ,507.8,500,490.5
XS GIS Cut Line= 2
     2269213.883      496499.125     2268907.427      497355.971
#Sta/Elev= 30
       0 2412.72    65.9 2399.21   133.9 2390.54   195.1 2379.05   214.6 2373.38
   227.3 2367.92   243.9 2358.91   265.6 2344.94   286.8 2335.87   303.3 2333.61
   333.5 2334.31     342 2327.72   350.5 2323.31   367.5 2320.91   503.5 2320.84
   537.4 2320.92   545.9 2322.68   562.9 2323.01   588.4 2326.46   622.2 2326.47
     635 2324.89   656.4 2325.66   669.4 2327.73   681.9 2334.53   703.1 2335.94
   707.4 2338.16   738.3 2362.17     854 2423.16   877.3 2433.32     910 2441.41
#Mann= 3 ,0,0
       0      .1       0   350.5    .035       0   562.9      .1       0
Bank Sta=350.5,562.9
XS Rating Curve= 0 ,0
Exp/Cntr=0.3,0.1

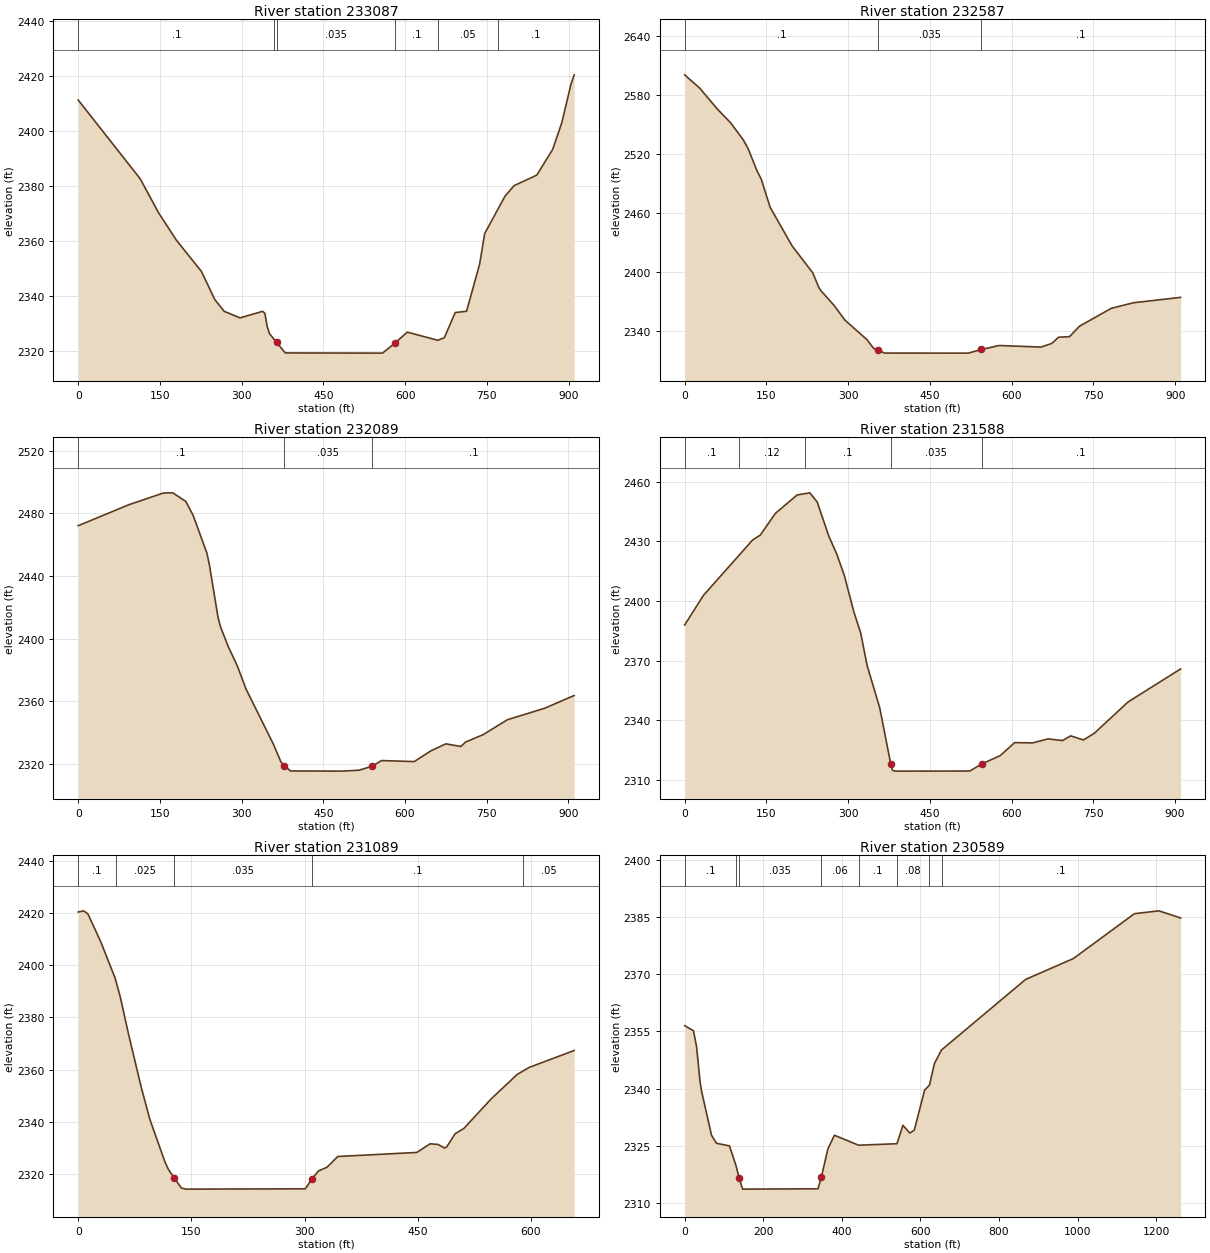
Type RM Length L Ch R = 1 ,233087  ,546.9,500,446.4
XS GIS Cut Line= 2
     2268711.695      496327.466     2268464.186       497203.16
#Sta/Elev= 30
       0 2411.33     114 2382.58   147.3 2370.32   180.5  2360.2   226.2 2348.91
   250.5 2338.72   267.8 2334.41   296.9 2332.01   338.5 2334.41   342.6 2333.61
   346.8 2328.86   350.9 2326.32     364 2323.06     380 2319.25   558.4 2319.18
   581.1 2322.82   603.8 2326.83     660 2323.85   671.8  2324.8   691.8 2333.95
   712.6 2334.42   736.6 2351.61   745.8 2362.69   783.2 2376.34   799.9 2380.17
   841.4 2383.98   870.5 2393.31   887.2 2402.98   903.8 2416.78     910  2420.5
#Mann= 6 ,-1,0
       0      .1       0     360    .025       0     364    .035       0
   581.1      .1       0     660     .05       0     770      .1       0
Bank Sta=364,581.1
XS Rating Curve= 0 ,0
Exp/Cntr=0.3,0.1

Type RM Length L Ch R = 1 ,232587  ,537.8,497.6,458.3
XS GIS Cut Line= 2
     2268030.147      496289.853     2268156.074      497191.098
#Sta/Elev= 30
       0 2600.24    27.6  2586.7    59.9  2565.5    84.1 2551.61   107.5 2534.19
   116.4 2525.26   132.3 2503.24   140.7 2493.87   156.8 2465.61   197.2 2426.27
   235.1  2398.9   245.7 2384.63   249.7 2381.02   274.1  2365.9   294.2 2350.82
   334.3 2331.18   346.7 2322.22   354.7 2320.51   366.9 2317.41   520.3 2317.36
   544.6 2321.09   576.9  2325.1   654.1 2323.52   673.8 2327.26   685.9 2333.49
   706.1 2334.09   724.5 2344.75   782.9 2362.91   823.3 2368.55     910 2374.03
#Mann= 3 ,0,0
       0      .1       0   354.7    .035       0   544.6      .1       0
Bank Sta=354.7,544.6
XS Rating Curve= 0 ,0
Exp/Cntr=0.3,0.1

Type RM Length L Ch R = 1 ,232089  ,526.2,501.4,473.6
XS GIS Cut Line= 2
     2267413.541      496515.514     2267847.003      497316.313
#Sta/Elev= 30
       0 2472.06    92.9 2485.43   156.5 2492.92   173.6 2493.03   197.5 2487.57
   211.1 2478.59   236.3 2454.63   240.8 2447.24   256.6  2413.9   261.2 2407.69
   275.2 2395.24   292.4 2382.48     308 2368.04   358.5 2332.69   372.1 2321.56
     378 2319.13   389.8 2315.71     484 2315.59   515.9 2316.18   540.3 2318.81
   556.8 2322.33     617 2321.67   647.8 2328.59   675.1 2332.99   702.6  2331.3
   711.4 2334.16   743.3 2338.81   788.1 2348.36     857 2355.76   910.6 2363.81
#Mann= 3 ,0,0
       0      .1       0     378    .035       0   540.3      .1       0
Bank Sta=378,540.3
XS Rating Curve= 0 ,0
Exp/Cntr=0.3,0.1

Type RM Length L Ch R = 1 ,231588  ,505.5,499.3,492.4
XS GIS Cut Line= 2
     2266926.821      496896.013     2267550.453      497559.055
#Sta/Elev= 30
       0 2387.97    34.5 2402.86   124.6 2430.66   138.9 2433.18   166.3 2444.03
   206.3  2453.3   229.7  2454.4   243.2 2449.79   264.9 2432.37   279.1 2423.65
   293.2 2412.68   310.2 2394.81   323.1 2383.87   334.8 2367.61   358.1 2346.18
   378.1 2318.23   381.5 2314.88     386 2314.47   523.3 2314.51   545.1 2318.06
   579.1 2322.27   605.6 2328.81   638.6 2328.66   666.8 2330.68   693.5 2329.83
   708.4 2332.21   731.8 2330.15   751.7 2333.48   813.9 2349.28   910.2 2365.85
#Mann= 5 ,-1,0
       0      .1       0     100     .12       0     220      .1       0
   378.1    .035       0   545.1      .1       0
Bank Sta=378.1,545.1
XS Rating Curve= 0 ,0
Exp/Cntr=0.3,0.1

Type RM Length L Ch R = 1 ,231089  ,445.2,499.2,568.8
XS GIS Cut Line= 2
2266747.36016118497451.803168711     2267227.711      497900.331
#Sta/Elev= 30
       0 2420.46     7.2 2420.92    12.9 2419.71    29.9 2409.01    48.9 2395.09
    55.8 2387.83    66.6 2373.68    83.2 2353.55    94.9 2340.92   114.8 2324.65
   119.2 2321.83     127 2318.45   136.8  2314.5   142.7 2314.09   300.9 2314.21
     310 2318.11   318.5 2321.09   329.5 2322.46     344 2326.62   448.7 2328.17
   466.3 2331.49   476.8 2331.24   485.5 2329.85   488.5 2330.38   499.6 2335.39
     511 2337.37   547.1  2348.7   581.7 2358.11   597.6 2360.81   657.2  2367.3
#Mann= 5 ,-1,0
       0      .1       0      50    .025       0     127    .035       0
     310      .1       0     590     .05       0
Bank Sta=127,310
XS Rating Curve= 0 ,0
Exp/Cntr=0.3,0.1

Type RM Length L Ch R = 1 ,230589  ,460.8,494.2,532
XS GIS Cut Line= 3
2266407.57871103497627.7183875832266584.75527864498226.764975921
2267100.99899174  498600.6760206
#Sta/Elev= 30
       0 2356.52    22.4  2355.2    30.3 2351.02    39.1 2341.86    43.2  2339.3
    68.3 2327.85    80.8 2325.75   114.1 2325.06   130.8 2319.83   138.52316.643
   147.5 2313.75   339.4 2313.84   348.12317.024   364.4 2324.26   381.1 2327.85
   442.7 2325.24   540.3 2325.63   555.4 2330.45     573 2328.42   584.3 2329.17
   610.5 2339.63     623 2340.98     623 2340.99   635.6 2346.62   653.6 2350.16
   867.5 2368.61   989.5  2374.1  1144.5 2385.82  1206.8 2386.57  1262.1  2384.7
#Mann= 8 ,-1,0
       0      .1       0   130.8    .025       0   138.5    .035       0
   348.1     .06       0   442.7      .1       0   540.3     .08       0
     623     .06       0   653.6      .1       0
Bank Sta=138.5,348.1
XS Rating Curve= 0 ,0
Exp/Cntr=0.3,0.1

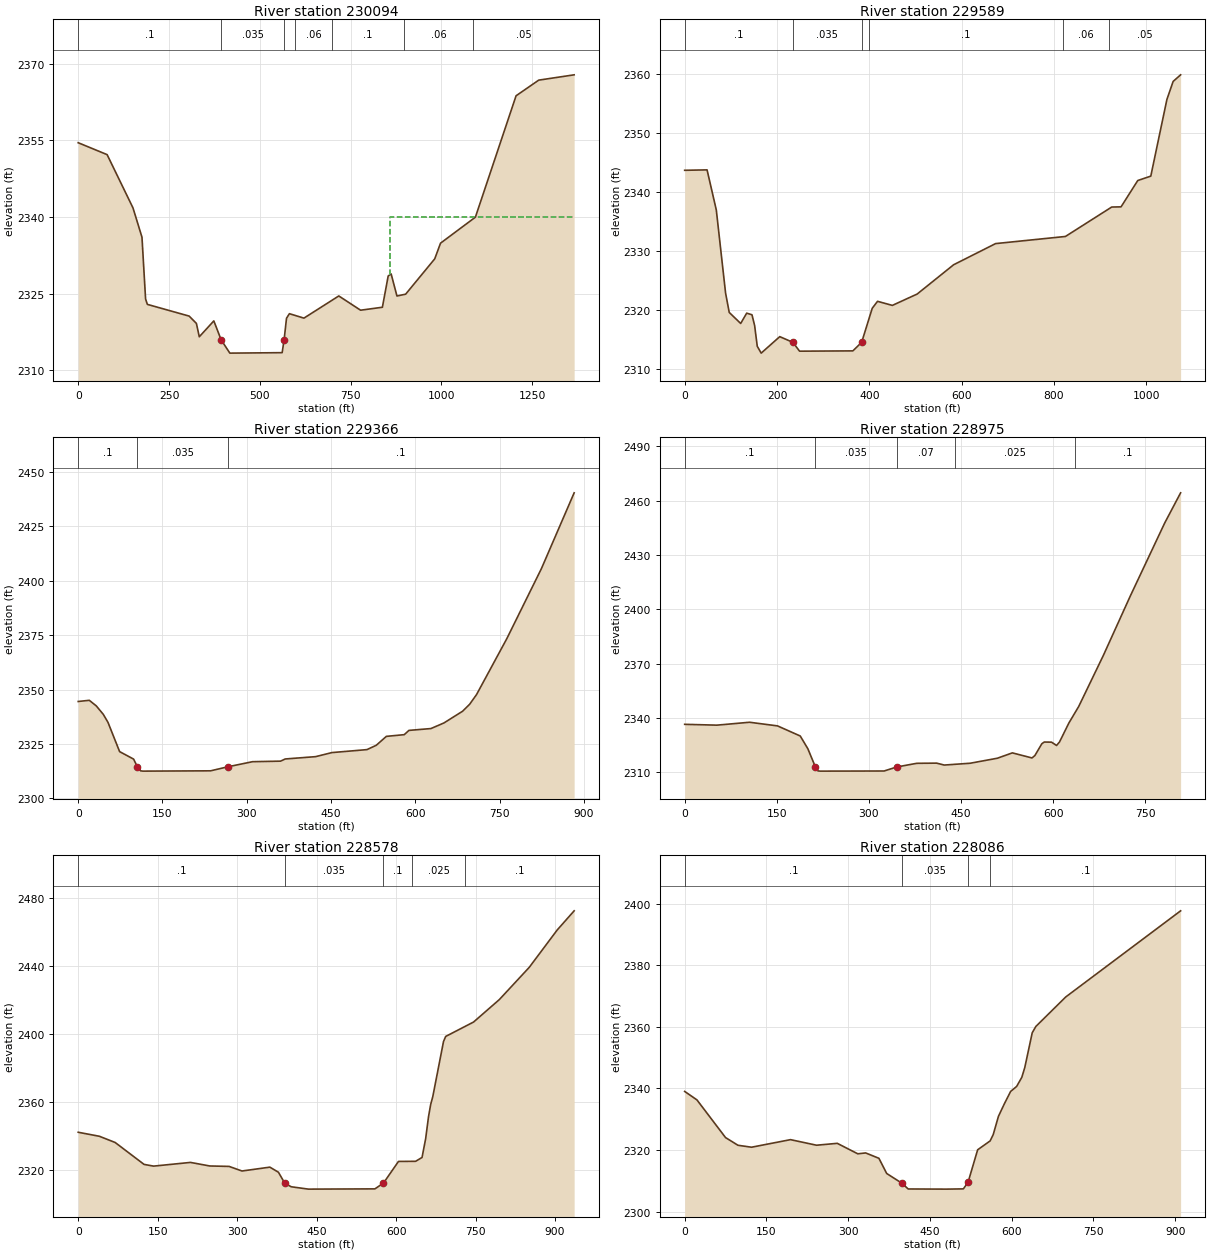
Type RM Length L Ch R = 1 ,230094  ,415.7,505.1,599.3
XS GIS Cut Line= 3
2266137.49158263497499.3385454132265991.49398759497699.538438196
2265968.54712915498817.058588549
#Sta/Elev= 30
       0 2354.56    79.6 2352.23   150.8 2341.81   175.6 2336.06   185.5 2323.97
   190.4 2322.92   305.4 2320.63   325.4  2319.2   333.4 2316.58   373.4 2319.69
  393.56 2315.98   417.5 2313.38   561.5 2313.47  566.96 2316.01   573.5  2320.2
   581.5  2321.1   621.5 2320.23   717.5 2324.57   777.5 2321.78   837.5 2322.36
   853.5 2328.48   861.6 2328.89   877.6 2324.56   901.6 2324.92   981.6 2331.83
   997.6  2334.9  1093.6 2339.99  1205.6 2363.75    1268 2366.81  1365.5 2367.85
#Mann= 7 ,-1,0
       0      .1       0  393.56    .035       0  566.96      .1       0
  597.78     .06       0  697.78      .1       0  897.78     .06       0
 1087.78     .05       0
#XS Ineff= 2 , 0
                          858.14            2340
Permanent Ineff=
       F       F
Bank Sta=393.56,566.96
XS Rating Curve= 0 ,0
Exp/Cntr=0.3,0.1

Type RM Length L Ch R = 1 ,229589  ,198,223.4,261.5
XS GIS Cut Line= 3
2265821.99791397497507.2285116432265282.94610767497902.380371729
2265235.38193797498305.294136014
#Sta/Elev= 30
       0 2343.67    48.5 2343.74    68.5 2336.95    88.6 2322.88    96.5 2319.61
   121.3 2317.74   134.3 2319.49   145.8 2319.21   151.5 2317.39   157.2 2313.88
   165.7 2312.72   205.9 2315.51   234.5 2314.54   248.8 2313.05   364.3  2313.1
   383.3 2314.55   406.2 2320.31   417.7 2321.49   449.8  2320.8   503.5 2322.72
   582.5 2327.68   673.4 2331.26   824.7 2332.47   924.9 2337.45   945.1 2337.48
   981.3 2341.94  1009.5 2342.68  1044.4 2355.66  1057.9 2358.71  1074.1 2359.83
#Mann= 6 ,-1,0
       0      .1       0   234.5    .035       0   383.3    .025       0
     400      .1       0  818.37     .06       0  918.37     .05       0
Bank Sta=234.5,383.3
XS Rating Curve= 0 ,0
Exp/Cntr=0.3,0.1

Type RM Length L Ch R = 1 ,229366  ,387.9,391.1,394.3
XS GIS Cut Line= 2
2265731.19150241497412.6342288742264880.93578987497649.590738925
#Sta/Elev= 30
       0 2344.49    19.7 2345.03    32.2 2342.45    44.7 2338.56      53 2334.88
    73.7 2321.43    98.6 2317.99  105.34 2314.41   111.1 2312.59   115.2 2312.46
   235.7  2312.6   265.9 2314.43   310.4  2316.8   360.1 2317.05   368.5 2318.05
   422.5 2319.12   451.6 2320.99   513.9 2322.35   530.5 2324.35   548.5 2328.45
   580.3 2329.23   588.6 2331.19   627.8 2332.04   650.9 2334.61   684.1    2340
   696.6 2343.18     709 2347.68   762.8 2373.36   824.5 2405.63   882.7 2440.46
#Mann= 3 ,0,0
       0      .1       0  105.34    .035       0   265.9      .1       0
Bank Sta=105.34,265.9
XS Rating Curve= 0 ,0
Exp/Cntr(USF)=0,0
Exp/Cntr=0.3,0.1

Type RM Length L Ch R = 1 ,228975  ,361.6,396.3,438.7
XS GIS Cut Line= 3
 2265723.1962157497020.4494128472265212.31914171497143.349086306
2264930.37283201 497133.70989623
#Sta/Elev= 30
       0 2336.58    52.5 2336.12   105.7 2337.72   151.2 2335.71   188.2 2330.13
   200.6  2323.1   212.9 2313.01     217 2310.87   221.2 2310.75   324.8 2310.82
   345.2 2313.03   377.9 2315.06   410.4 2315.16   422.7  2314.1   464.9  2315.1
   509.1 2317.86   533.6 2320.82   565.6 2318.02   570.3 2319.36   581.6 2325.86
   585.6 2326.81   597.4 2326.73   605.6 2324.91   610.4 2326.85   625.7 2337.34
   641.7 2346.45   681.7 2374.54   725.7 2407.41   781.7 2447.69   807.6 2464.33
#Mann= 5 ,-1,0
       0      .1       0   212.9    .035       0   345.2     .07       0
     440    .025       0  635.45      .1       0
Bank Sta=212.9,345.2
XS Rating Curve= 0 ,0
Exp/Cntr(USF)=0,0
Exp/Cntr=0.3,0.1

Type RM Length L Ch R = 1 ,228578  ,402.1,492,576.8
XS GIS Cut Line= 3
2265872.20863226496865.4481652632265709.87591714496731.917165263
     2264992.485      496621.035
#Sta/Elev= 30
       0 2342.11      40 2339.74    69.7 2336.09   124.3 2323.17   142.3 2322.16
   211.9 2324.34   248.3 2322.24   284.8 2321.99   309.1 2319.28   361.7 2321.55
   377.9 2318.57     390 2312.04   402.1 2309.99   434.5  2308.6     560 2308.75
   576.2 2312.16   604.5 2324.92   636.9 2324.99     649 2327.27   655.8  2338.3
   661.2 2351.23   665.2 2358.36   669.3 2363.16   689.5 2395.56   693.6 2398.57
   746.2 2407.05   794.8 2420.26   851.4  2439.3     904 2461.26   936.1 2472.59
#Mann= 5 ,-1,0
       0      .1       0     390    .035       0   576.2      .1       0
   630.2    .025       0   730.2      .1       0
Bank Sta=390,576.2
XS Rating Curve= 0 ,0
Exp/Cntr=0.3,0.1

Type RM Length L Ch R = 1 ,228086  ,497.3,499.4,503.1
BEGIN DESCRIPTION:
2' drawdown in the 100 yr could only be fixed with c/e of 0.5/0.7
END DESCRIPTION:
XS GIS Cut Line= 2
     2266000.611      496716.076     2265505.106      495952.758
#Sta/Elev= 30
       0 2339.03    22.5 2336.28      75 2324.03    97.8 2321.53   122.7  2320.9
   194.2 2323.36   241.9 2321.55     280 2322.16   317.6 2318.76   332.1 2319.04
   356.4  2317.3   370.7 2312.36   398.6  2309.2   410.1 2307.33   480.3 2307.28
   511.4 2307.36     520 2309.53   537.6 2320.07   560.5 2322.95   566.2 2325.03
   575.7 2330.92   586.5 2334.98   598.1 2339.03   609.1 2340.65   618.6 2343.61
   624.1 2346.82   637.7 2358.09   644.4 2360.15   699.3 2369.74     910 2397.72
#Mann= 4 ,-1,0
       0      .1       0   398.6    .035       0     520    .025       0
   560.5      .1       0
Bank Sta=398.6,520
XS Rating Curve= 0 ,0
Exp/Cntr=0.7,0.5

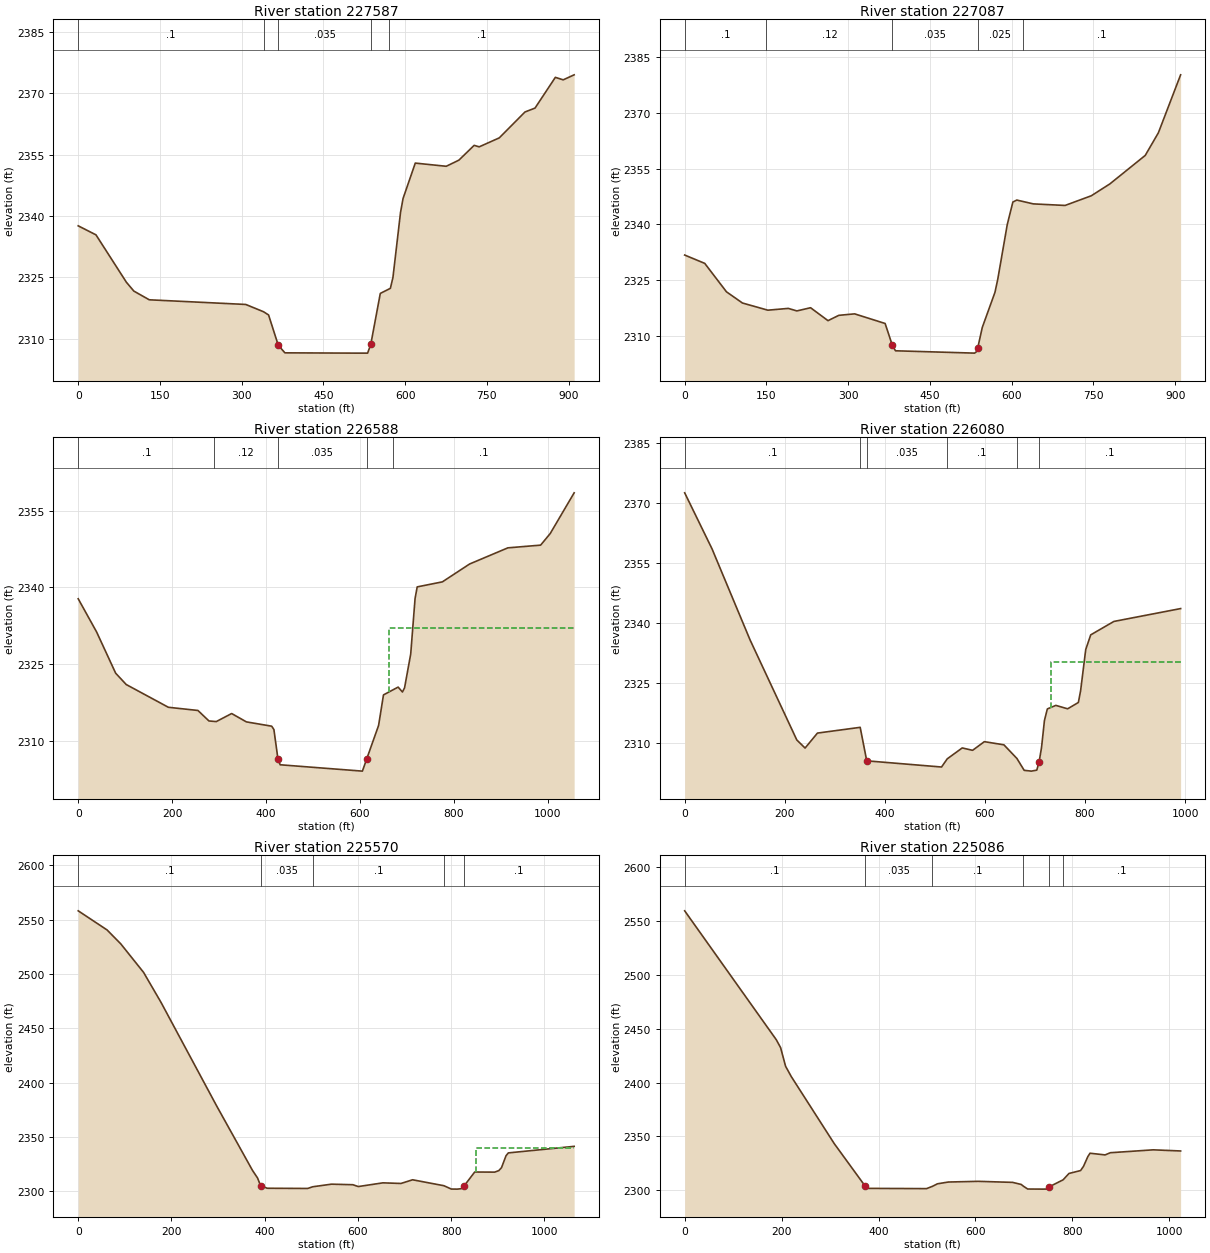
Type RM Length L Ch R = 1 ,227587  ,501.2,500,499
XS GIS Cut Line= 2
     2266412.159      496465.199     2265946.207      495683.542
#Sta/Elev= 30
       0 2337.59    32.6 2335.38    88.5 2323.77   102.1 2321.62   130.4 2319.49
   307.4 2318.35     340 2316.57   349.3 2315.78   367.1 2308.36   379.3 2306.51
   507.4 2306.44     531 2306.44   536.8 2308.56   554.3 2321.05   570.2 2322.12
   572.8 2322.31   577.5 2324.94   591.4 2340.85   596.1  2344.3   618.5 2352.94
   675.3 2352.16   698.5 2353.66   726.5 2357.28   735.8 2356.92   772.6 2359.11
   819.8 2365.45   838.2  2366.4   875.5 2373.92   889.9 2373.31     910 2374.54
#Mann= 5 ,-1,0
       0      .1       0     340    .025       0   367.1    .035       0
   536.8    .025       0   570.2      .1       0
Bank Sta=367.1,536.8
XS Rating Curve= 0 ,0
Exp/Cntr=0.3,0.1

Type RM Length L Ch R = 1 ,227087  ,490.4,498.5,506
XS GIS Cut Line= 2
     2266843.303      496203.498     2266369.888      495426.338
#Sta/Elev= 30
       0 2331.71    36.8 2329.47    76.7 2321.81     106  2318.8   152.6 2316.87
   190.1 2317.35   205.9 2316.67     231 2317.53     263 2314.05   282.8 2315.48
   311.8 2315.88   367.8 2313.29   381.1 2307.38   386.8 2305.94     532 2305.31
   536.7 2305.84  537.842306.754     546 2312.19   569.4  2321.7   574.5 2325.21
   591.9 2339.91   602.2 2345.98   609.4 2346.51   639.7 2345.48     698 2345.06
   746.2 2347.67   780.2 2350.86   845.1 2358.53   869.2 2364.62     910 2380.22
#Mann= 5 ,-1,0
       0      .1       0     150     .12       0   381.1    .035       0
  537.84    .025       0     620      .1       0
Bank Sta=381.1,537.84
XS Rating Curve= 0 ,0
Exp/Cntr=0.3,0.1

Type RM Length L Ch R = 1 ,226588  ,482.5,508.4,530.8
XS GIS Cut Line= 3
2267277.81236774496036.2799255642266942.55376021 495379.37730255
 2266711.2131984 495160.08572834
#Sta/Elev= 30
       0 2337.78    39.2  2331.3    79.8 2323.25   102.3 2321.04   192.1  2316.6
     255 2315.98   278.5 2313.93     294 2313.81   326.8 2315.38   358.3 2313.75
   412.1 2312.91   416.8 2312.26   425.3  2306.6   430.1 2305.38   605.3 2304.14
   614.2 2306.45   639.8 2313.06   650.2 2319.02   681.4 2320.54   690.6 2319.58
   695.1  2320.4   708.2    2327   717.5 2337.85     722  2340.1   775.6 2341.08
   833.7 2344.57   915.1 2347.72   984.9 2348.25  1005.3 2350.51  1056.3 2358.46
#Mann= 5 ,-1,0
       0      .1       0     290     .12       0   425.3    .035       0
   614.2    .025       0     670      .1       0
#XS Ineff= 2 , 0
                          661.86         2332.11
Permanent Ineff=
       F       F
Bank Sta=425.3,614.2
XS Rating Curve= 0 ,0
Exp/Cntr=0.3,0.1

Type RM Length L Ch R = 1 ,226080  ,577.1,510.3,326.7
XS GIS Cut Line= 3
     2267622.761      495818.0562267477.74202481 495258.92812406
 2267253.1997315494911.862429775
#Sta/Elev= 30
       0 2372.63    54.6 2358.61   130.8 2335.74   224.1 2310.71   240.6 2308.69
   265.3 2312.44   350.7 2313.88   363.8 2305.49   513.3 2303.94   524.6 2305.98
   554.6 2308.72   575.3 2308.12   598.8 2310.29   637.9  2309.5   663.9 2306.08
   678.4 2303.11   692.8 2302.91   703.6 2303.16   708.3 2305.28   713.1 2308.85
   718.9  2315.6   724.7 2318.49   741.7 2319.38   765.2 2318.52   786.7 2320.11
   791.2 2323.08   801.4 2333.38   811.4 2337.05   857.7 2340.41     991 2343.63
#Mann= 6 ,-1,0
       0      .1       0   350.7    .025       0   363.8    .035       0
   524.6      .1       0   663.9    .035       0   708.3      .1       0
#XS Ineff= 2 , 0
                          731.27         2330.15
Permanent Ineff=
       F       F
Bank Sta=363.8,708.3
XS Rating Curve= 0 ,0
Exp/Cntr=0.3,0.1

Type RM Length L Ch R = 1 ,225570  ,499.2,484.2,428.2
XS GIS Cut Line= 2
     2268294.775      495375.2712267424.71977307494763.572143603
#Sta/Elev= 30
       0 2558.03    61.9 2540.44    91.2 2527.69   140.1 2501.48   177.5 2473.92
   296.2 2379.18   373.7 2319.39   384.6 2312.38     391 2305.42   405.3 2302.91
   492.1 2302.72   502.9 2304.27   543.1 2306.67   589.1 2306.16   600.6 2304.46
   653.5 2307.89   692.2 2307.31   717.1  2310.7   784.3 2305.25   800.2 2302.18
     813 2302.11   821.6 2302.53   827.4 2304.94   850.3 2317.85   893.1 2317.74
     902 2319.13   907.8 2321.84   917.5  2332.8   922.4 2335.42  1063.6 2341.45
#Mann= 5 ,-1,0
       0      .1       0     391    .035       0   502.9      .1       0
   784.3    .035       0   827.4      .1       0
#XS Ineff= 2 , 0
                          853.18         2340.33
Permanent Ineff=
       F       F
Bank Sta=391,827.4
XS Rating Curve= 0 ,0
Exp/Cntr=0.3,0.1

Type RM Length L Ch R = 1 ,225086  ,497.9,498.6,500.3
XS GIS Cut Line= 2
     2268562.666      494884.3112267639.48235343494442.589444197
#Sta/Elev= 30
       0 2559.33     189 2439.75   197.9 2432.44   208.2 2415.14     220 2405.52
   308.7 2343.28   372.8 2303.67   379.7 2301.78   499.1 2301.56   511.1 2303.64
   521.6 2306.03   544.1 2307.68   605.8 2308.32   676.8 2307.35   694.5 2305.42
   698.9 2303.84   707.8 2301.19     739 2301.09   747.7 2301.15   752.2 2303.24
   780.9 2309.72     793 2315.62     817 2318.32     823 2322.24     832 2331.31
   836.4  2334.4   867.5 2332.84   878.4 2334.87     967 2337.55  1023.4 2336.49
#Mann= 6 ,-1,0
       0      .1       0   372.8    .035       0   511.1      .1       0
   698.9    .035       0   752.2     .06       0   780.9      .1       0
Bank Sta=372.8,752.2
XS Rating Curve= 0 ,0
Exp/Cntr=0.3,0.1

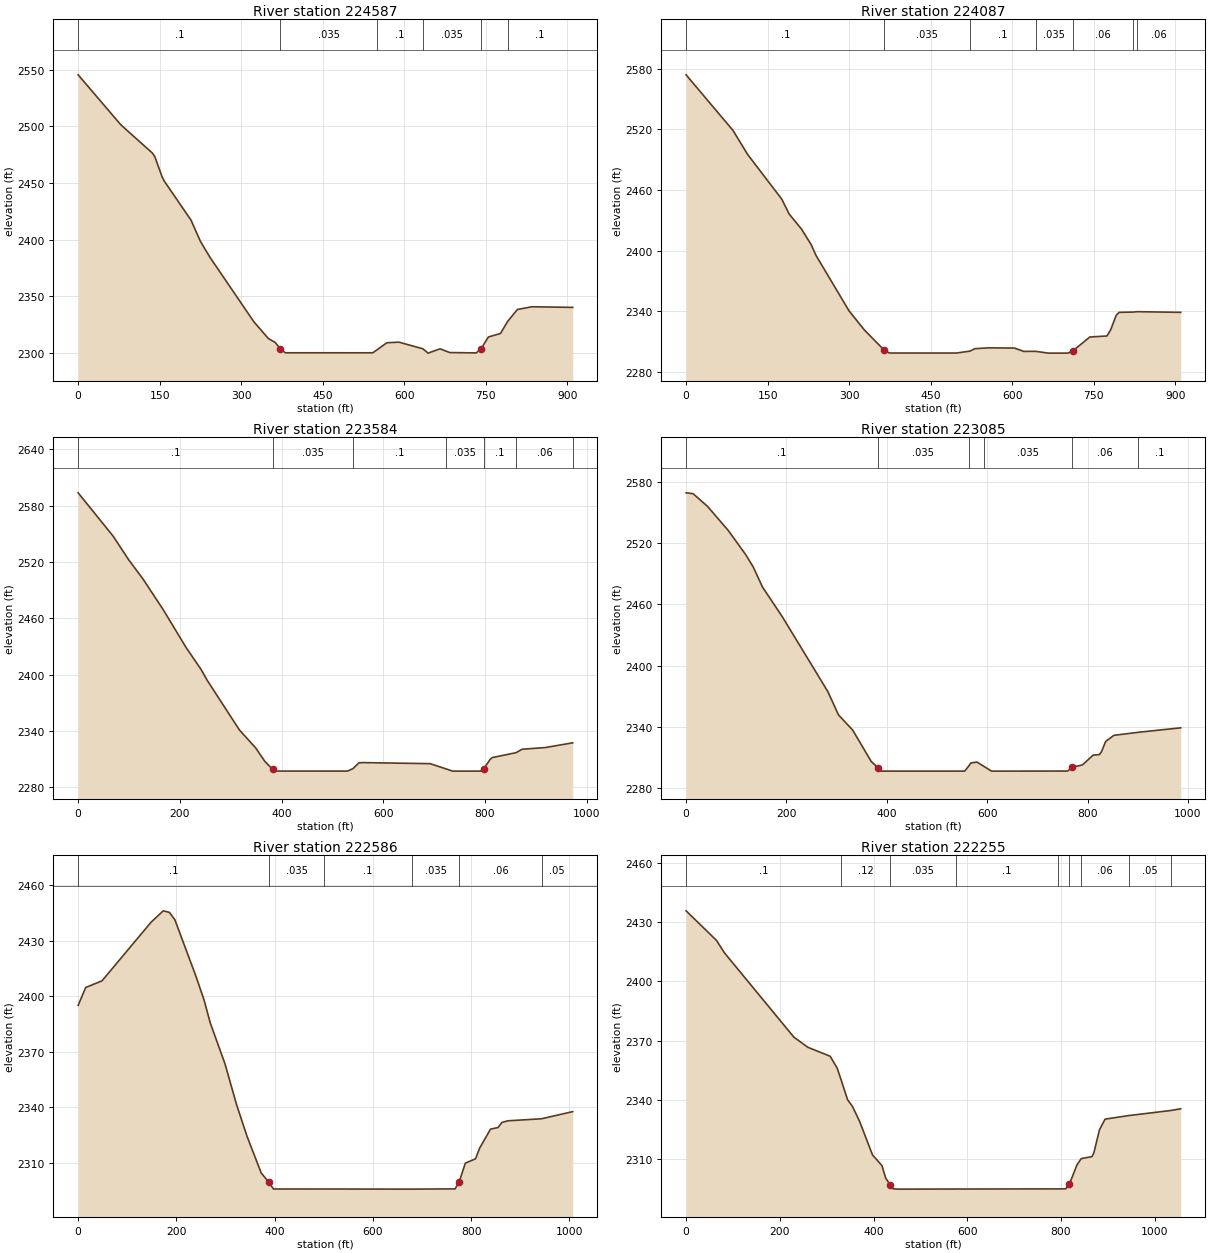
Type RM Length L Ch R = 1 ,224587  ,497.7,500,507.5
XS GIS Cut Line= 2
     2268763.046      494430.907     2267944.625      494033.053
#Sta/Elev= 30
       0 2545.54    78.8 2501.26   136.6 2476.45   141.1 2473.26   154.4  2455.5
   158.9 2451.39   207.8 2417.09   224.9 2398.54   241.8 2384.88   323.4 2327.36
   350.1 2312.55   362.6 2309.16   372.3 2303.31   381.2 2300.02   542.1 2300.01
   550.2 2302.71     568 2308.88   590.3 2309.39   634.3 2303.54   643.9 2299.71
   665.9 2303.54   683.7 2300.22   732.6 2299.91   741.5 2303.72   754.8 2313.96
   777.1 2317.07   790.1 2327.62   808.2 2338.26   834.9 2340.67     910 2340.12
#Mann= 6 ,-1,0
       0      .1       0   372.3    .035       0   550.2      .1       0
   634.3    .035       0   741.5     .06       0   790.1      .1       0
Bank Sta=372.3,741.5
XS Rating Curve= 0 ,0
Exp/Cntr=0.3,0.1

Type RM Length L Ch R = 1 ,224087  ,502.1,502.6,513.3
XS GIS Cut Line= 2
     2268984.854      493994.166     2268175.459      493578.258
#Sta/Elev= 30
       0 2573.84    86.2 2518.88   113.2 2495.08   176.2 2450.71   189.6 2436.15
   212.2 2421.31     230 2405.94   239.1 2395.08   299.7  2340.4     328 2321.38
     365 2301.16     374 2298.58   497.3 2298.56   522.4 2300.48   531.4 2302.88
   556.8 2303.71   604.3 2303.48   621.4 2300.15   642.9 2300.26   666.3 2298.47
   702.3 2298.47   711.2 2300.52   742.8 2314.43   774.3 2315.42   781.1 2321.43
   791.4 2335.93   796.8 2338.84   822.6 2339.09   830.1 2339.47     910 2338.82
#Mann= 7 ,-1,0
       0      .1       0     365    .035       0   522.4      .1       0
   642.9    .035       0   711.2     .06       0   822.6     .05       0
   830.1     .06       0
Bank Sta=365,711.2
XS Rating Curve= 0 ,0
Exp/Cntr=0.3,0.1

Type RM Length L Ch R = 1 ,223584  ,520.2,498.9,417.3
XS GIS Cut Line= 2
     2269213.118      493550.9742268352.06245459493098.701834737
#Sta/Elev= 30
       0 2593.54    68.8 2547.46    99.8 2521.98   127.6 2501.81   167.3  2469.2
   212.3 2428.92     242 2405.39   253.8 2394.05   317.3  2341.1     349 2322.21
     367 2307.89   382.3 2299.39   385.1 2297.64   389.6 2297.47   529.7 2297.46
   540.4 2300.05   552.3 2306.31   561.3 2306.48   692.2 2305.35     724 2299.69
   736.7 2297.41   791.8 2297.44   797.4  2299.7   809.8 2309.63   814.3 2311.83
   861.1 2317.02   873.1 2320.69   918.3 2322.47   972.5 2327.54   972.6 2327.55
#Mann= 7 ,-1,0
       0      .1       0   382.3    .035       0   540.4      .1       0
     724    .035       0   797.4      .1       0   861.1     .06       0
   972.5     .05       0
Bank Sta=382.3,797.4
XS Rating Curve= 0 ,0
Exp/Cntr=0.3,0.1

Type RM Length L Ch R = 1 ,223085  ,497.7,499.7,507
XS GIS Cut Line= 2
     2269421.607      492985.3232268467.16907444492740.202822331
#Sta/Elev= 30
       0 2569.13    13.9 2568.32    42.8 2555.82    84.1  2532.2   118.5 2508.78
   133.6 2496.64   152.4 2476.71   191.9  2447.6   282.3 2374.57   303.6 2351.64
   331.9 2336.76     369 2305.92   382.5 2299.77   389.7 2296.56   554.9 2296.56
     563 2301.46   567.3 2304.55   579.6 2305.43   592.8 2301.38   608.6 2296.56
   760.3 2296.63   768.6 2300.18   789.9 2302.72   810.9 2312.22   823.3 2312.78
   827.4 2315.36   835.9 2325.62   852.3 2331.61   901.1  2334.6   985.4 2338.97
#Mann= 6 ,-1,0
       0      .1       0   382.5    .035       0     563      .1       0
   592.8    .035       0   768.6     .06       0   901.1      .1       0
Bank Sta=382.5,768.6
XS Rating Curve= 0 ,0
Exp/Cntr=0.3,0.1

Type RM Length L Ch R = 1 ,222586  ,359.4,330.9,231.8
XS GIS Cut Line= 2
     2269550.962      492512.9272268581.64569429492241.440632256
#Sta/Elev= 30
       0 2395.17    15.4 2404.83    48.6 2408.42   148.3 2440.05   173.2 2446.24
   185.7  2445.4   196.8 2441.47   239.7 2410.94   256.3 2398.06   268.7 2385.83
   298.7 2363.71   322.7 2341.31   343.5  2324.6   372.6 2304.59   388.2 2299.55
   397.5 2295.95   500.6 2295.94   662.2 2295.88   679.5 2295.88   767.2 2296.02
   775.5 2299.77     788 2309.91   808.8 2312.28   817.1 2318.01   839.3 2328.29
   854.4 2329.15   862.8 2331.96     875  2332.8   943.1 2333.89  1006.6 2337.75
#Mann= 6 ,-1,0
       0      .1       0   388.2    .035       0   500.6      .1       0
   679.5    .035       0   775.5     .06       0   943.1     .05       0
Bank Sta=388.2,775.5
XS Rating Curve= 0 ,0
Exp/Cntr=0.3,0.1

Type RM Length L Ch R = 1 ,222255  ,491.4,535.7,497.9
XS GIS Cut Line= 3
2269588.51143584492311.7050611282269299.33573358492061.086119174
2268627.00222584492080.364499324
#Sta/Elev= 30
       0 2435.79    64.9 2420.78    81.4 2414.62   229.8 2371.79   259.8  2366.6
   307.4 2362.06   322.5 2355.95     331 2349.89   344.5 2340.05   355.1 2336.58
   370.3    2329   397.8    2312   417.8 2306.65   425.8 2300.37  434.84    2297
   441.9 2294.87     452 2294.69   575.3 2294.73   793.7 2294.81     810 2294.84
   817.6 2297.06     834 2306.99   843.1 2310.15     866 2311.18     870 2313.06
     882 2324.76     894 2330.18   944.1 2331.97  1034.1 2334.55  1055.3 2335.44
#Mann= 9 ,-1,0
       0      .1       0     331     .12       0  434.84    .035       0
   575.3      .1       0   793.7    .035       0   817.6      .1       0
   843.1     .06       0   944.1     .05       0  1034.1      .1       0
Bank Sta=434.84,817.6
XS Rating Curve= 0 ,0
Exp/Cntr(USF)=0,0
Exp/Cntr=0.3,0.1