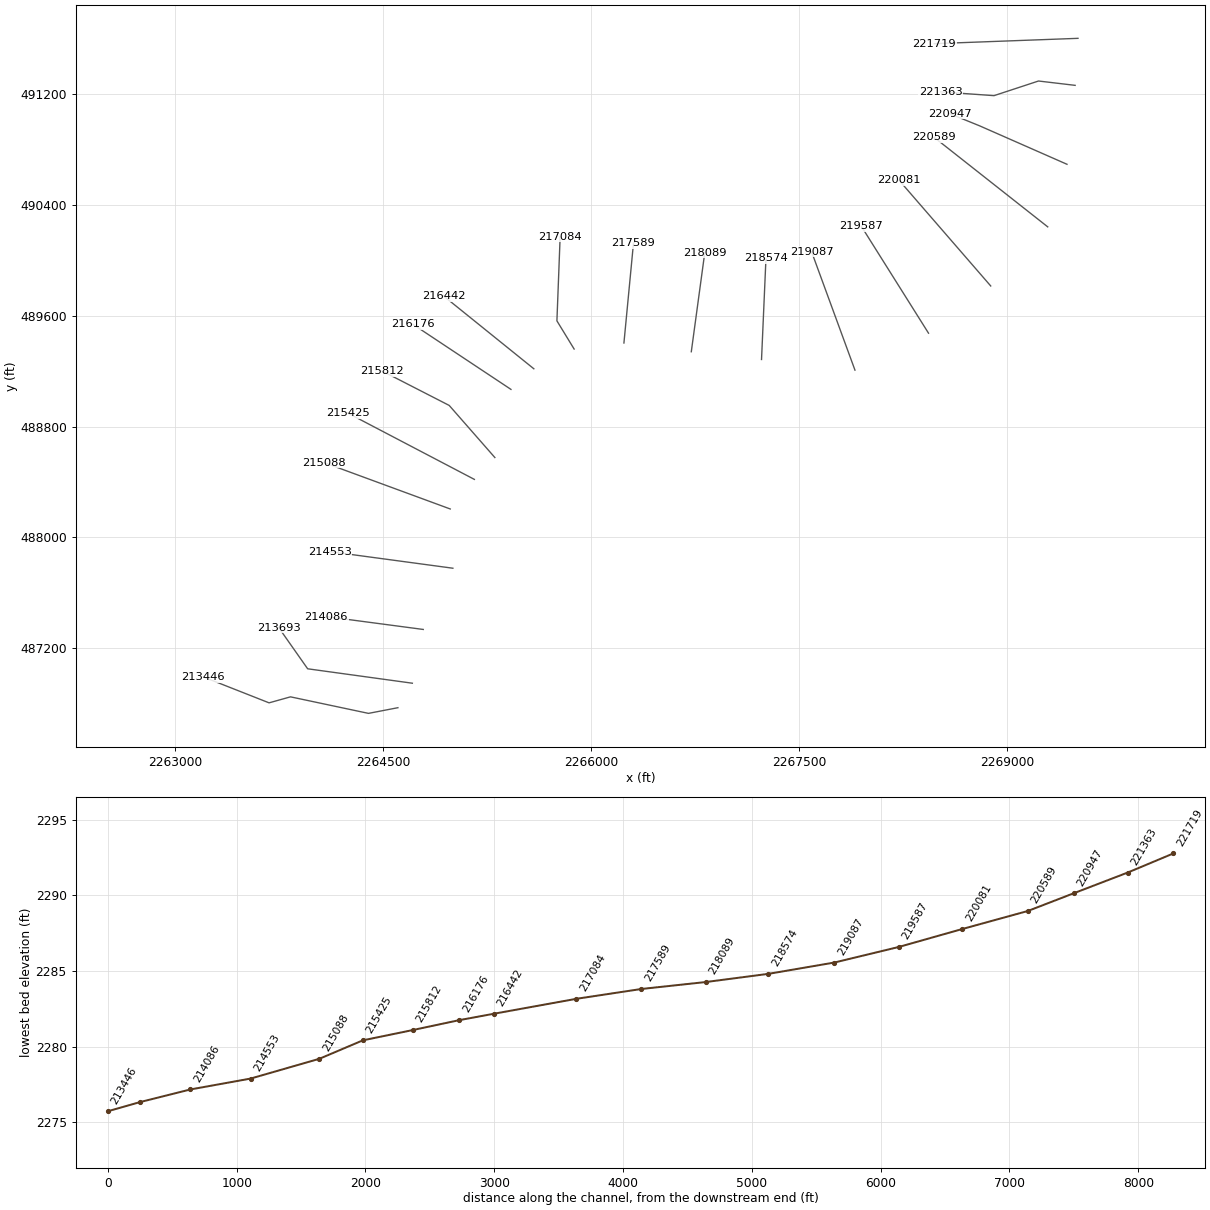
HEC-RAS study GRNBRRRV.prj: GRNBRRRV

--- GRNBRRRV.g01 (geometry) --- (continued)

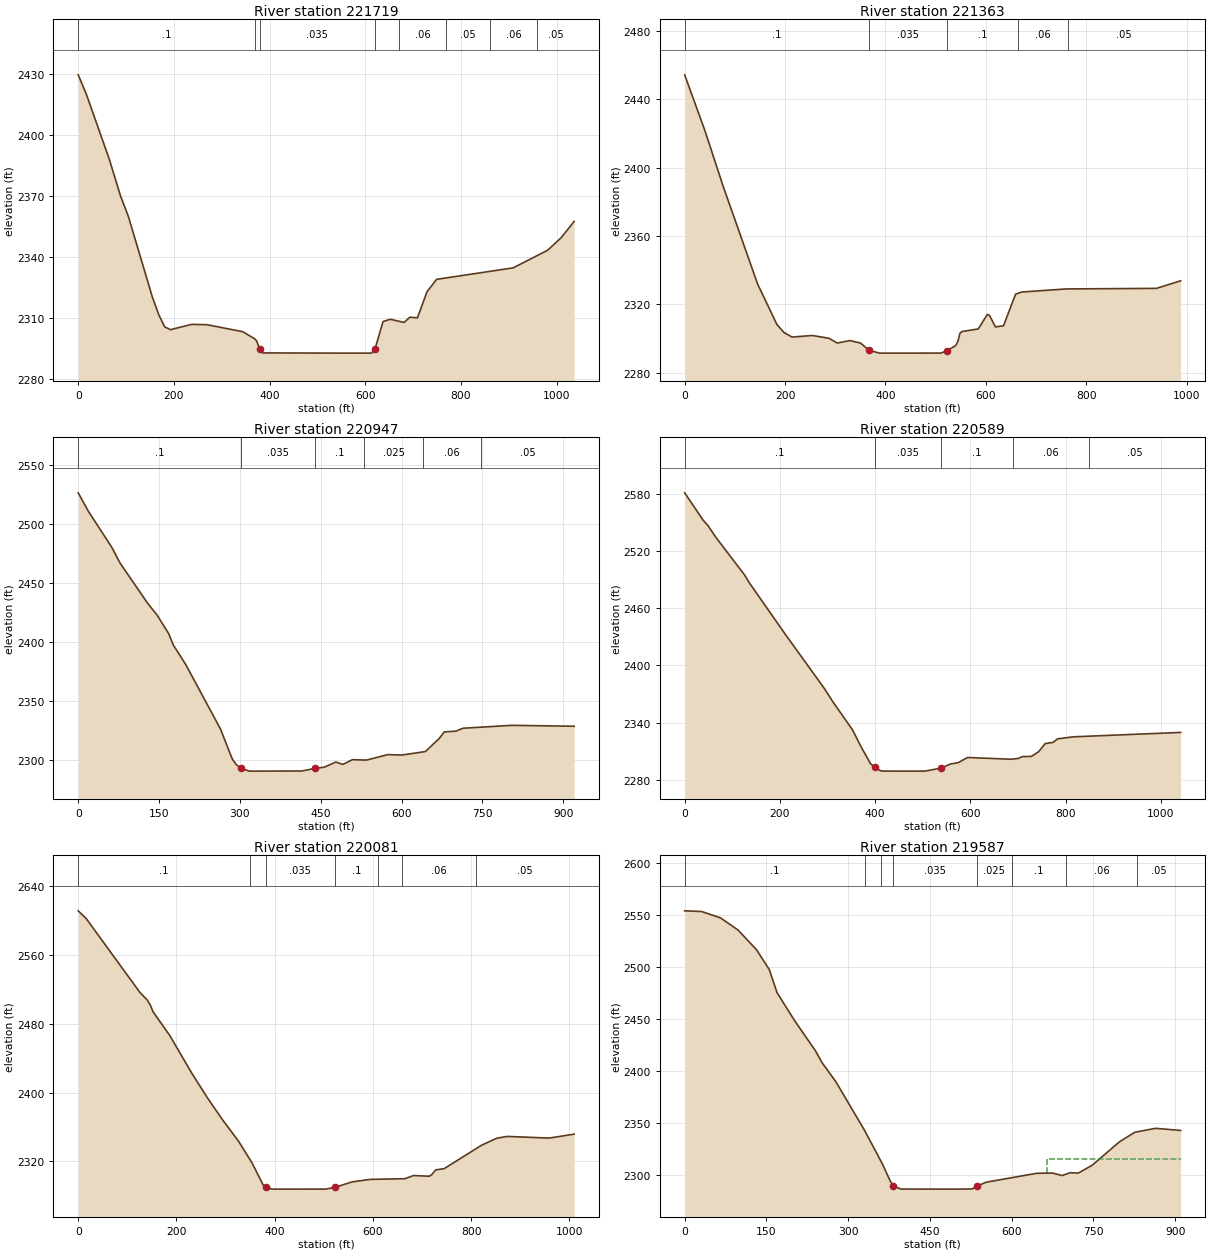
Type RM Length L Ch R = 1 ,221719  ,320.2,355.9,382.9
XS GIS Cut Line= 2
2269508.98811772491600.8147930852268472.77518464491562.258032784
#Sta/Elev= 30
       0 2429.74    16.8 2420.33    64.9 2388.27    88.5 2370.12   104.9 2360.04
     155  2320.4   168.9 2311.41   180.9 2305.69   192.9 2304.32     237 2306.94
     269 2306.78   343.9 2303.33   369.1 2299.82   373.1 2298.78   379.6 2294.58
   385.1 2292.89     550 2292.78   613.2 2292.79   620.7 2294.92   637.3 2308.32
   652.6 2309.44   681.3 2307.89   693.3 2310.44   709.3 2310.16   729.3 2322.98
   749.3 2329.09   909.4 2334.74   981.5 2343.42  1009.5 2349.52  1036.9 2357.59
#Mann= 8 ,-1,0
       0      .1       0     370    .025       0   379.6    .035       0
   620.7      .1       0     670     .06       0     770     .05       0
     860     .06       0     960     .05       0
Bank Sta=379.6,620.7
XS Rating Curve= 0 ,0
Exp/Cntr(USF)=0,0
Exp/Cntr=0.3,0.1

Type RM Length L Ch R = 1 ,221363  ,470,416.1,336.4
XS GIS Cut Line= 4
2269488.53630679 491261.621059312269224.44032236491292.921324132
2268903.61260794491187.2829303592268520.18436387491214.670662078
#Sta/Elev= 30
       0 2454.42    40.6 2421.53    76.9 2388.97   145.4  2331.9   183.7 2308.31
   197.7 2303.62   213.8 2300.91   254.1 2301.84   287.3 2300.22   304.1  2297.4
   329.4 2298.87   350.4 2297.41   367.3 2293.19   388.4 2291.51   510.5 2291.53
   523.1 2292.93     540 2295.96   544.2 2298.25   548.4 2303.11   552.6 2304.17
   584.9 2305.66   603.1 2314.19   607.2 2313.65   619.2 2306.86   635.2 2307.53
   659.3 2326.01   671.3 2327.27   759.6 2329.08     940 2329.42   988.1 2333.85
#Mann= 5 ,-1,0
       0      .1       0   367.3    .035       0   523.1      .1       0
  663.72     .06       0  763.72     .05       0
Bank Sta=367.3,523.1
XS Rating Curve= 0 ,0
Exp/Cntr(USF)=0,0
Exp/Cntr=0.3,0.1

Type RM Length L Ch R = 1 ,220947  ,376.8,358.5,332
XS GIS Cut Line= 3
2269429.73965542490692.1588280852268800.50764719 490969.31876181
 2268585.0324794491057.023925564
#Sta/Elev= 30
       0 2526.39    19.2 2510.45    62.1 2480.32    77.8 2466.62   129.4  2432.3
   145.9 2422.94   167.8 2406.93   176.5 2397.16   199.2 2380.94     264 2325.85
   285.8 2300.56   293.3 2295.68   302.4 2292.42   317.5 2290.15   415.1 2290.25
   438.8 2292.44   456.3 2293.46   478.1 2297.87   491.2 2295.84   508.7 2299.88
     535 2299.52   574.3 2304.16   600.5 2303.81   644.2 2306.76   669.5 2317.71
   679.2 2323.41   700.9 2324.09   713.8 2326.55   804.4 2329.03   920.2 2328.25
#Mann= 6 ,-1,0
       0      .1       0   302.4    .035       0   438.8      .1       0
     530    .025       0     640     .06       0  747.57     .05       0
Bank Sta=302.4,438.8
XS Rating Curve= 0 ,0
Exp/Cntr=0.3,0.1

Type RM Length L Ch R = 1 ,220589  ,523.8,507.9,489.8
XS GIS Cut Line= 2
     2269290.834      490240.7122268472.96150421490885.855913158
#Sta/Elev= 30
       0 2581.32      39 2552.46    49.2 2546.77    65.3 2534.73   125.7 2495.12
   135.8 2486.82     213 2431.55   293.8  2375.5   309.8 2362.93   352.5 2332.34
   370.2 2314.85   390.6 2296.61   400.8 2292.95     411 2289.43   416.1    2289
   504.5 2288.97   538.3 2292.08   558.7 2296.51     574 2297.74   594.4  2303.3
   685.8 2301.45   701.4 2302.35   708.5  2304.2   728.5 2304.47   743.5  2309.4
   757.4 2317.95   774.1 2319.19   782.9 2322.82   816.8 2325.02  1041.7 2329.62
#Mann= 5 ,-1,0
       0      .1       0   400.8    .035       0   538.3      .1       0
     690     .06       0     850     .05       0
Bank Sta=400.8,538.3
XS Rating Curve= 0 ,0
Exp/Cntr=0.3,0.1

Type RM Length L Ch R = 1 ,220081  ,508,493.9,479.1
XS GIS Cut Line= 2
     2268880.078      489814.2152268218.92427692490577.517330526
#Sta/Elev= 30
       0 2611.68    16.2 2602.73   125.6 2516.75     141 2507.58   146.7 2502.05
   152.6 2494.04   186.4  2466.6   231.7 2422.31   262.9 2394.23   293.1 2369.08
   326.7 2343.35   353.7 2318.52   376.3 2292.93     382 2289.73   395.5 2287.78
   503.9 2287.82   522.5 2289.78   557.8 2296.22   594.7 2299.12   665.4 2299.94
   682.6 2303.59   714.7  2302.8   719.5  2304.4     728 2310.16   745.2 2311.63
   821.5 2338.96   852.7 2347.13   873.5 2349.12     959 2347.19  1009.8 2351.76
#Mann= 7 ,-1,0
       0      .1       0     350    .025       0     382    .035       0
   522.5      .1       0     610    .025       0     660     .06       0
     810     .05       0
Bank Sta=382,522.5
XS Rating Curve= 0 ,0
Exp/Cntr=0.3,0.1

Type RM Length L Ch R = 1 ,219587  ,519.5,500,478.1
XS GIS Cut Line= 2
     2268431.728      489473.663     2267947.799       490244.32
#Sta/Elev= 30
       0 2554.35    31.2 2553.67    65.6 2547.63      98 2535.83   131.7 2516.99
   155.3 2497.83   169.5  2475.6   202.2 2448.34   239.9 2419.76   251.7 2408.54
   277.5 2389.87     330  2343.2   363.1 2310.54   377.3 2294.24   382.8 2290.03
   396.2 2286.66   495.4 2286.59   527.4 2286.75   536.1 2289.43   553.5 2293.28
     646 2301.82   674.9 2302.05   692.7 2299.66   707.3 2302.42   722.1 2301.99
   747.9 2309.61   797.7  2332.1     826 2341.33   864.2 2345.09     910 2343.04
#Mann= 8 ,-1,0
       0      .1       0     330    .025       0     360      .1       0
   382.8    .035       0   536.1    .025       0     600      .1       0
     700     .06       0     830     .05       0
#XS Ineff= 2 , 0
                          665.16         2315.79
Permanent Ineff=
       F       F
Bank Sta=382.8,536.1
XS Rating Curve= 0 ,0
Exp/Cntr=0.3,0.1

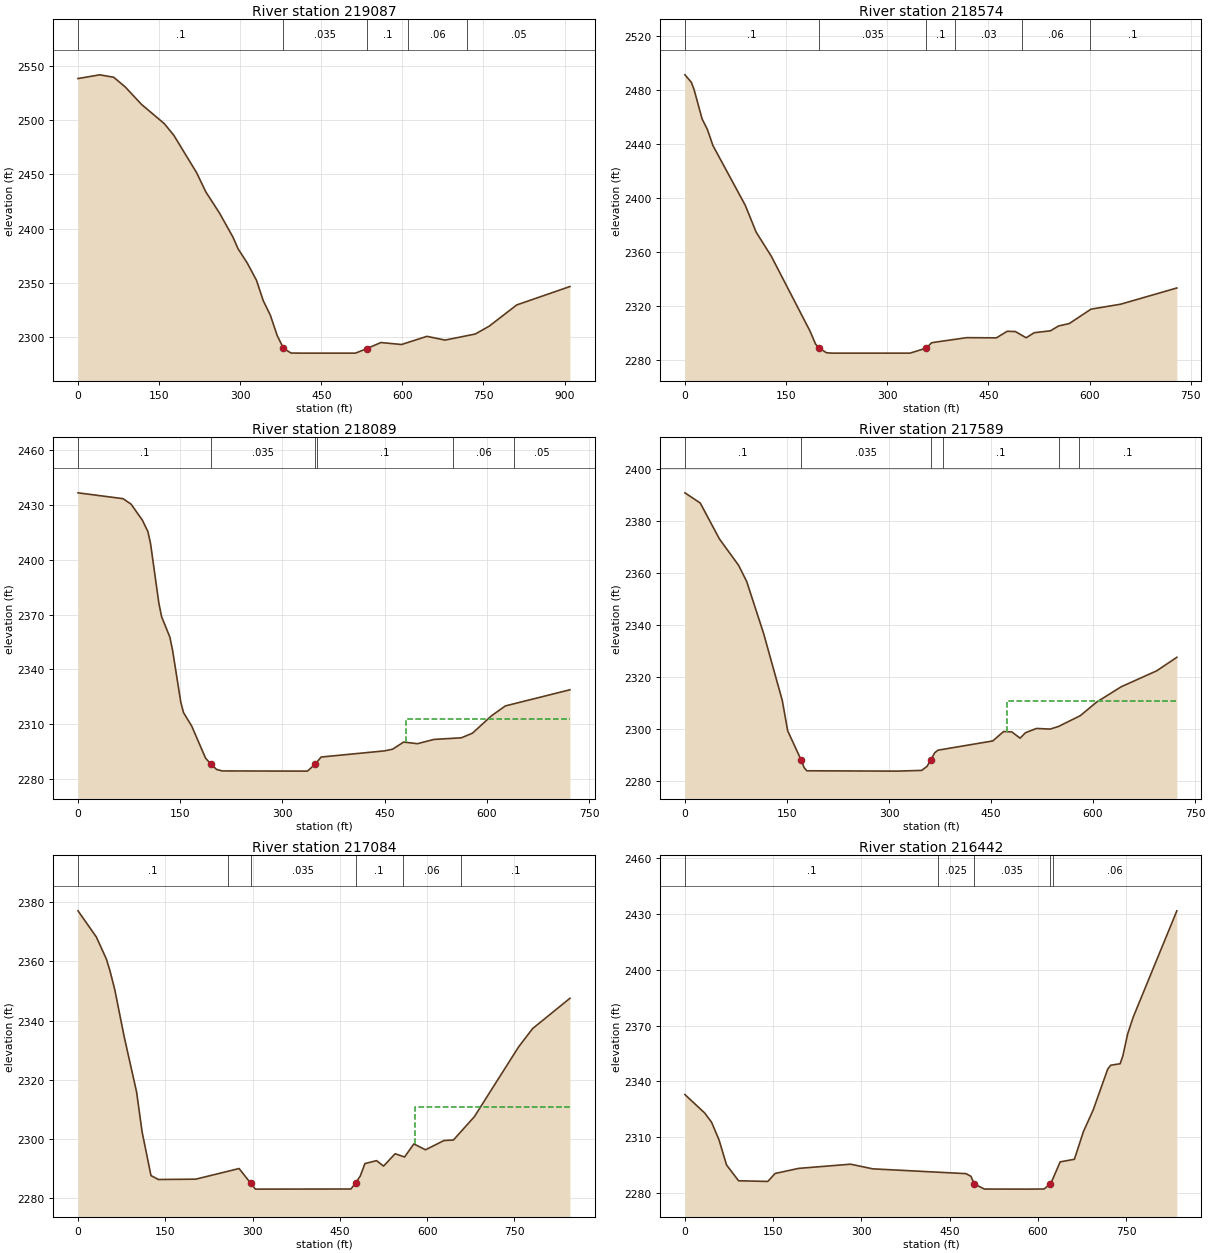
Type RM Length L Ch R = 1 ,219087  ,550,513.1,472.3
XS GIS Cut Line= 2
     2267901.599      489207.063      2267588.76        490061.6
#Sta/Elev= 30
       0 2538.09    40.2 2541.51    66.1 2539.27    87.4 2530.35   117.3 2514.39
   159.9 2496.48   177.4 2485.78   219.5 2451.43   236.5 2433.81   261.6 2414.49
   286.5 2392.36   296.2 2381.44   313.2 2368.33   330.2  2352.5   342.6  2333.9
   355.8 2320.42   368.6 2301.58   380.1 2289.98   394.1 2285.64   411.1 2285.56
   513.4 2285.56   534.7 2289.79   560.3 2295.31   598.6 2293.49   645.5    2301
     679 2297.55   734.9 2303.13   760.5 2310.31   811.6 2329.89     910 2346.81
#Mann= 5 ,-1,0
       0      .1       0   380.1    .035       0   534.7      .1       0
     610     .06       0     720     .05       0
Bank Sta=380.1,534.7
XS Rating Curve= 0 ,0
Exp/Cntr=0.3,0.1

Type RM Length L Ch R = 1 ,218574  ,493.1,484.6,475.2
XS GIS Cut Line= 2
2267228.18959504489283.694813909      2267260.12      490012.511
#Sta/Elev= 30
       0 2491.07     9.5 2485.55    13.5 2480.21    25.5 2458.34    33.5 2450.34
    41.5 2438.67    89.5 2394.36   105.6 2374.49     128  2356.7   185.7 2300.95
   193.7 2291.55   198.4 2288.95   209.7 2285.11   217.7 2284.81   333.8 2284.81
   357.8 2288.51   365.8  2292.5   373.8 2293.13   417.9 2296.28   461.9 2296.13
   477.9    2301     490 2300.81     506 2296.19     518 2299.94     542 2301.35
     554 2304.93     570 2306.73   602.1 2317.39   646.1 2321.07   729.5  2333.1
#Mann= 6 ,-1,0
       0      .1       0   198.4    .035       0   357.8      .1       0
     400     .03       0     500     .06       0     600      .1       0
Bank Sta=198.4,357.8
XS Rating Curve= 0 ,0
Exp/Cntr=0.3,0.1

Type RM Length L Ch R = 1 ,218089  ,496.5,500.4,505
XS GIS Cut Line= 2
2266722.00836774489339.652408947     2266819.168      490054.983
#Sta/Elev= 30
       0 2436.72    66.1 2433.52    77.9  2430.5    94.4 2421.79   102.5 2415.56
   106.5 2408.85   118.6 2376.44   122.6 2368.96   134.8 2357.68   138.8 2350.42
   150.9 2321.91   154.9  2316.3     167 2308.84   187.2 2291.38   195.2 2288.06
   203.4 2285.19   211.5 2284.38   336.6 2284.27     348 2288.03   356.8 2291.99
   449.6 2295.36   461.7 2296.28   477.9  2300.2   498.1  2299.3   522.3 2301.63
   562.6 2302.53   578.8 2305.04     607 2314.66   627.2    2320   721.9 2328.83
#Mann= 6 ,-1,0
       0      .1       0   195.2    .035       0     348    .025       0
     350      .1       0     550     .06       0     640     .05       0
#XS Ineff= 2 , 0
                           481.8         2312.76
Permanent Ineff=
       F       F
Bank Sta=195.2,348
XS Rating Curve= 0 ,0
Exp/Cntr=0.3,0.1

Type RM Length L Ch R = 1 ,217589  ,498.2,504.8,510.9
XS GIS Cut Line= 2
2266236.43417767489402.762408947       2266305.3      490122.691
#Sta/Elev= 30
       0 2390.86    22.5 2386.94    50.6 2373.17    78.8 2363.02    90.8 2356.77
   115.7 2336.74   143.1 2311.01   151.1  2299.3   171.2  2287.9   175.2 2285.17
   179.2 2283.94   311.8 2283.81     348 2284.09     356 2285.65   361.4 2288.15
   367.3  2290.9   372.1 2291.87   452.5 2295.42   468.5 2299.04   480.6 2298.89
   492.7 2296.49   500.7 2298.59   516.8 2300.23   536.9 2299.98   548.9 2300.96
   581.1 2305.12   605.2 2310.35   641.3 2316.25   693.6  2322.4   723.2  2327.6
#Mann= 6 ,-1,0
       0      .1       0   171.2    .035       0   361.4    .025       0
     380      .1       0     550     .06       0     580      .1       0
#XS Ineff= 2 , 0
                          474.14         2310.75
Permanent Ineff=
       F       F
Bank Sta=171.2,361.4
XS Rating Curve= 0 ,0
Exp/Cntr=0.3,0.1

Type RM Length L Ch R = 1 ,217084  ,557.2,641.7,726.7
XS GIS Cut Line= 3
2265877.48453408489359.2097722192265753.46265165489562.489308301
      2265776.72       490169.23
#Sta/Elev= 30
       0  2377.1    31.5 2368.27    48.6 2360.89    54.8 2356.95    63.2 2350.47
    79.3 2334.65   100.7 2315.91   110.1 2302.52   125.4 2287.73   138.2 2286.41
   202.2 2286.52   276.8 2290.11   296.4 2285.24   304.9 2283.16     469  2283.2
     477 2285.24     485 2287.58     493 2291.78     513 2292.78     525 2290.94
     545 2295.11   561.1    2294   577.1 2298.42   597.1 2296.44   628.8 2299.56
   645.1 2299.74   681.1 2307.62   757.2  2331.2   781.2 2337.36   845.3 2347.58
#Mann= 6 ,-1,0
       0      .1       0  258.13    .025       0   296.4    .035       0
     477      .1       0  558.13     .06       0  658.13      .1       0
#XS Ineff= 2 , 0
                          578.59         2310.78
Permanent Ineff=
       F       F
Bank Sta=296.4,477
XS Rating Curve= 0 ,0
Exp/Cntr=0.3,0.1

Type RM Length L Ch R = 1 ,216442  ,259.4,266.8,274.6
XS GIS Cut Line= 2
2265587.15911395489216.7267047622264936.69026283489741.747991738
#Sta/Elev= 30
       0 2332.93    33.7 2323.02    45.3 2318.08      58 2308.56    70.7 2295.14
    91.2 2286.65   140.8  2286.3   153.2 2290.57     193  2293.3   281.4 2295.56
   319.2 2293.06   477.5 2290.49     486 2289.05   491.7 2284.95   508.8 2282.21
   582.7 2282.17   610.4 2282.25   619.7 2284.75   624.72287.334   637.6 2296.81
   661.8 2298.19   677.2 2313.14   693.7 2324.67   718.4 2346.62   723.5  2348.7
   739.5 2349.49   744.1 2353.66   752.2 2365.43   761.9 2374.67   835.9 2431.62
#Mann= 5 ,-1,0
       0      .1       0     430    .025       0   491.7    .035       0
   619.7    .025       0   624.7     .06       0
Bank Sta=491.7,619.7
XS Rating Curve= 0 ,0
Exp/Cntr(USF)=0,0
Exp/Cntr=0.3,0.1

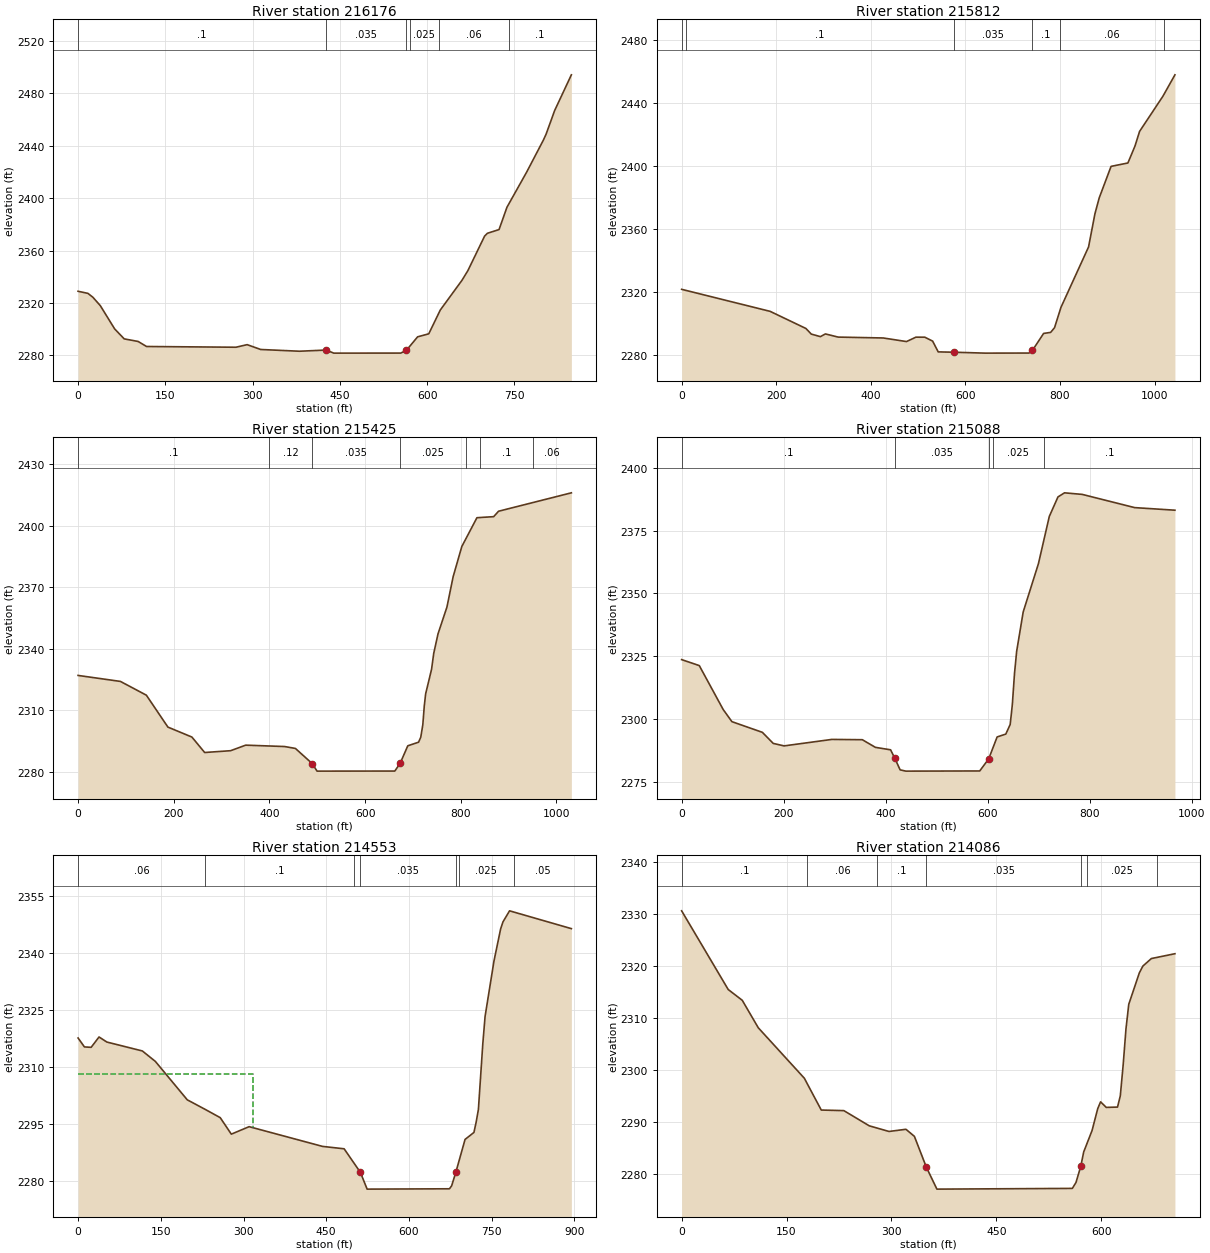
Type RM Length L Ch R = 1 ,216176  ,352,363.5,372.5
XS GIS Cut Line= 2
2265422.21879813489068.0481102212264715.99547405489537.314924243
#Sta/Elev= 30
       0 2328.98    16.9 2327.38    25.4 2324.43    38.2 2318.01    62.9 2300.23
    79.3 2292.63   103.2 2290.66   117.7 2286.81   271.4 2286.25   290.6 2288.22
   313.9 2284.53   380.3  2283.2   426.4 2284.09   439.5 2281.75   554.7 2281.78
   564.4 2283.91   583.6 2294.19   602.8  2296.5   622.6 2314.66   659.8 2337.31
     670 2344.73   698.8 2371.15   703.6 2373.26   723.6  2376.1   737.2 2393.16
   770.9 2419.84   799.7 2444.32   804.5 2448.99   819.1 2466.91   847.9 2494.25
#Mann= 6 ,-1,0
       0      .1       0   426.4    .035       0   564.4      .1       0
     570    .025       0     620     .06       0     740      .1       0
Bank Sta=426.4,564.4
XS Rating Curve= 0 ,0
Exp/Cntr(USF)=0,0
Exp/Cntr=0.3,0.1

Type RM Length L Ch R = 1 ,215812  ,388,386.9,386.9
XS GIS Cut Line= 3
 2265306.2518015488576.4472521052264977.11852459488952.343280902
2264493.75820647489200.521041203
#Sta/Elev= 30
       0  2321.6   187.1 2307.61   262.8 2296.74   274.1 2293.18   293.4 2291.56
     304 2293.28     331 2291.27   426.3 2290.71   475.4 2288.43   495.4 2291.23
   514.2  2291.2   530.7 2288.72   542.5 2281.88   575.2 2281.67   641.6 2281.09
   734.5 2281.14   741.6 2282.77   765.4  2293.6   780.2 2294.25   788.5 2297.25
   801.9 2310.05   860.4 2348.51   873.9 2369.59   882.9 2379.63     908 2399.66
   943.6 2401.81   958.5 2412.53   968.3 2421.87  1017.8 2444.28    1043 2457.78
#Mann= 6 ,-1,0
       0     .06       0      10      .1       0   575.2    .035       0
   741.6      .1       0  799.63     .06       0 1019.63      .1       0
Bank Sta=575.2,741.6
XS Rating Curve= 0 ,0
Exp/Cntr=0.3,0.1

Type RM Length L Ch R = 1 ,215425  ,322.2,337.5,351.4
XS GIS Cut Line= 2
2265158.52596198 488418.715437582264245.34997381488897.544107595
#Sta/Elev= 30
       0 2327.02    88.5 2324.11   142.7 2317.41   187.8 2301.85   237.9 2297.01
   264.6 2289.48   318.8 2290.36   350.4 2293.06   431.7 2292.39   454.3 2291.46
   489.5 2284.06   499.5 2280.41   662.1 2280.45   673.2 2284.21   689.2 2292.75
   711.7  2294.5   716.3 2296.92   720.6 2303.05   723.6 2312.02   726.5 2318.04
   738.9 2330.06   743.4 2337.79   752.4 2347.31     771 2360.32     784 2375.14
   802.1 2389.82   833.7 2403.85   868.7 2404.36   878.9    2407  1031.1 2415.97
#Mann= 7 ,-1,0
       0      .1       0     400     .12       0   489.5    .035       0
   673.2    .025       0     810     .06       0     840      .1       0
     950     .06       0
Bank Sta=489.5,673.2
XS Rating Curve= 0 ,0
Exp/Cntr(USF)=0,0
Exp/Cntr=0.3,0.1

Type RM Length L Ch R = 1 ,215088  ,508.8,534.3,557.4
XS GIS Cut Line= 2
2264984.68754541488205.225822331     2264076.958      488539.288
#Sta/Elev= 30
       0  2323.6    34.6 2321.22    81.5 2303.72    98.6 2298.89   158.3 2294.64
   179.6 2290.23   200.9 2289.24   294.6 2291.82   354.3  2291.7   379.9 2288.66
   409.7 2287.68   418.2 2284.22   428.4  2279.7   439.6 2279.19   584.5 2279.26
   602.1 2284.08   618.6  2292.8   635.6 2293.94   644.2 2297.77   648.4 2305.63
   652.7 2318.16   656.9 2326.92   669.7 2342.58   699.6 2361.82   720.9 2380.62
   737.9 2388.39   750.7 2390.02   785.5 2389.39   888.3 2384.13   967.2  2383.1
#Mann= 5 ,-1,0
       0      .1       0   418.2    .035       0   602.1      .1       0
     610    .025       0     710      .1       0
Bank Sta=418.2,602.1
XS Rating Curve= 0 ,0
Exp/Cntr=0.3,0.1

Type RM Length L Ch R = 1 ,214553  ,467.3,467.5,469.5
XS GIS Cut Line= 2
2265003.61287934487777.8852189872264117.03292211487897.633451527
#Sta/Elev= 30
       0 2317.68    11.5 2315.33    23.7 2315.22      38 2317.95    52.2 2316.61
   116.5 2314.27   140.2 2311.51     198  2301.4     230 2298.92   257.8  2296.7
   277.9 2292.36   310.2 2294.33   443.4 2289.13   482.5  2288.5     512 2282.29
   524.2 2277.88   673.5 2277.97   677.5 2278.76   685.2 2282.38   701.8 2290.97
   717.9 2292.81   721.9  2295.5     726 2298.87     734 2316.16   738.1 2323.35
   754.2 2337.92   766.3  2346.4   770.5 2348.24   782.5 2351.17   894.6 2346.48
#Mann= 7 ,-1,0
       0     .06       0     230      .1       0     500    .025       0
     512    .035       0   685.2      .1       0     690    .025       0
     790     .05       0
#XS Ineff= 2 , 0
          316.62 2308.33
Permanent Ineff=
       F       F
Bank Sta=512,685.2
XS Rating Curve= 0 ,0
Exp/Cntr=0.3,0.1

Type RM Length L Ch R = 1 ,214086  ,393.3,392.7,392.2
XS GIS Cut Line= 2
     2264790.151      487336.0832264090.75199158487428.889429774
#Sta/Elev= 30
       0 2330.69    66.6 2315.56    86.7 2313.48   109.6  2308.2   175.5 2298.49
   199.7 2292.37     232 2292.26   268.3 2289.34   296.6 2288.25   320.8 2288.67
   332.9 2287.31     350 2281.38   365.1 2277.16   558.8  2277.3     564 2278.44
   570.9 2281.58     575  2284.3     587 2288.44   595.1 2292.64   599.2 2293.95
   607.3 2292.88   623.4 2292.94   627.4 2295.11   631.5 2301.09   635.5 2307.99
   639.5 2312.72   654.6 2318.75   659.7 2320.07   671.8 2321.51   705.5 2322.44
#Mann= 7 ,-1,0
       0      .1       0     180     .06       0     280      .1       0
     350    .035       0   570.9      .1       0     580    .025       0
     680      .1       0
Bank Sta=350,570.9
XS Rating Curve= 0 ,0
Exp/Cntr=0.3,0.1

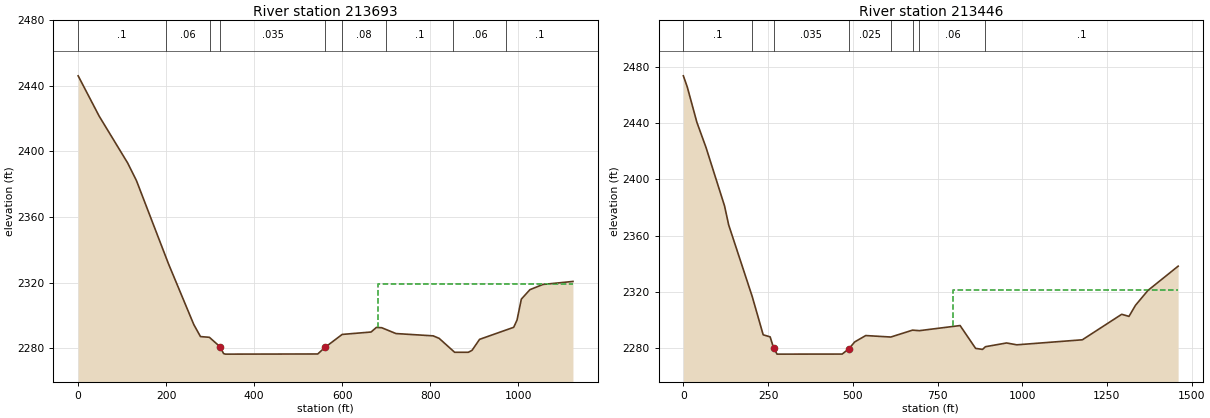
Type RM Length L Ch R = 1 ,213693  ,256.8,247.5,237.7
XS GIS Cut Line= 3
2264711.59520248486948.2330784212263956.95380174487052.272622067
2263748.68402948 487349.18232284
#Sta/Elev= 30
       0 2446.17    47.9  2421.5   112.5 2392.98   132.7 2382.09   205.3 2331.43
   262.9 2294.32     278 2287.03   298.2 2286.59   322.4 2280.84   330.5 2276.66
   334.6 2276.32   544.5 2276.41   560.7 2280.37     600 2288.34   665.7 2289.81
   677.8 2292.62   689.9 2292.43   722.2 2288.88   806.9 2287.47   820.4 2285.94
   855.7 2277.43   886.5 2277.43   895.1 2278.61   912.3 2285.34   989.8 2292.69
   997.4  2297.1  1007.2 2309.88  1026.7 2315.65    1056 2318.83  1124.5 2320.69
#Mann= 9 ,-1,0
       0      .1       0     200     .06       0     300    .025       0
   322.4    .035       0   560.7    .025       0     600     .08       0
     700      .1       0  851.78     .06       0  971.78      .1       0
#XS Ineff= 2 , 0
                          681.46          2319.3
Permanent Ineff=
       F       F
Bank Sta=322.4,560.7
XS Rating Curve= 0 ,0
Exp/Cntr=0.3,0.1

Type RM Length L Ch R = 1 ,213446  ,158.5,175.3,183.3
BEGIN DESCRIPTION:
structure xs 4
END DESCRIPTION:
XS GIS Cut Line= 5
 2264607.4599645486771.5805654262264395.39778284486730.614007607
2263833.35006781486849.871507762 2263678.8454004486806.610200887
2263205.18413075486993.502039129
#Sta/Elev= 30
       0 2473.72    11.5 2465.81      40 2440.59    66.8 2422.79   121.5  2381.2
   133.7 2367.68   203.1 2316.79   235.6 2289.46   256.1 2288.01  266.61 2279.91
   276.5 2275.72   468.7 2275.76   489.2 2279.69   505.5 2284.38   538.2 2288.93
   612.2 2287.88   676.3 2292.78   696.5 2292.41   816.7 2296.05   862.4 2279.82
   882.9 2279.07   891.5    2281   953.9 2283.66     984 2282.34  1177.5 2285.92
  1293.6 2304.06  1315.1 2302.58  1334.3 2310.46    1371 2321.02  1460.2  2338.3
#Mann= 8 ,-1,0
       0      .1       0   203.1     .06       0  266.61    .035       0
   489.2    .025       0   612.2     .05       0   676.3    .025       0
   696.5     .06       0   891.5      .1       0
#XS Ineff= 2 , 0
                          795.04         2321.61
Permanent Ineff=
       F       F
Bank Sta=266.61,489.2
XS Rating Curve= 0 ,0
Exp/Cntr(USF)=0,0
Exp/Cntr=0.5,0.3