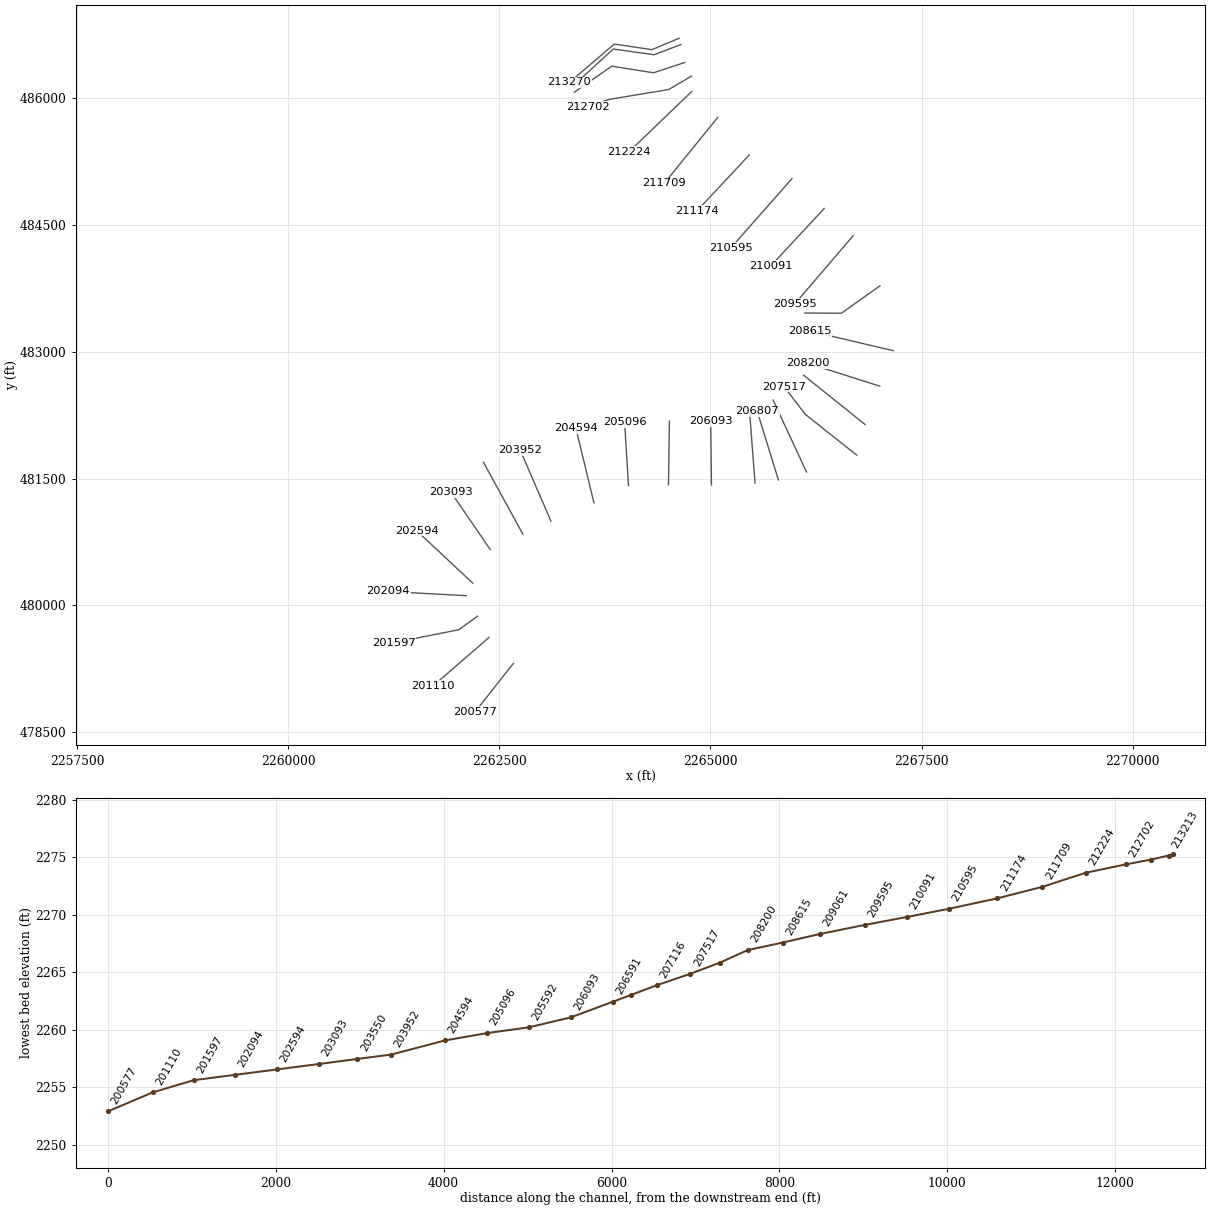
HEC-RAS study GRNBRRRV.prj: GRNBRRRV

--- GRNBRRRV.g01 (geometry) --- (continued)

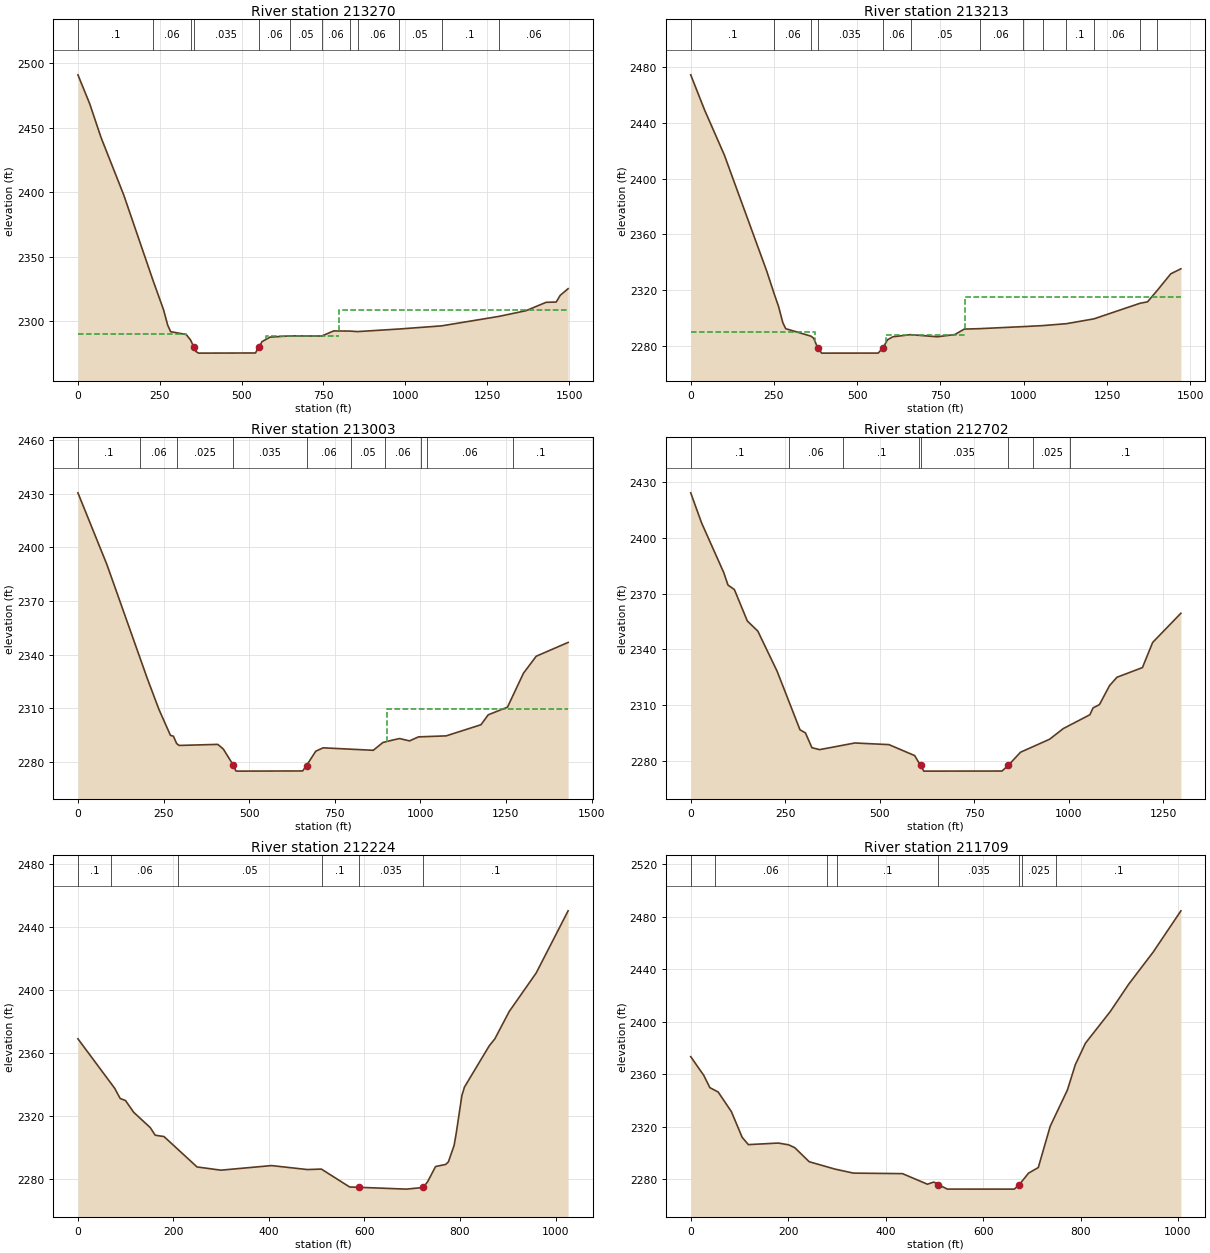
Type RM Length L Ch R = 1 ,213270  ,65.9,57.5,58.1
BEGIN DESCRIPTION:
structure xs 3
END DESCRIPTION:
XS GIS Cut Line= 4
2264629.14814217486711.3356274562264308.64507217486576.386966404
2263862.70595462486642.8352534342263331.15202029486189.617574749
#Sta/Elev= 30
       0  2490.8      36  2468.4    70.5 2442.34   139.8 2397.88   230.2 2330.98
   261.5 2308.89   274.2 2296.97   283.2  2291.9   330.9 2289.67   344.5 2285.27
   353.1  2280.4   360.4 2276.57   368.5 2275.28   542.2  2275.4     553 2280.11
   562.6 2284.24   586.8 2287.67   647.5 2288.63   744.6 2288.51     781 2292.46
     830 2292.36   854.5 2291.96     980 2293.94  1110.9  2296.4  1285.5 2303.71
  1368.4 2308.12    1430 2314.64  1460.8 2314.83  1473.2 2320.08  1497.2 2325.18
#Mann= 12 ,-1,0
       0      .1       0   230.2     .06       0   344.5     .08       0
   353.1    .035       0     553     .06       0   647.5     .05       0
   744.6     .06       0     830     .05       0   854.5     .06       0
     980     .05       0  1110.9      .1       0  1285.5     .06       0
#XS Ineff= 3 ,-1
       0     331 2290.48     575  797.75 2288.79  797.75  1497.2 2309.05
Permanent Ineff=
       F       F       F
Bank Sta=353.1,553
XS Rating Curve= 0 ,0
Exp/Cntr(USF)=0,0
Exp/Cntr=0.5,0.3

Type RM Length L Ch R = 1 ,213213  ,211.4,209.6,207.7
BEGIN DESCRIPTION:
structure xs 2
END DESCRIPTION:
XS GIS Cut Line= 4
2264650.83631984486636.6319043742264332.74304736486516.142028434
2263850.34558123486584.1234798192263375.09362299486148.593492698
#Sta/Elev= 30
       0 2474.18    41.3 2449.23   100.9 2416.89   228.1 2333.92   250.9 2317.36
   263.8 2308.53   276.6 2296.89   285.2 2292.64   360.9 2287.31     369 2285.88
   381.1 2279.07   393.2 2275.16   562.9 2275.19  576.91 2278.88   591.2 2284.76
   607.1 2286.86   660.2 2288.37   740.6 2286.85   793.1 2288.45   821.4 2292.35
   867.7 2292.66   997.4 2294.11  1057.4 2294.85  1128.2 2296.22  1210.6 2299.66
    1349  2310.8  1371.7 2311.85  1399.9 2319.72  1441.5 2331.88  1471.9 2335.47
#Mann= 13 ,-1,0
       0      .1       0   250.9     .06       0   360.9    .025       0
   381.1    .035       0  576.91     .06       0   660.2     .05       0
   867.7     .06       0   997.4     .05       0  1057.4     .06       0
  1128.2      .1       0  1210.6     .06       0    1349      .1       0
  1399.9     .06       0
#XS Ineff= 3 ,-1
     1.2   374.22290.145     585  824.79    2288  824.79  1471.9 2315.64
Permanent Ineff=
       F       F       F
Bank Sta=381.1,576.91
XS Rating Curve= 0 ,0
Exp/Cntr(USF)=0,0
Exp/Cntr=0.5,0.3

Type RM Length L Ch R = 1 ,213003  ,254,300.9,340.9
BEGIN DESCRIPTION:
xs 1
END DESCRIPTION:
XS GIS Cut Line= 4
2264696.94487922486424.5633684712264327.13217045486302.747283196
2263833.07144982486381.0221114312263387.61742705486072.292220328
#Sta/Elev= 30
       0 2430.59      85 2390.27   202.6 2326.68   236.7 2309.33   270.3 2294.81
   278.8 2294.38   288.4 2290.22   295.6 2289.19   408.6 2289.78   424.8 2287.14
   453.22278.333   461.2 2274.94   465.3 2274.81   656.3 2274.91   667.7 2277.96
   694.7 2285.98   716.3 2287.85   862.5 2286.47   890.7 2290.84   913.1 2291.92
   939.3 2293.05   968.5 2291.74   994.6 2293.98  1075.6 2294.55  1177.2 2300.79
  1198.3 2306.33  1254.5 2310.62  1301.2 2329.61  1338.5 2339.13  1431.6 2346.85
#Mann= 10 ,-1,0
       0      .1       0     180     .06       0     290    .025       0
   453.2    .035       0   667.7     .06       0  797.94     .05       0
  897.94     .06       0 1000.78     .05       0 1020.78     .06       0
 1270.78      .1       0
#XS Ineff= 2 , 0
                          901.41         2309.75
Permanent Ineff=
       F       F
Bank Sta=453.2,667.7
XS Rating Curve= 0 ,0
Exp/Cntr=0.3,0.1

Type RM Length L Ch R = 1 ,212702  ,401.6,478.5,533.3
XS GIS Cut Line= 4
2264777.03197917486263.8299667662264506.69917323486104.457611428
2263804.99739074485988.3963718192263547.59890917485903.402115639
#Sta/Elev= 30
       0 2424.41    28.8 2408.16    87.3 2381.45    98.5 2374.71   115.5 2372.26
   149.6 2355.34   177.4 2349.88   228.5 2328.22   288.9 2296.68   303.4 2294.98
   320.4 2287.05   340.7 2285.97   433.9 2289.56   524.1 2288.68   592.1 2282.78
   607.6 2277.44   616.4 2274.39     823 2274.44   839.4 2277.45     872 2284.58
   948.9 2291.58   985.3 2297.35  1055.4 2304.78  1063.8 2308.48  1080.7 2310.24
  1107.4 2320.49    1127 2324.99  1194.4 2330.21  1221.4 2343.76  1296.1  2359.5
#Mann= 8 ,-1,0
       0      .1       0     260     .06       0  403.81      .1       0
  603.81    .025       0   607.6    .035       0   839.4      .1       0
  903.81    .025       0 1003.81      .1       0
Bank Sta=607.6,839.4
XS Rating Curve= 0 ,0
Exp/Cntr=0.3,0.1

Type RM Length L Ch R = 1 ,212224  ,503.2,514.7,523.8
XS GIS Cut Line= 2
2264779.99906409486082.0669646892264040.11778282485370.827671021
#Sta/Elev= 30
       0 2368.95    76.9 2337.62    88.5 2331.13    99.6 2329.84   116.7 2322.39
   151.4 2312.68   161.8 2307.84   180.2 2306.99   249.4 2287.72   299.4 2285.68
   405.3 2288.59   480.3 2286.07   509.7 2286.37   569.1 2274.99   587.9 2274.82
   687.8 2273.66   722.8 2274.71   732.2 2278.36   748.8 2287.99     770 2289.33
   775.6 2290.91   787.6 2301.37     792 2308.98   803.9 2333.02   809.3 2338.37
   861.3 2364.56   872.8 2368.88   902.9 2386.21   959.5 2410.72  1026.3 2450.09
#Mann= 6 ,-1,0
       0      .1       0      70     .06       0     210     .05       0
     510      .1       0   587.9    .035       0   722.8      .1       0
Bank Sta=587.9,722.8
XS Rating Curve= 0 ,0
Exp/Cntr=0.3,0.1

Type RM Length L Ch R = 1 ,211709  ,543.7,535.5,528.1
XS GIS Cut Line= 2
2265086.73820248485773.9568139092264452.63126451484993.007090827
#Sta/Elev= 30
       0 2373.34    26.8 2359.08    39.3 2349.76    56.4  2346.4    83.4 2331.52
   105.6 2311.91   118.3 2306.34   179.6 2307.54   200.8  2306.2   213.5 2304.03
   243.2  2293.3     296  2287.7     334 2284.64   434.6 2284.24   485.8 2276.19
     499 2277.84   508.4 2275.85   526.6 2272.47     664 2272.44   673.5 2275.54
   693.4 2284.65   713.3 2288.89   737.8 2320.35     773 2347.89   789.3  2367.2
     810 2383.57   861.5 2407.96   898.8 2428.53   949.1 2453.02    1006 2484.44
#Mann= 8 ,-1,0
       0      .1       0      50     .06       0     280     .05       0
     300      .1       0   508.4    .035       0   673.5      .1       0
     680    .025       0     750      .1       0
Bank Sta=508.4,673.5
XS Rating Curve= 0 ,0
Exp/Cntr=0.3,0.1

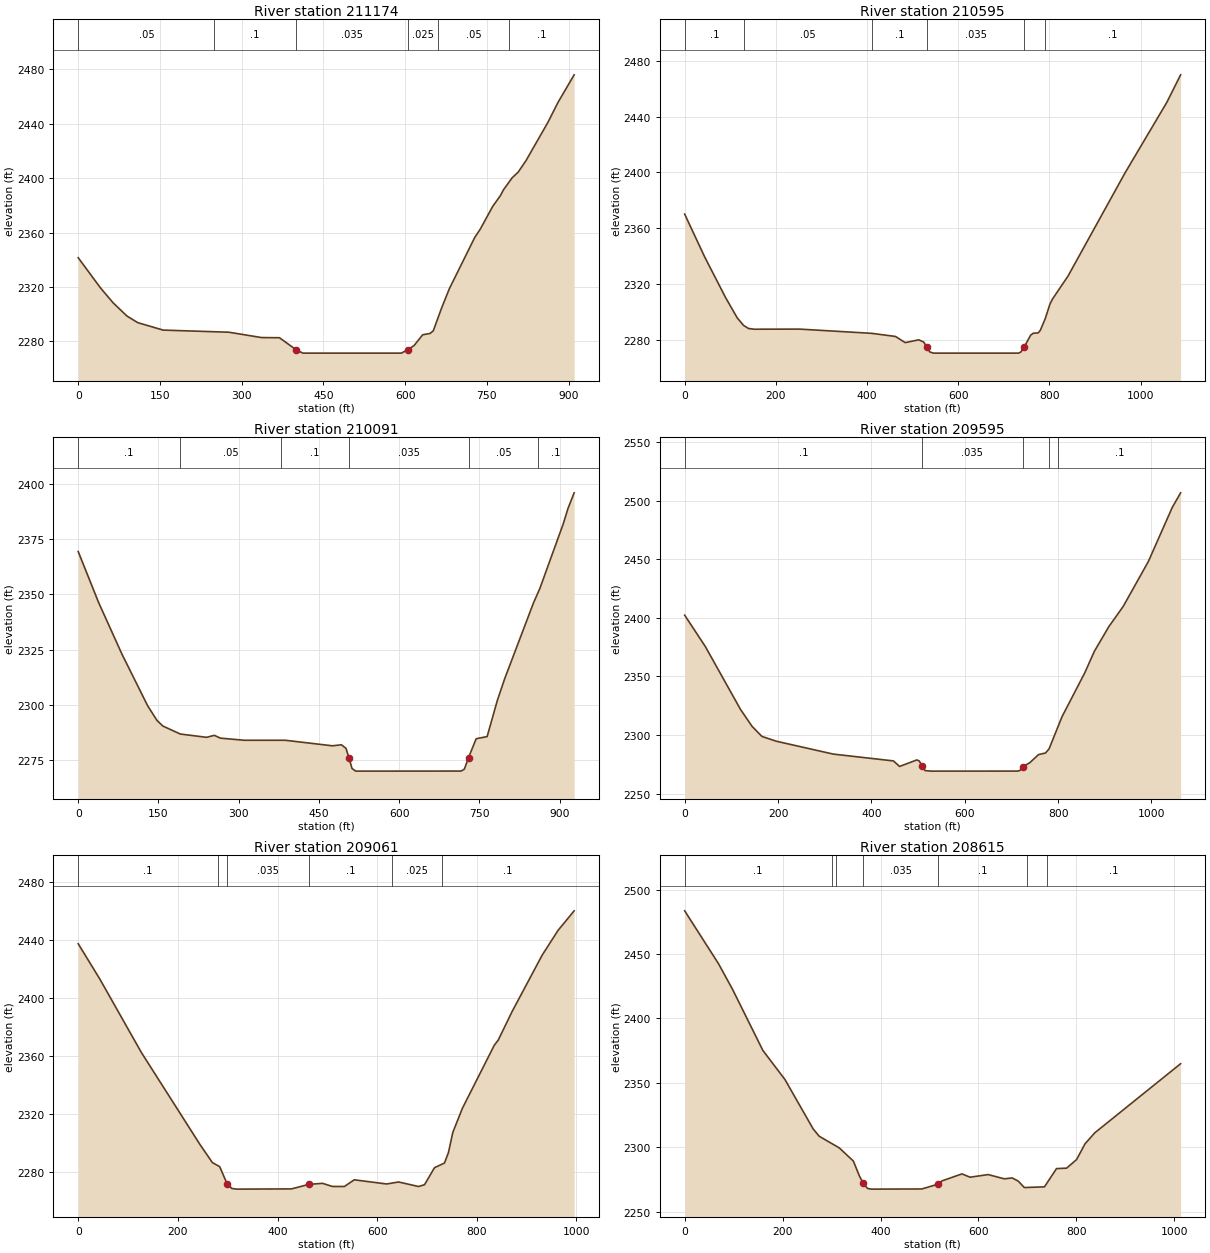
Type RM Length L Ch R = 1 ,211174  ,575.5,579,582.7
XS GIS Cut Line= 2
2265461.05522729485330.9645081952264839.63822729484666.178508195
#Sta/Elev= 30
       0 2341.61    40.8 2319.43    64.1 2308.41    89.6 2298.66   109.4 2293.83
   155.8 2288.38   276.6 2286.81   336.4 2282.88   369.3 2282.75   399.6 2273.98
   412.2 2271.44   592.9 2271.44   604.6 2273.89   616.3 2277.03   632.1 2284.94
   645.6 2285.91   651.5 2287.82   666.9 2304.75   681.1 2318.88   727.6  2356.5
   737.7 2362.57   760.3 2379.17   774.5 2387.15   780.3 2391.52   796.4 2400.43
   807.3 2404.52   821.4 2412.82   862.1 2441.28   879.9 2455.45     910 2476.06
#Mann= 6 ,-1,0
       0     .05       0     250      .1       0   399.6    .035       0
   604.6    .025       0     660     .05       0     790      .1       0
Bank Sta=399.6,604.6
XS Rating Curve= 0 ,0
Exp/Cntr=0.3,0.1

Type RM Length L Ch R = 1 ,210595  ,507.4,503.6,500.3
XS GIS Cut Line= 2
 2265966.0252809485050.088661052     2265246.355      484234.491
#Sta/Elev= 30
       0 2370.13    43.9 2339.45    89.8  2310.3   115.3 2295.79   129.2 2290.38
   139.9 2288.22   152.2 2287.67   251.9 2287.75     410 2284.72   462.3 2282.48
   483.7 2278.06   513.3 2280.06     524 2278.53   531.9 2274.62   537.6 2271.39
   545.3 2270.53     732 2270.53   737.4 2271.35   744.4 2274.76   758.7 2283.38
   764.1 2284.72   775.6 2285.09   780.1 2286.94   790.7 2295.18   801.1 2305.66
   806.7 2309.29   840.8 2325.79   965.5 2399.53  1057.5 2450.28  1087.7 2469.98
#Mann= 6 ,-1,0
       0      .1       0     130     .05       0     410      .1       0
   531.9    .035       0   744.4     .05       0     790      .1       0
Bank Sta=531.9,744.4
XS Rating Curve= 0 ,0
Exp/Cntr=0.3,0.1

Type RM Length L Ch R = 1 ,210091  ,490.7,495.8,501
XS GIS Cut Line= 2
2266347.99648338484696.9804709772265716.33588835484018.027090827
#Sta/Elev= 30
       0 2369.49      38 2346.45    81.8 2322.91   129.9 2299.46   147.2 2292.87
   158.2 2290.29   190.9 2286.65   240.1 2285.16   254.5 2286.06   265.8 2284.79
   311.1 2283.81   387.6 2283.81   475.2 2281.31   492.2 2281.76   500.7 2280.14
   506.4 2275.72     512 2271.01   518.8 2269.81   716.2 2269.84     722 2270.71
   729.9 2275.99   744.1 2284.51   764.6  2285.5   783.7 2301.92   797.4 2311.75
   851.2 2346.14     863 2352.62   906.7 2381.93   915.8 2389.07   927.3 2396.15
#Mann= 6 ,-1,0
       0      .1       0     190     .05       0     380      .1       0
   506.4    .035       0   729.9     .05       0     860      .1       0
Bank Sta=506.4,729.9
XS Rating Curve= 0 ,0
Exp/Cntr=0.3,0.1

Type RM Length L Ch R = 1 ,209595  ,560.8,534.3,512.2
XS GIS Cut Line= 2
2266691.35390075484374.705078421     2265999.804       483568.23
#Sta/Elev= 30
       0 2402.26    44.2 2375.52   119.6 2321.82   144.3 2307.38   165.4 2298.78
     197 2294.59   318.2 2283.68   447.3 2277.84   460.4 2273.12   497.3  2278.7
   502.6 2277.75   508.8 2273.34   514.9 2269.58   528.1 2269.13   713.4 2269.16
   718.2 2269.71   723.9 2272.72   723.9 2272.73   739.7 2276.45   757.9 2283.23
     773 2284.62   780.6 2288.13   808.2 2315.47   857.2 2353.16   877.5 2371.31
   908.3 2392.27   939.5 2409.81   993.4 2448.16  1044.4 2494.17  1062.4 2506.71
#Mann= 5 ,-1,0
       0      .1       0   508.8    .035       0   723.9      .1       0
     780     .05       0     800      .1       0
Bank Sta=508.8,723.9
XS Rating Curve= 0 ,0
Exp/Cntr=0.3,0.1

Type RM Length L Ch R = 1 ,209061  ,538,446.3,369.6
XS GIS Cut Line= 3
2267007.61941737483781.1978843612266551.63412406483456.996529023
2266115.85074391483459.364280902
#Sta/Elev= 30
       0 2437.46    43.5 2413.06   126.9 2362.43   244.7 2298.92   269.2 2286.66
     284  2283.8   298.7 2272.04   308.5 2268.79   318.3 2268.34     428 2268.49
   462.5 2271.59   490.1 2272.34   510.2 2270.18   534.3 2270.16   553.9 2274.76
     619 2271.89     643 2273.26     683 2270.14     695 2271.37     715  2283.1
     735  2286.3     743 2293.52   751.8 2307.43     771 2324.04     835 2367.49
     843 2371.09     871 2390.88     931 2429.53     963 2446.66   995.3 2460.14
#Mann= 6 ,-1,0
       0      .1       0     280    .025       0   298.7    .035       0
   462.5      .1       0  629.49    .025       0  729.49      .1       0
Bank Sta=298.7,462.5
XS Rating Curve= 0 ,0
Exp/Cntr=0.3,0.1

Type RM Length L Ch R = 1 ,208615  ,426.3,414.8,407.3
XS GIS Cut Line= 2
     2267163.724      483014.2442266177.36669429483245.018533007
#Sta/Elev= 30
       0 2483.47    69.4 2442.27    98.1 2422.33   159.7 2375.19   204.9 2352.58
   262.5 2314.26   274.8 2308.61   315.9 2299.54   344.6 2289.34   356.9 2277.77
   364.9 2272.03   373.4 2268.15   381.6 2267.59   484.3 2267.71   518.1 2271.49
   525.4 2273.96   566.4 2279.41   582.9 2276.84   619.8 2278.88   652.7 2275.59
   669.1 2276.26   681.5 2273.77   693.8 2268.81   734.9 2269.37   759.5  2283.5
   780.1 2283.86   800.6 2290.57   817.7 2302.72   837.6 2311.25    1013 2364.88
#Mann= 7 ,-1,0
       0      .1       0     300     .12       0     310      .1       0
   364.9    .035       0   518.1      .1       0     700    .025       0
     740      .1       0
Bank Sta=364.9,518.1
XS Rating Curve= 0 ,0
Exp/Cntr=0.3,0.1

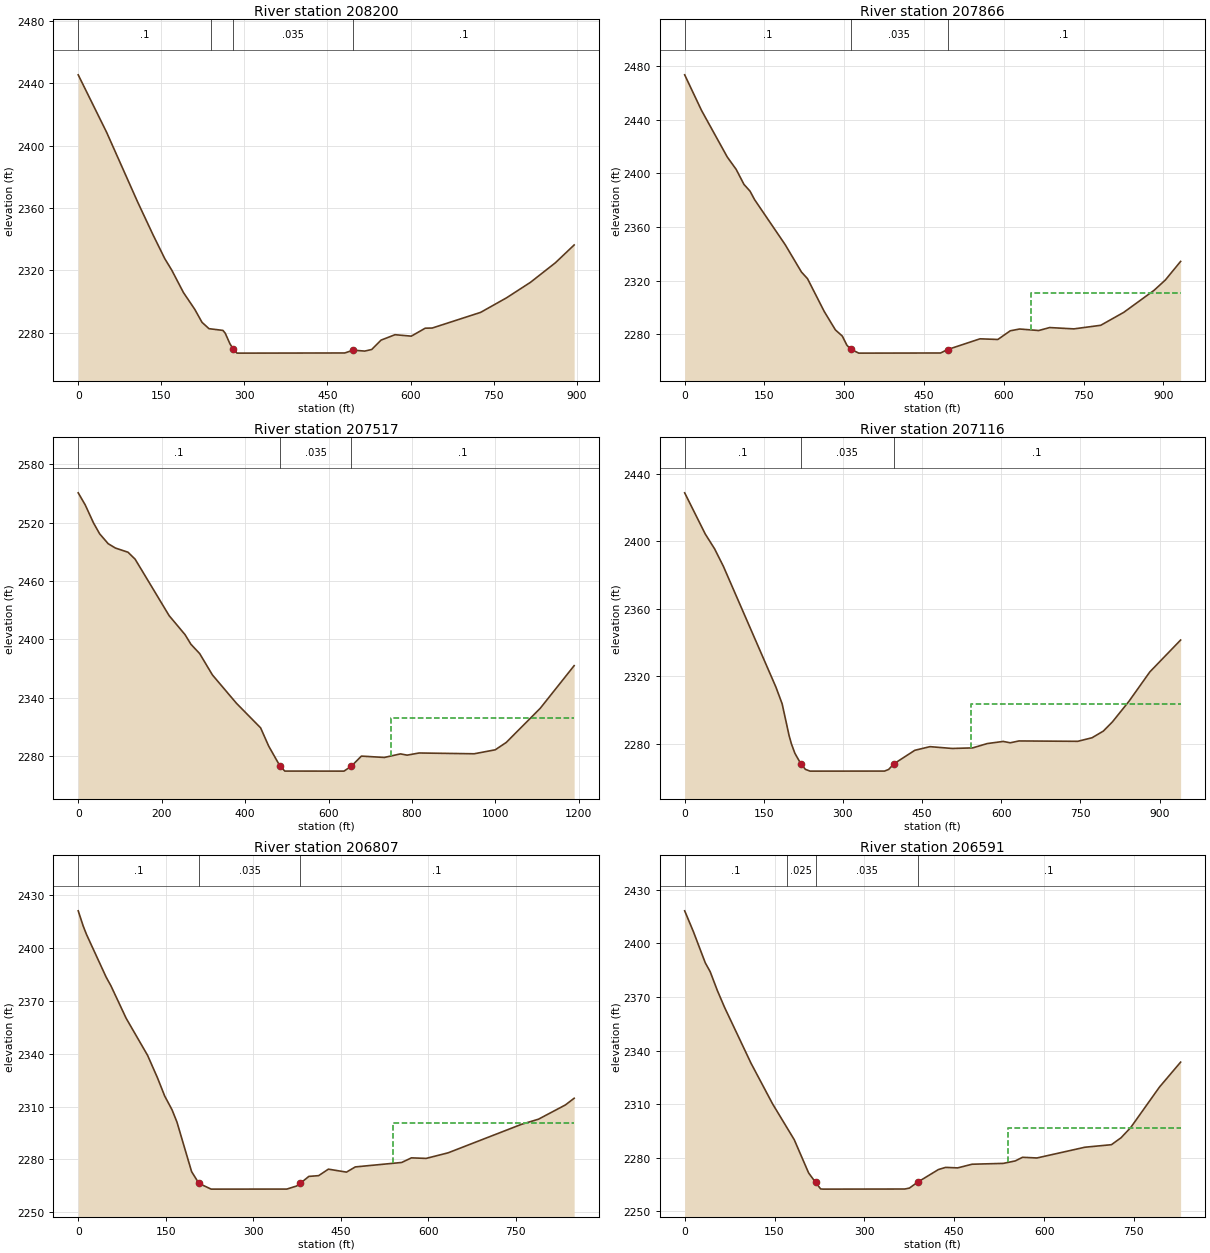
Type RM Length L Ch R = 1 ,208200  ,383.5,333.9,300.7
XS GIS Cut Line= 2
2267005.18482233482593.7416610522266152.01782233482865.040508195
#Sta/Elev= 30
       0 2445.41    51.3 2408.54     107 2364.09   135.4 2342.57   156.3 2327.51
     169 2320.09   189.9 2305.84   210.5 2294.98   223.5 2286.69   236.1 2282.62
   261.3 2281.51   265.5 2279.66   273.9 2272.94   279.4 2269.85   286.5 2266.97
   290.2 2266.94   481.2 2267.04   496.3 2268.84   517.3 2268.25   529.9 2269.29
   546.7 2275.28   571.9 2278.75   601.3 2277.83   626.5 2282.93   639.1 2283.03
   726.5 2293.08   773.4 2302.44   816.5 2312.36   861.5  2324.9   895.3  2336.3
#Mann= 4 ,-1,0
       0      .1       0     240     .12       0   279.4    .035       0
   496.3      .1       0
Bank Sta=279.4,496.3
XS Rating Curve= 0 ,0
Exp/Cntr=0.3,0.1

Type RM Length L Ch R = 1 ,207866  ,348.8,348.8,349.6
XS GIS Cut Line= 2
2266831.70307434482139.9497343092266103.94422367482723.120733856
#Sta/Elev= 30
       0 2473.57    31.8 2446.91    80.2 2412.16    96.8 2403.02   111.5 2391.78
   122.9 2386.74   131.4 2380.44   189.1 2346.75   219.6 2326.37     231 2321.41
   262.3 2297.03   283.4  2283.2   296.5 2278.53     305 2271.79   312.1 2268.79
   327.4 2265.84   481.2 2265.94   494.5 2268.53   555.4 2276.52   588.9 2276.03
   612.3 2282.52   629.9 2283.84   665.8 2282.71   686.3 2284.93   731.9 2283.94
   782.4 2286.62   825.8 2296.31   882.7 2312.72   903.9 2320.43   932.6  2334.3
#Mann= 3 ,0,0
       0      .1       0   312.1    .035       0   494.5      .1       0
#XS Ineff= 2 , 0
                           650.6         2310.98
Permanent Ineff=
       F       F
Bank Sta=312.1,494.5
XS Rating Curve= 0 ,0
Exp/Cntr(USF)=0,0
Exp/Cntr=0.3,0.1

Type RM Length L Ch R = 1 ,207517  ,441.9,401.3,341.6
XS GIS Cut Line= 3
2266732.46716526481777.9061364662266125.63240134482258.029812729
2265873.12570669482587.276673458
#Sta/Elev= 30
       0 2550.49    16.8  2538.1    36.7 2519.57    51.4 2508.42    71.8  2498.3
    89.1 2493.83   119.3 2489.55   136.4 2482.41     218 2424.41     256 2404.98
   270.2 2395.07   291.1 2385.51   321.7  2363.6   379.2 2334.54   437.2 2309.29
   456.5 2290.62   483.8 2269.95   495.2 2264.94     637 2264.88   654.6 2269.92
   678.7 2280.29   733.7 2278.91   772.4 2282.57   788.5 2281.28     817 2283.49
   949.2 2282.69   999.6 2286.77    1026 2294.34  1107.4 2329.35  1188.7 2373.13
#Mann= 3 ,0,0
       0      .1       0   483.8    .035       0   654.6      .1       0
#XS Ineff= 2 , 0
                          749.74         2319.15
Permanent Ineff=
       F       F
Bank Sta=483.8,654.6
XS Rating Curve= 0 ,0
Exp/Cntr=0.3,0.1

Type RM Length L Ch R = 1 ,207116  ,319.7,308.6,290.3
XS GIS Cut Line= 2
2266138.16406203481577.6808387222265742.10583474482430.033599022
#Sta/Elev= 30
       0 2428.67    39.1 2404.23    56.8 2395.46    73.4 2385.12   172.8 2313.73
   184.7 2303.76   197.9 2284.93   202.3 2280.02   208.9 2274.43     220  2268.3
   228.8 2264.93   237.6 2263.88   378.8 2263.91   386.6 2264.89   396.4 2268.17
   436.1 2276.21   464.9 2278.37     507  2277.3   545.8 2277.64   573.3 2280.19
   603.7 2281.47     617 2280.66   633.5 2281.75   744.9 2281.53     772 2283.64
   793.4 2287.58   810.6 2293.02   841.9 2305.18   881.6 2322.65   939.9  2341.5
#Mann= 3 ,0,0
       0      .1       0     220    .035       0   396.4      .1       0
#XS Ineff= 2 , 0
                          542.17         2303.46
Permanent Ineff=
       F       F
Bank Sta=220,396.4
XS Rating Curve= 0 ,0
Exp/Cntr=0.3,0.1

Type RM Length L Ch R = 1 ,206807  ,237.6,216.5,190.1
XS GIS Cut Line= 2
2265805.31388664481483.5261076862265554.73633634482295.582983683
#Sta/Elev= 30
       0 2421.28     8.6 2412.59    14.3 2407.78    47.8 2383.63    56.1 2378.62
    82.2 2360.15   118.9 2339.08   135.7 2326.43   148.2 2315.97   160.8 2308.13
   169.2 2301.15   194.3 2272.98   206.8 2266.31   227.8 2263.03   357.5 2263.06
   374.3 2264.81   380.62266.333   395.2 2270.27     412  2270.7   428.7 2274.39
   459.7  2272.7   474.8 2275.66   554.3 2278.19     571 2280.81   596.2  2280.5
   633.8 2283.67   759.4 2299.86   788.7  2302.8   834.8  2310.9   849.8  2314.7
#Mann= 3 ,0,0
       0      .1       0   206.8    .035       0   380.6      .1       0
#XS Ineff= 2 , 0
                          538.73         2300.83
Permanent Ineff=
       F       F
Bank Sta=206.8,380.6
XS Rating Curve= 0 ,0
Exp/Cntr(USF)=0,0
Exp/Cntr=0.3,0.1

Type RM Length L Ch R = 1 ,206591  ,503.7,497.6,490.3
XS GIS Cut Line= 2
2265528.39621489481446.8362312782265465.53980993482272.383115639
#Sta/Elev= 30
       0 2418.26    14.4 2406.74    34.4 2389.14    42.5 2384.24    54.5 2373.68
    66.5 2364.28   110.7 2332.96   146.8 2310.14   182.9 2290.12   206.9 2271.51
   218.6 2266.18     227 2262.55     231 2262.44   367.4  2262.5   375.2 2263.03
   388.8 2266.31   423.6 2273.41   435.6 2274.61   455.7 2274.33   479.7 2276.38
   531.9 2276.85   551.9 2278.24     564 2280.27     588 2279.88   668.3 2285.91
   712.4 2287.32   728.4 2291.19   744.5 2296.89   792.6 2319.59   827.9 2333.54
#Mann= 4 ,-1,0
       0      .1       0     170    .025       0   218.6    .035       0
   388.8      .1       0
#XS Ineff= 2 , 0
                          540.45         2296.68
Permanent Ineff=
       F       F
Bank Sta=218.6,388.8
XS Rating Curve= 0 ,0
Exp/Cntr=0.3,0.1

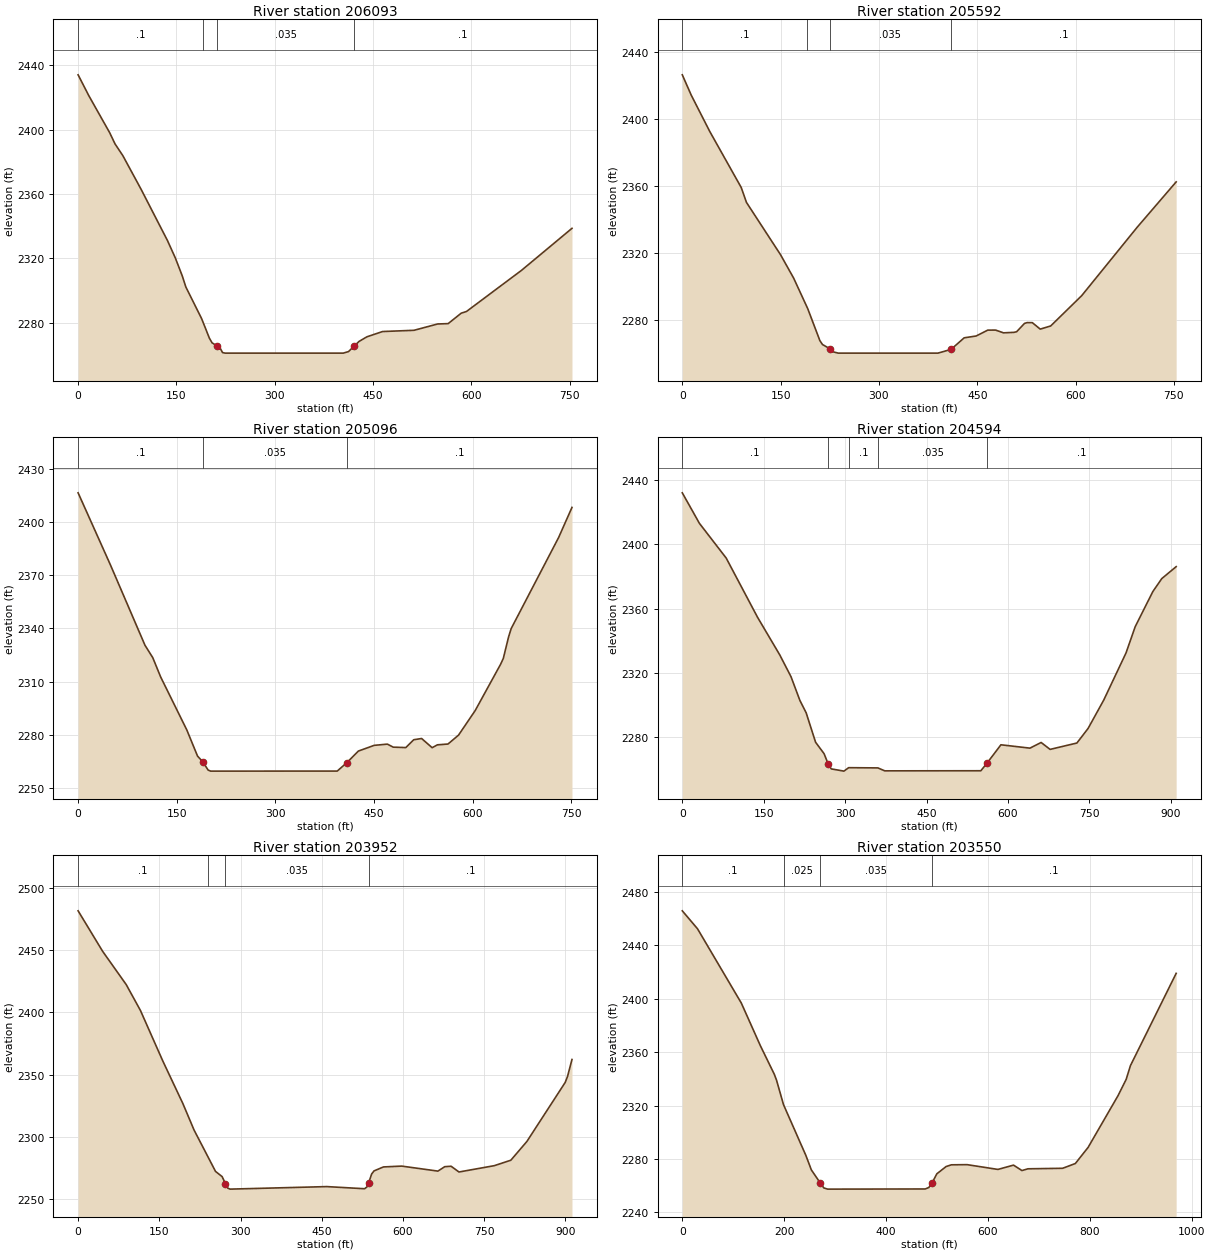
Type RM Length L Ch R = 1 ,206093  ,503.8,500.9,497.2
XS GIS Cut Line= 2
2265012.75120248481424.853838722     2265003.579      482178.143
#Sta/Elev= 30
       0 2434.19    16.3 2421.25    48.3 2398.09    56.3 2391.24    68.3 2383.88
    96.3 2362.82   136.3 2331.11   148.3 2320.29     159 2308.98   164.3 2302.26
   188.3 2282.63   200.3 2270.35   204.3 2267.52   212.3 2265.44   216.3 2264.45
   220.3 2261.44   224.3 2261.09   404.4 2261.09   412.4 2262.04   420.9 2265.36
   428.4 2268.33   440.4 2271.22   464.4 2274.52   512.4 2275.29   548.4 2279.22
   564.4 2279.44   584.4 2285.95   592.4 2286.99   676.4  2312.6   753.3 2338.71
#Mann= 4 ,-1,0
       0      .1       0     190    .025       0   212.3    .035       0
   420.9      .1       0
Bank Sta=212.3,420.9
XS Rating Curve= 0 ,0
Exp/Cntr=0.3,0.1

Type RM Length L Ch R = 1 ,205592  ,489.3,496.3,506.4
XS GIS Cut Line= 2
      2264503.78481427.269838721     2264515.048      482180.563
#Sta/Elev= 30
       0  2426.1    13.7 2413.94    41.9 2392.34    89.9 2358.94    97.9 2350.05
   149.9 2318.86   169.9 2304.91   191.5  2286.6   209.9 2267.65   213.9 2265.34
   224.9 2262.89   229.9 2261.01   237.9 2260.22     390 2260.22     410 2262.45
     430 2269.34   448.3 2270.43     466 2273.93     478 2273.95     490 2272.31
     506  2272.6     510 2272.96     522 2277.92     526 2278.41     534 2278.38
     546 2274.53     562 2276.41   609.3 2294.48     694 2335.28   753.4 2362.29
#Mann= 4 ,-1,0
       0      .1       0     190    .025       0   224.9    .035       0
     410      .1       0
Bank Sta=224.9,410
XS Rating Curve= 0 ,0
Exp/Cntr=0.3,0.1

Type RM Length L Ch R = 1 ,205096  ,476.9,502.5,524.8
XS GIS Cut Line= 2
2264030.70840496 481415.89063624     2263984.285        482165.4
#Sta/Elev= 30
       0 2416.35    49.4 2375.57   101.7 2330.54   113.5  2323.6   125.5 2312.73
   165.3 2282.88   181.6 2268.18   189.7 2264.91   197.7 2260.29   201.7 2259.72
     394 2259.75   408.8 2264.55   426.1    2271   450.1 2274.22   470.2 2274.92
   479.1 2273.22   498.2 2272.97   510.3 2277.38   522.3 2278.08   538.3  2272.9
   546.3 2274.52   562.4 2274.97   578.4 2279.97   603.7 2293.78   642.5 2319.94
   646.5 2323.15   654.5 2335.24   658.5 2339.97   730.7 2391.27   750.9 2408.14
#Mann= 3 ,0,0
       0      .1       0   189.7    .035       0   408.8      .1       0
Bank Sta=189.7,408.8
XS Rating Curve= 0 ,0
Exp/Cntr=0.3,0.1

Type RM Length L Ch R = 1 ,204594  ,600.9,641.7,658.2
XS GIS Cut Line= 2
     2263620.976       481214.52     2263406.856       482098.97
#Sta/Elev= 30
       0 2431.98    31.5 2413.04    80.9 2391.45   138.5 2354.76   179.7 2331.23
   200.3 2317.76   216.7 2302.98   228.2 2295.34   245.6 2277.03   261.3 2269.89
   268.6  2263.7   274.4 2260.48   297.8 2259.08   306.6 2261.22   360.4 2261.08
   373.1 2259.25   550.1 2259.31  561.51 2264.04   587.1 2275.44   640.6 2273.36
   661.2 2276.88   677.7 2272.58   727.1 2276.54   747.7 2285.59   776.5 2303.19
   817.6 2332.49   834.5  2348.8     867 2370.62   883.5 2378.69     910 2386.11
#Mann= 5 ,-1,0
       0      .1       0   268.6    .035       0   306.6      .1       0
   360.4    .035       0  561.51      .1       0
Bank Sta=268.6,561.51
XS Rating Curve= 0 ,0
Exp/Cntr=0.3,0.1

Type RM Length L Ch R = 1 ,203952  ,390.2,402,417.9
XS GIS Cut Line= 2
2263112.23717637480995.5751586342262750.27790495481832.817398599
#Sta/Elev= 30
       0 2481.82    45.3 2449.23    88.9 2422.43   115.1 2401.64   156.4    2361
   193.5  2326.7   214.2 2305.36   253.8  2272.1     266 2267.92     272 2262.37
   276.3 2258.69   280.6 2257.85   459.3 2259.88     529 2258.17   533.4 2259.58
   536.7 2262.99   542.1 2269.99   546.5 2272.51   563.9 2275.71   597.6 2276.38
   664.5 2272.35   677.2 2275.92   688.9 2276.26   703.4 2271.64   768.7 2276.73
   799.2 2281.11   828.8 2296.19   899.5 2343.66   903.8 2348.39   912.1 2362.19
#Mann= 4 ,-1,0
       0      .1       0     240    .025       0     272    .035       0
   536.7      .1       0
Bank Sta=272,536.7
XS Rating Curve= 0 ,0
Exp/Cntr(USF)=0,0
Exp/Cntr=0.3,0.1

Type RM Length L Ch R = 1 ,203550  ,447.3,457.3,472.8
XS GIS Cut Line= 2
2262779.28448148480842.9800756942262313.01525198481693.097206235
#Sta/Elev= 30
       0 2465.81    29.9 2452.37   115.9 2396.75   153.1 2364.99   180.7  2343.4
     185 2339.04   198.7 2320.72   242.6  2282.7   253.4 2271.85   270.5 2262.29
   277.9 2258.35   285.4 2257.47     477 2257.59   484.1 2258.72   490.7 2262.38
   499.8 2268.96     518 2274.39   528.3 2275.67   559.1 2275.79   619.7 2272.22
   650.3 2275.44   666.8 2271.37   678.6 2272.68   746.8 2273.07   771.7 2276.66
   796.7  2288.7   855.4  2327.4   871.5 2339.69   879.8 2349.89   969.6 2418.99
#Mann= 4 ,-1,0
       0      .1       0     200    .025       0   270.5    .035       0
   490.7      .1       0
Bank Sta=270.5,490.7
XS Rating Curve= 0 ,0
Exp/Cntr(USF)=0,0
Exp/Cntr=0.3,0.1

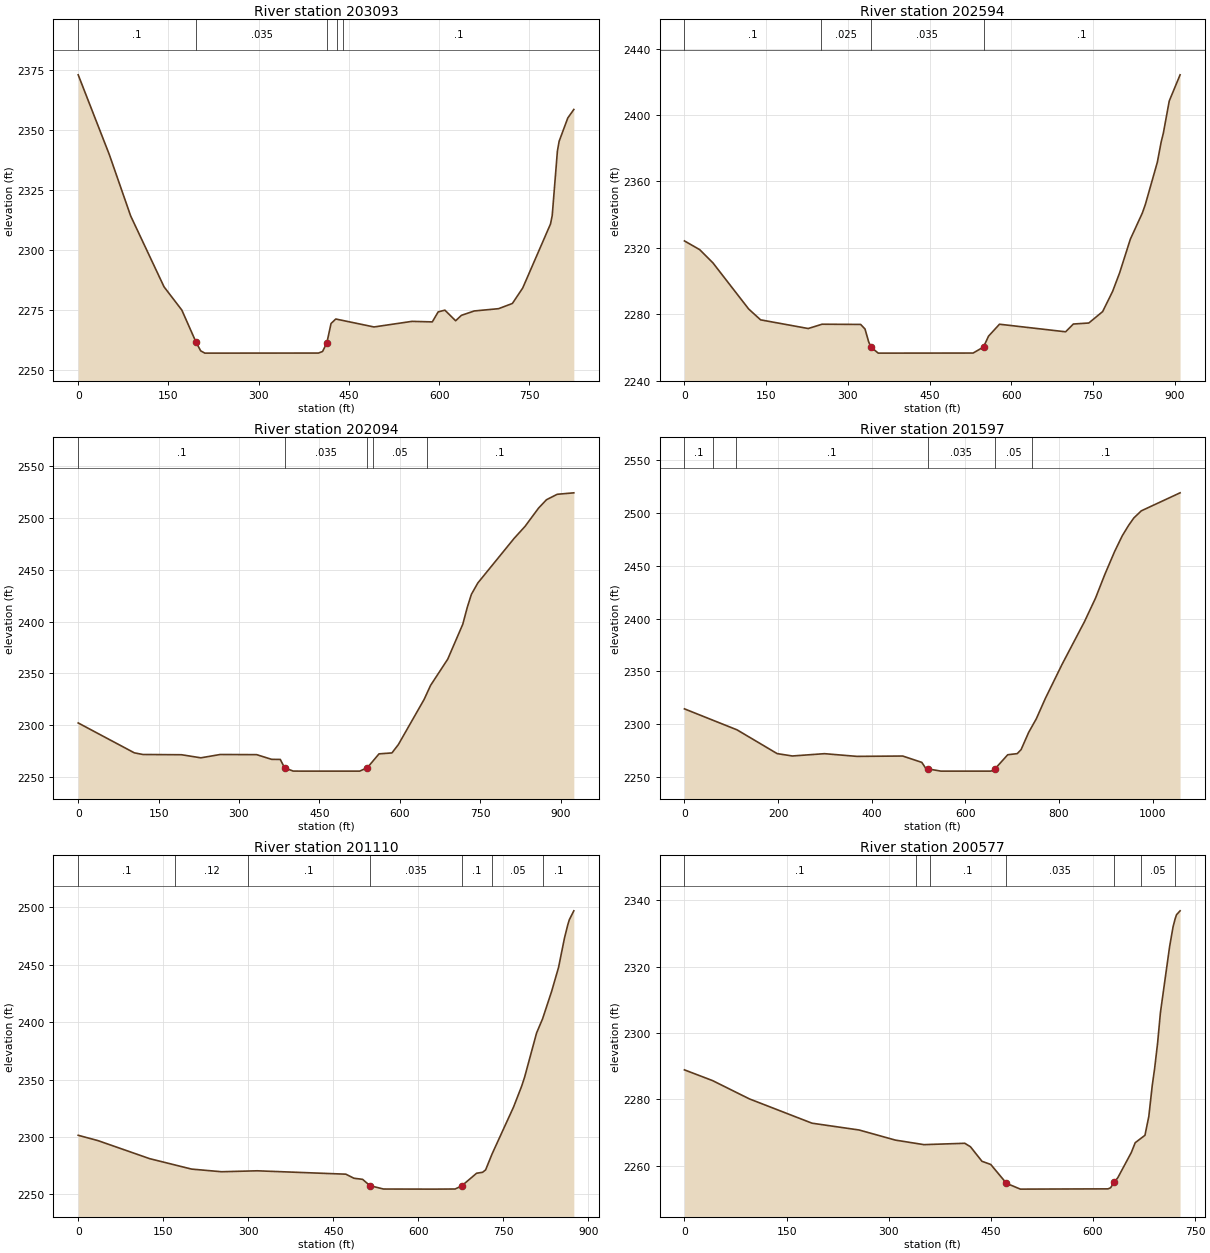
Type RM Length L Ch R = 1 ,203093  ,471.6,499,527.4
XS GIS Cut Line= 2
2262393.38669429480659.4090660152261928.41344218 481339.37793797
#Sta/Elev= 30
       0 2372.86    51.8 2339.61    87.2 2314.13   142.7 2284.61   172.2 2274.96
     196  2261.5   203.6 2257.97   210.5 2257.03   399.3 2257.06   406.1 2257.71
   413.2 2261.25   420.2 2269.35   428.1 2271.23   491.6 2267.92   554.6 2270.25
   588.5 2270.03   598.2 2274.18   609.4 2274.92   627.3  2270.5   636.9 2272.76
   658.3 2274.58   698.6 2275.53   721.6  2277.7   738.7 2284.11   784.9 2310.75
   787.8  2314.3   796.4  2341.1   799.3 2345.22   813.7 2354.91   823.7 2358.44
#Mann= 5 ,-1,0
       0      .1       0     196    .035       0   413.2      .1       0
     430    .025       0     440      .1       0
Bank Sta=196,413.2
XS Rating Curve= 0 ,0
Exp/Cntr=0.3,0.1

Type RM Length L Ch R = 1 ,202594  ,416.5,499.1,568.1
XS GIS Cut Line= 2
     2262186.296      480262.123     2261521.644      480883.684
#Sta/Elev= 30
       0 2324.14    27.9  2318.9    52.2 2310.95   117.9 2283.14   139.8  2276.6
   227.2 2271.38   252.7 2273.97   323.5 2273.84   331.5 2271.09   338.3 2263.28
   342.5 2260.14   355.8 2256.56     530 2256.61   549.1 2260.24   558.3 2266.78
   578.4 2273.97   699.8 2269.41     714 2274.09   742.4  2274.7   767.8 2281.57
   786.1 2293.74   798.9 2304.84   818.7 2325.21   840.8 2341.02   846.3 2346.18
   868.2 2371.49   875.3 2383.79   879.2 2388.94   890.1 2408.42     910 2424.18
#Mann= 4 ,-1,0
       0      .1       0     250    .025       0   342.5    .035       0
   549.1      .1       0
Bank Sta=342.5,549.1
XS Rating Curve= 0 ,0
Exp/Cntr=0.3,0.1

Type RM Length L Ch R = 1 ,202094  ,470.6,496.9,518.5
XS GIS Cut Line= 2
2262108.70078511480113.870987594     2261185.269      480163.412
#Sta/Elev= 30
       0 2302.43   104.7 2273.69   120.7 2272.09   192.8 2271.85   228.9 2268.89
   264.9 2272.08     333 2271.94     361 2267.41   377.1 2267.32   385.1 2259.26
   401.1 2256.14   417.1 2256.09   525.3 2256.09   539.7  2259.5   561.3  2272.7
   585.4 2273.59   597.4 2281.63   645.5 2325.09   657.5 2338.55   689.5 2363.77
   717.6 2397.35     726 2413.63   733.7 2426.16   745.6    2437   813.4 2479.95
   833.7 2491.45     859 2509.07   873.8 2517.13   893.8 2522.35   924.8 2523.76
#Mann= 5 ,-1,0
       0      .1       0   385.1    .035       0   539.7      .1       0
     550     .05       0     650      .1       0
Bank Sta=385.1,539.7
XS Rating Curve= 0 ,0
Exp/Cntr=0.3,0.1

Type RM Length L Ch R = 1 ,201597  ,428.6,487.1,528.4
XS GIS Cut Line= 3
2262242.73669827479871.1684585712262021.74722683479710.873835367
     2261250.969      479558.437
#Sta/Elev= 30
       0 2314.58   112.4 2294.68     198 2272.21   230.5 2269.96   299.1 2272.14
   368.4 2269.59   466.2 2269.91     507  2263.9   515.2 2258.43   519.3  2257.8
   547.8 2255.62   653.8 2255.62   660.5 2256.34   663.9 2258.05   690.5 2271.12
   710.9  2272.2   719.1 2276.01   735.3 2292.33   751.7 2305.27   770.9 2324.47
   806.8  2356.9   854.5 2397.18   878.1 2419.49     898 2441.92   918.8  2463.5
   935.2 2478.48   948.8 2488.35     960 2495.39   975.9 2502.09  1058.7 2519.13
#Mann= 6 ,-1,0
       0      .1       0      60     .12       0     110      .1       0
   519.3    .035       0   663.9     .05       0     743      .1       0
Bank Sta=519.3,663.9
XS Rating Curve= 0 ,0
Exp/Cntr=0.3,0.1

Type RM Length L Ch R = 1 ,201110  ,510.5,533.2,548.4
XS GIS Cut Line= 2
2262379.32329331479619.947470977 2261718.5600412 479047.61087594
#Sta/Elev= 30
       0 2301.45    34.8 2296.83   126.1 2281.09     200 2272.01   252.9  2269.7
   315.8 2270.52   472.1 2267.58   486.3 2264.05   501.6 2263.09   514.6 2257.57
   538.6 2254.64   627.4 2254.56   664.9 2254.67   676.3 2257.31   676.3 2257.32
   702.7 2268.38   713.3 2269.24   718.6 2271.31   730.1  2285.3   767.9 2326.07
   782.1 2344.12   787.4 2352.09   808.5 2390.56   819.1 2402.91   835.1 2426.88
   847.3 2447.75   857.7  2473.2   863.4 2484.49   866.2 2489.13   874.2 2496.95
#Mann= 7 ,-1,0
       0      .1       0     170     .12       0     300      .1       0
   514.6    .035       0   676.3      .1       0     730     .05       0
     820      .1       0
Bank Sta=514.6,676.3
XS Rating Curve= 0 ,0
Exp/Cntr=0.3,0.1

Type RM Length L Ch R = 1 ,200577  ,556.8,562.8,567
XS GIS Cut Line= 2
2262667.24570542 479312.156473062262215.67363272  478741.1099707
#Sta/Elev= 30
       0 2288.89    41.3 2285.65    95.4 2280.13   187.4  2272.8   256.5 2270.75
   309.8  2267.7   351.7 2266.33   411.8 2266.74   420.1 2265.69     437 2261.31
   449.9 2260.35     473 2254.66   493.4 2252.91   622.2 2252.99   625.9 2253.32
     631 2254.93   636.5 2256.35   656.3 2263.93   662.1 2266.92   676.4 2269.15
   682.1 2274.88   687.1 2284.15   690.6  2289.3     695 2297.02   699.1 2306.13
   712.6 2326.06   717.7 2332.06   720.8 2334.51   722.8  2335.7     728 2336.87
#Mann= 7 ,-1,0
       0      .1       0     340     .12       0     360      .1       0
     473    .035       0     631      .1       0     670     .05       0
     720      .1       0
Bank Sta=473,631
XS Rating Curve= 0 ,0
Exp/Cntr(USF)=0,0
Exp/Cntr=0.3,0.1