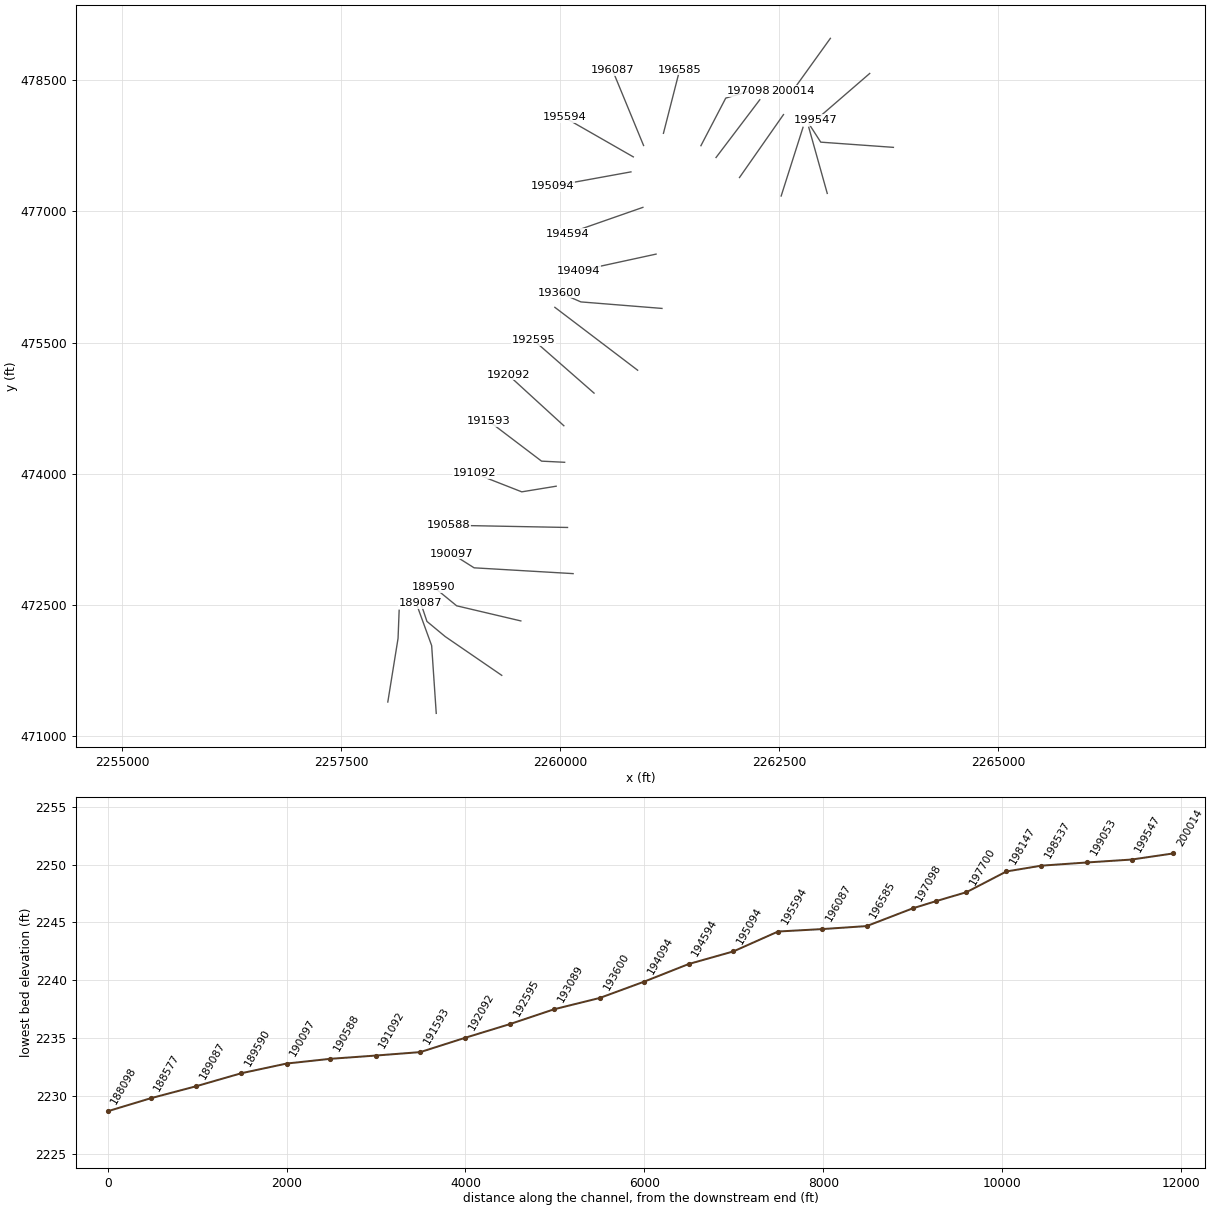
HEC-RAS study GRNBRRRV.prj: GRNBRRRV

--- GRNBRRRV.g01 (geometry) --- (continued)

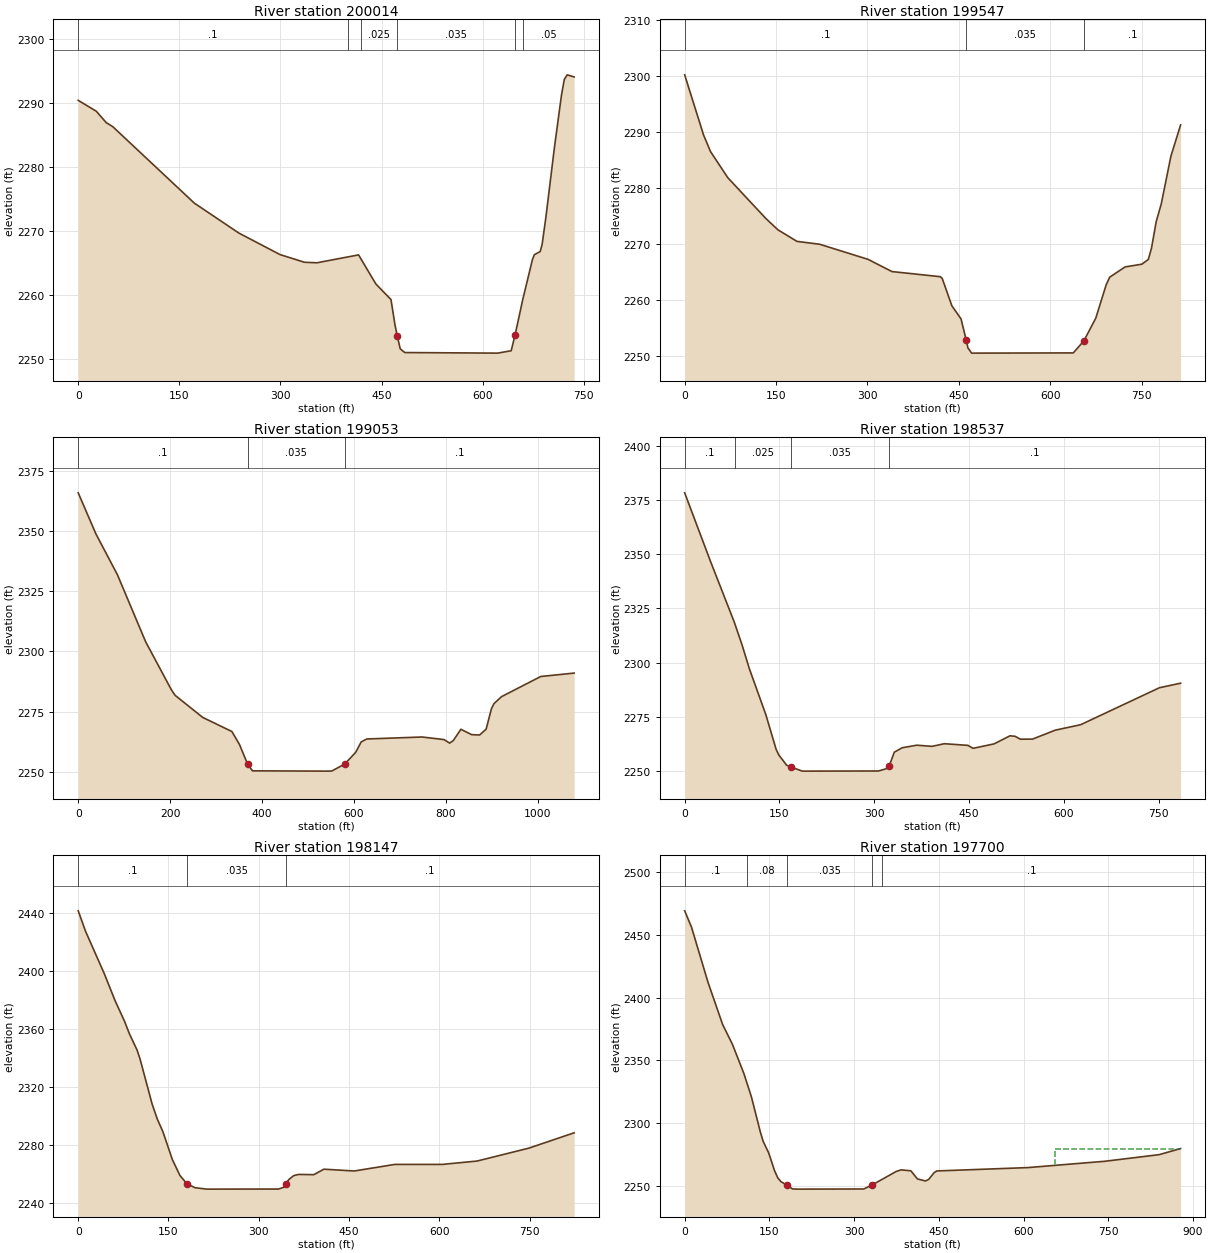
Type RM Length L Ch R = 1 ,200014  ,498.3,467.8,445.4
XS GIS Cut Line= 2
2263086.72897721 478978.949902562262657.70588602478381.292633567
#Sta/Elev= 30
       0 2290.36    26.8 2288.67    41.6 2286.89    51.4 2286.25   172.2 2274.35
   238.5 2269.67   299.3 2266.33   335.6 2265.13   354.2 2265.05   415.9 2266.28
   441.6 2261.74     464 2259.32   469.9 2255.38   473.2 2253.69   477.7 2251.64
   484.5 2251.06   622.2 2250.97   642.3 2251.34     648 2253.77   659.5 2259.34
   673.8 2265.54   676.7 2266.31   685.3  2266.8   688.2 2267.92   693.9 2272.24
   706.3  2282.9   716.8  2291.1   721.1 2293.63   725.4 2294.34   735.7 2294.01
#Mann= 6 ,-1,0
       0      .1       0     400     .12       0     420    .025       0
   473.2    .035       0     648      .1       0   659.5     .05       0
Bank Sta=473.2,648
XS Rating Curve= 0 ,0
Exp/Cntr(USF)=0,0
Exp/Cntr=0.3,0.1

Type RM Length L Ch R = 1 ,199547  ,602.1,493.3,411.6
XS GIS Cut Line= 2
2263535.96283565478577.3169827622262920.12569196478044.781481695
#Sta/Elev= 30
       0 2300.22    31.1 2289.43    42.5 2286.48    70.8 2281.82   133.2 2274.53
   153.1  2272.5   184.3 2270.43   221.8 2269.91   301.1 2267.21   340.3 2265.03
   419.7 2264.11   422.8 2263.81   438.6 2258.92   453.7 2256.56   462.2 2252.78
     465 2251.38   471.1 2250.44     638 2250.48   655.4 2252.64   674.9 2256.69
   691.9 2262.63   697.8 2264.03   723.1 2265.86   750.6 2266.35   761.2  2267.2
   766.5 2269.27   774.1 2273.95   782.4 2277.12   798.2 2285.64   814.2 2291.27
#Mann= 3 ,0,0
       0      .1       0   462.2    .035       0   655.4      .1       0
Bank Sta=462.2,655.4
XS Rating Curve= 0 ,0
Exp/Cntr(USF)=0,0
Exp/Cntr=0.3,0.1

Type RM Length L Ch R = 1 ,199053  ,660.3,516.2,376.3
XS GIS Cut Line= 3
2263806.69317418477732.4003218522262976.65180659477791.901495155
2262842.77416666478000.155601718
#Sta/Elev= 30
       0 2366.05    38.6 2348.93    85.4 2331.94   146.9 2304.01     203 2283.99
   211.1 2281.73   271.2 2272.54   334.5 2266.69   351.1 2261.29   369.1 2252.95
   379.5 2250.31   535.9 2250.19   551.9 2250.22     580 2253.11   604.1 2258.01
   616.1 2262.35   628.1 2263.57   748.4  2264.4   796.4 2263.33   808.6 2261.85
   816.6 2262.93   833.1 2267.61   856.6 2265.37     874 2265.24   888.1 2267.67
   899.6 2276.14     905 2278.27   921.8 2281.22  1007.1 2289.59  1079.7 2291.01
#Mann= 3 ,-1,0
       0      .1       0   369.1    .035       0     580      .1       0
Bank Sta=369.1,580
XS Rating Curve= 0 ,0
Exp/Cntr(USF)=0,0
Exp/Cntr=0.3,0.1

Type RM Length L Ch R = 1 ,198537  ,442.4,390.3,325.7
XS GIS Cut Line= 2
2263051.02827322477205.814938116  2262839.799108 477961.47983907
#Sta/Elev= 30
       0 2378.38    40.9  2346.7    78.3 2318.83    90.7 2308.26   102.4 2297.13
   128.4    2276   144.7 2259.96   148.9 2257.37   161.3 2252.65   167.9 2251.83
   186.2 2249.91   306.7 2249.98   319.1 2251.03   323.6 2252.37   331.6 2258.64
   344.1  2260.7   367.2 2261.88   391.3 2261.35   410.8 2262.56   447.9 2261.81
   456.4 2260.44   489.4 2262.48   514.7 2266.21   522.7 2265.99   531.1 2264.65
   550.4 2264.69   586.1 2268.81   626.5 2271.34   751.1 2288.41   784.6  2290.5
#Mann= 4 ,-1,0
       0      .1       0      80    .025       0   167.9    .035       0
   323.6      .1       0
Bank Sta=167.9,323.6
XS Rating Curve= 0 ,0
Exp/Cntr(USF)=0,0
Exp/Cntr=0.3,0.1

Type RM Length L Ch R = 1 ,198147  ,474.9,446.6,416.1
XS GIS Cut Line= 2
2262524.44288949477176.0643514642262774.34781736 477961.47983907
#Sta/Elev= 30
       0 2441.25    12.3 2427.06    43.1 2398.17    61.2  2379.4    77.1 2365.02
    85.1 2356.49    97.7 2345.38   102.6 2339.38   122.9 2307.98   131.4 2297.74
   140.8 2288.96   156.5 2269.75   169.1  2258.8   180.7 2253.08   194.3 2250.37
     214 2249.41   332.8 2249.47   341.2 2250.62   345.4 2253.01   349.6 2255.84
     358 2258.69   366.4 2259.55   391.5 2259.37   408.3 2263.16   458.7 2261.91
   526.1 2266.44   605.7 2266.47     663 2268.78     749 2277.67   824.2 2288.24
#Mann= 3 ,0,0
       0      .1       0   180.7    .035       0   345.4      .1       0
Bank Sta=180.7,345.4
XS Rating Curve= 0 ,0
Exp/Cntr(USF)=0,0
Exp/Cntr=0.3,0.1

Type RM Length L Ch R = 1 ,197700  ,346,342.7,338.6
XS GIS Cut Line= 2
2262048.43350306477387.2935166922262551.21841747478107.257713664
#Sta/Elev= 30
       0 2469.08    12.1  2456.1    41.3 2412.21    67.2 2378.64    84.5 2362.91
   104.8 2339.67   118.3 2320.83     134 2293.03   138.9 2285.71   148.7 2276.52
   159.2 2262.23   164.9 2256.54   170.4 2253.59   181.2 2250.76   190.8  2247.8
   199.4 2247.62   317.2 2247.74   332.1    2251   374.6  2261.7   383.2 2262.94
   400.5 2262.21   412.1 2255.75   426.3 2254.11   432.1 2255.37   441.4 2260.64
   446.4 2262.08   607.4 2264.75   743.9 2269.78     840 2275.05   878.1  2279.9
#Mann= 5 ,-1,0
       0      .1       0     110     .08       0   181.2    .035       0
   332.1    .025       0     350      .1       0
#XS Ineff= 2 , 0
                          655.21         2279.52
Permanent Ineff=
       F       F
Bank Sta=181.2,332.1
XS Rating Curve= 0 ,0
Exp/Cntr(USF)=0,0
Exp/Cntr=0.3,0.1

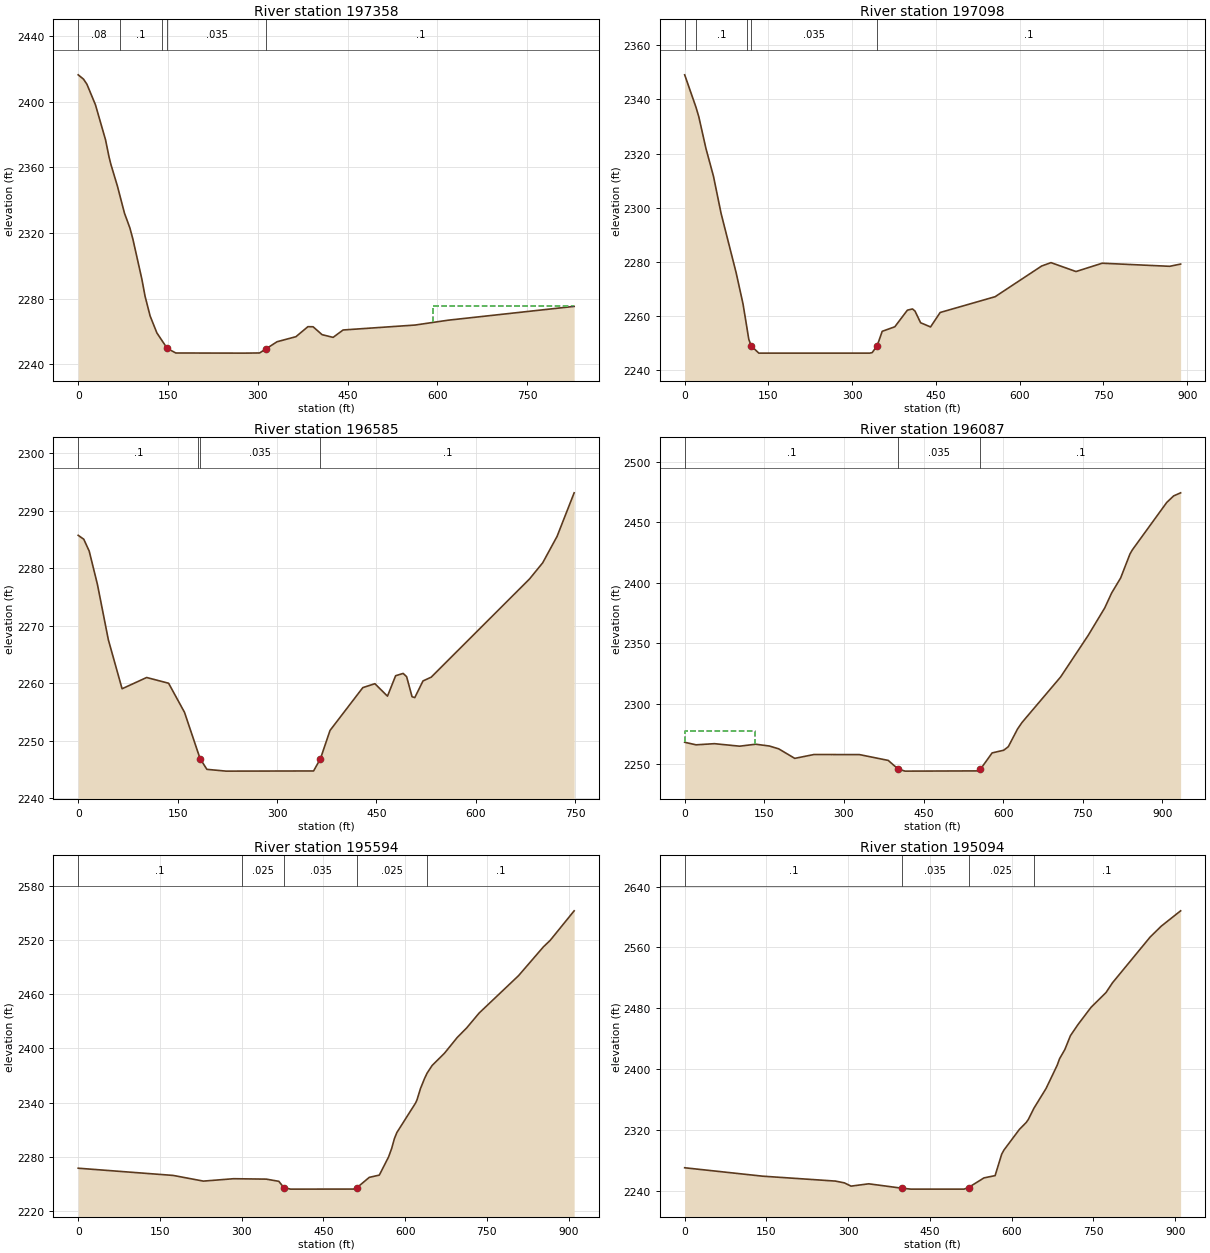
Type RM Length L Ch R = 1 ,197358  ,237.8,259.2,281.8
XS GIS Cut Line= 2
2261780.67822319 477616.373033912262280.48807894478276.836057579
#Sta/Elev= 30
       0  2416.3     8.8 2413.68    14.5 2410.61    28.8 2398.06    45.6 2376.78
    51.6 2366.11    54.5 2361.87    65.5 2348.52    77.3 2332.03    86.3 2323.07
    91.3  2316.3   106.4 2291.75   111.6 2281.57   120.1 2269.46   131.4 2259.14
   148.7 2249.71     163 2246.92   276.9 2246.84   302.9 2246.94   314.3 2249.58
   332.1 2253.77   363.7 2256.86   383.6 2262.94   392.3 2262.89   407.3 2258.08
   425.7 2256.43   442.4 2260.93   562.7 2263.94     618  2266.9   828.3  2275.3
#Mann= 5 ,-1,0
       0     .08       0      70      .1       0     140    .025       0
   148.7    .035       0   314.3      .1       0
#XS Ineff= 2 , 0
                          592.68         2275.28
Permanent Ineff=
       F       F
Bank Sta=148.7,314.3
XS Rating Curve= 0 ,0
Exp/Cntr(USF)=0,0
Exp/Cntr=0.3,0.1

Type RM Length L Ch R = 1 ,197098  ,483.7,513.9,538.1
XS GIS Cut Line= 3
2261607.89712721477751.3813165082261891.47254423478295.616965324
2262154.99717418478372.955715419
#Sta/Elev= 30
       0 2349.09    20.1 2337.21    25.3  2333.6    38.1 2321.86    51.6 2311.59
    65.2 2297.87    92.2 2275.92   104.5  2264.4   111.3 2255.85   114.8 2251.35
   119.3 2248.85   132.8 2246.22   331.3 2246.22   335.8  2246.4   344.8 2248.96
   353.8 2254.28   376.4 2255.96   398.9  2262.1     408 2262.55   412.5 2261.78
   422.6 2257.45   440.4  2255.9   457.6 2261.24   556.1 2267.08   639.4 2278.42
   656.1 2279.67   700.9 2276.38   747.8 2279.45   868.7 2278.31   888.3 2279.14
#Mann= 5 ,-1,0
       0     .06       0    20.1      .1       0   111.3    .025       0
   119.3    .035       0   344.8      .1       0
Bank Sta=119.3,344.8
XS Rating Curve= 0 ,0
Exp/Cntr(USF)=0,0
Exp/Cntr=0.3,0.1

Type RM Length L Ch R = 1 ,196585  ,421.8,497.7,551.5
XS GIS Cut Line= 2
2261179.71637283477893.053489771     2261365.045      478618.178
#Sta/Elev= 30
       0 2285.74     8.4 2285.06    16.6 2282.99      29  2277.2    45.5 2267.55
    66.2 2259.03   103.3 2260.99   136.4 2259.99   160.4 2254.93   181.3 2247.76
  184.05 2246.84   194.2    2245   223.1 2244.69   355.2 2244.72   365.6 2246.87
     380 2251.77   429.5 2259.23   447.7 2259.91   466.7 2257.74     479  2261.3
   490.4  2261.7   495.6 2261.13   503.8 2257.64   507.9 2257.49   520.3 2260.39
   532.7 2261.05   681.1 2278.15   700.9 2280.95   722.6 2285.55   748.4 2293.14
#Mann= 4 ,-1,0
       0      .1       0   181.3    .025       0  184.05    .035       0
   365.6      .1       0
Bank Sta=184.05,365.6
XS Rating Curve= 0 ,0
Exp/Cntr=0.3,0.1

Type RM Length L Ch R = 1 ,196087  ,420.7,493.3,545.5
XS GIS Cut Line= 2
      2260952.87      477753.4212260597.13947471478617.349354683
#Sta/Elev= 30
       0 2268.25    21.4 2266.14      56 2267.09   103.6 2265.02   133.8 2266.65
   159.7 2265.14   177.1 2262.83   207.4 2254.96   243.5 2258.13   329.2 2258.08
   383.4 2253.28     402 2246.23     415 2244.43   553.4 2244.62   557.2 2246.03
   579.2 2259.47     601 2261.67   609.7  2264.6     627 2279.15   635.6 2284.64
   708.2 2322.15   760.3 2356.58   791.4 2379.19   804.3 2391.44   821.3 2403.86
   838.9 2423.69   843.3 2427.03   908.2 2466.24   921.1 2471.59   934.3 2474.16
#Mann= 3 ,-1,0
       0      .1       0     402    .035       0   557.2      .1       0
#XS Ineff= 2 , 0
          132.76 2277.45
Permanent Ineff=
       F       F
Bank Sta=402,557.2
XS Rating Curve= 0 ,0
Exp/Cntr=0.3,0.1

Type RM Length L Ch R = 1 ,195594  ,438.1,500,555.9
XS GIS Cut Line= 2
     2260835.517      477623.455     2260045.954      478075.883
#Sta/Elev= 30
       0 2267.37   174.4 2259.38   229.7 2253.09   285.1 2255.75     345 2255.29
   368.1 2252.87   377.3 2245.92   389.7 2244.22   506.4 2244.28   511.8    2246
     534 2257.23   552.5 2259.75   569.4 2279.77   575.2  2289.3   580.1    2300
   584.7 2306.88   619.2 2339.75   621.6 2342.99     628 2355.52   635.4 2366.58
   640.1 2372.56   649.3 2381.05   672.3 2394.85   695.4 2412.09     713 2422.83
   735.6 2439.14     808 2480.58   853.6 2512.47   865.9 2519.55     910 2552.35
#Mann= 5 ,-1,0
       0      .1       0     300    .025       0   377.3    .035       0
   511.8    .025       0     640      .1       0
Bank Sta=377.3,511.8
XS Rating Curve= 0 ,0
Exp/Cntr=0.3,0.1

Type RM Length L Ch R = 1 ,195094  ,488.5,500,516.1
BEGIN DESCRIPTION:
c/e coefficient of 0.5/0.7 to correct drawdown and capture contraction of river at this location
END DESCRIPTION:
XS GIS Cut Line= 2
     2260808.503       477452.02     2259913.239      477288.917
#Sta/Elev= 30
       0 2270.57   142.6 2259.54   276.8 2253.05   293.1 2250.71   305.3 2246.44
   337.8 2249.48   398.8 2243.69     415  2242.5   512.6  2242.5   520.8  2244.6
   549.2 2257.27   569.6 2260.24   581.7 2288.45   585.8 2293.82   614.3  2321.1
   626.5 2329.88   630.5 2333.92   640.7 2348.62   663.1 2374.72   683.4 2405.05
   687.9 2413.84   697.5 2425.78   707.8 2444.06   721.5 2458.53   745.6 2481.31
   773.1 2500.76     785 2513.58   854.2 2573.75   874.5 2587.98     910 2608.11
#Mann= 4 ,-1,0
       0      .1       0   398.8    .035       0   520.8    .025       0
   640.7      .1       0
Bank Sta=398.8,520.8
XS Rating Curve= 0 ,0
Exp/Cntr=0.7,0.5

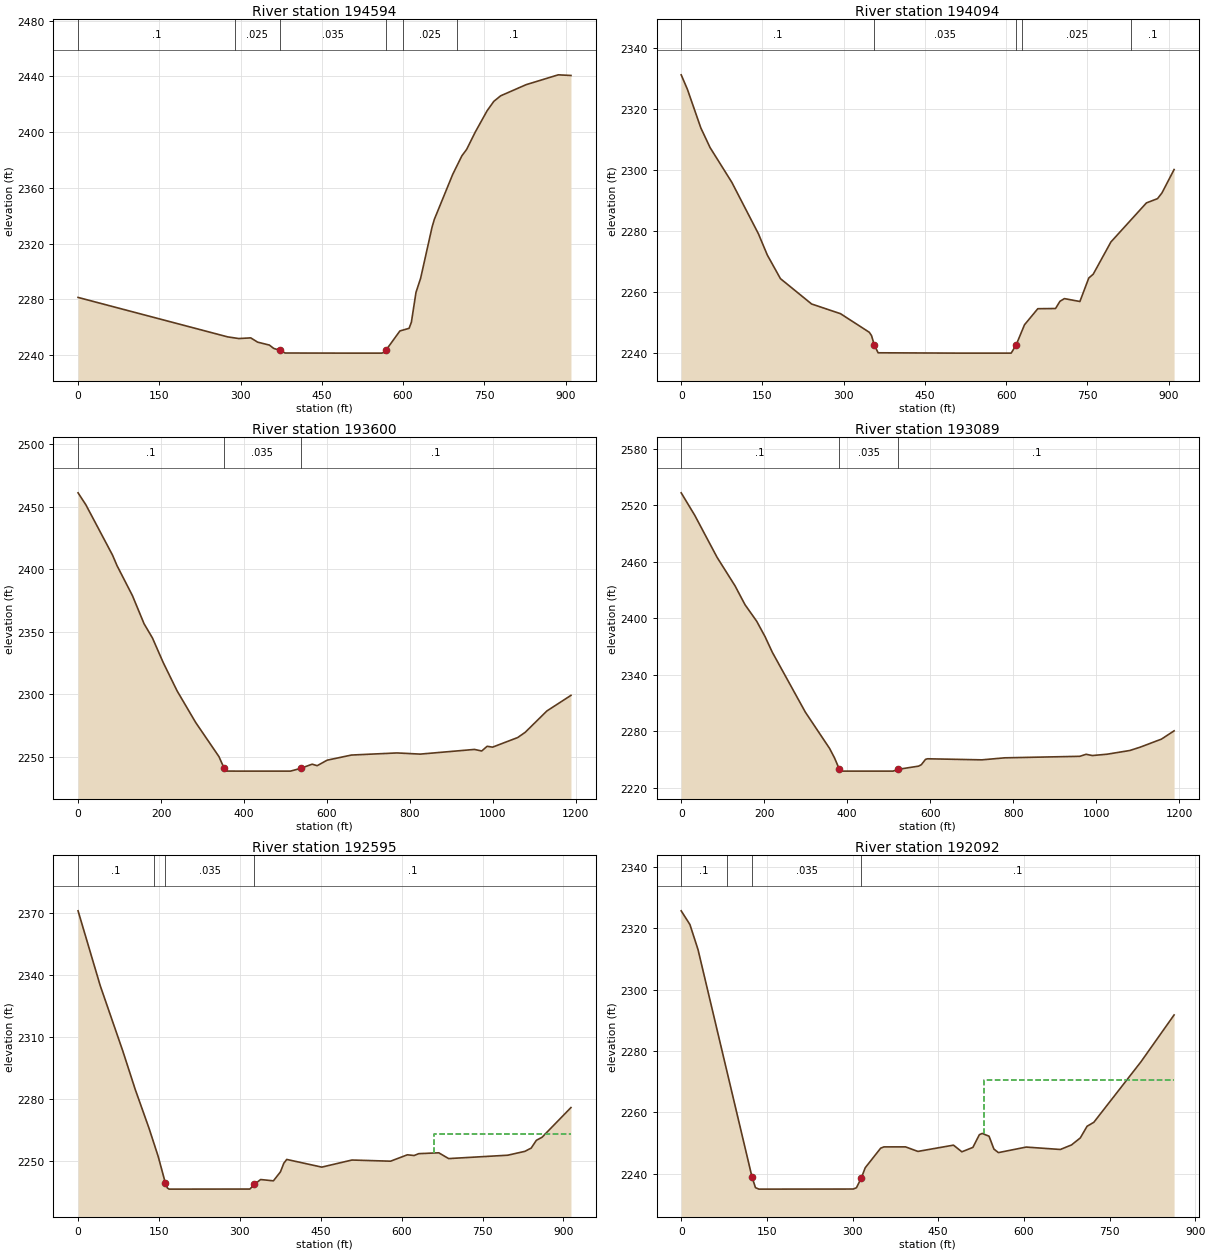
Type RM Length L Ch R = 1 ,194594  ,513.7,500,483.2
XS GIS Cut Line= 2
     2260945.098       477046.22     2260086.091      476745.875
#Sta/Elev= 30
       0 2281.38   276.4 2253.05   296.7 2251.88   318.8 2252.35   331.5  2249.3
   353.2 2247.19   361.2 2244.79     372 2243.53   382.3 2241.49   496.8 2241.41
   560.4 2241.41   564.6 2241.83   568.8 2243.71   594.2 2257.32   611.2 2259.22
   615.4 2263.63   623.9 2285.03   632.4 2295.06   653.5 2331.72   657.7 2337.34
   691.7 2369.69   708.6 2382.99   717.4  2387.6   733.1 2399.87   755.2 2415.34
   767.6 2422.08   780.2 2426.05   827.3 2434.06   886.6 2441.11     910 2440.64
#Mann= 6 ,-1,0
       0      .1       0     290    .025       0     372    .035       0
   568.8     .12       0     600    .025       0     700      .1       0
Bank Sta=372,568.8
XS Rating Curve= 0 ,0
Exp/Cntr=0.3,0.1

Type RM Length L Ch R = 1 ,194094  ,528.5,493.2,462.5
XS GIS Cut Line= 2
     2261095.531      476511.754     2260206.281      476318.532
#Sta/Elev= 30
       0 2331.09    11.6 2326.29    36.2 2313.72    53.3 2307.26    93.5 2295.86
   142.6 2278.99     159 2272.04   183.2  2264.3   240.8 2255.98   294.1 2252.81
   347.3 2246.71   351.4 2245.63   356.6 2242.48   363.6 2239.99   515.1 2239.88
   609.2 2239.88   618.1 2242.44   633.8 2249.16   658.4 2254.44   691.1  2254.5
   699.3 2256.87   707.5 2257.75   736.1  2256.8   752.5  2264.5   760.7 2265.75
   793.4 2276.32   858.9 2289.11   879.4 2290.51   887.6 2292.38     910 2300.05
#Mann= 5 ,-1,0
       0      .1       0   356.6    .035       0   618.1      .1       0
     630    .025       0     830      .1       0
Bank Sta=356.6,618.1
XS Rating Curve= 0 ,0
Exp/Cntr=0.3,0.1

Type RM Length L Ch R = 1 ,193600  ,574.5,511.8,456.7
XS GIS Cut Line= 3
      2261162.87      475890.7312260236.62277597475965.215474738
 2259998.9489548476069.023346607
#Sta/Elev= 30
       0 2461.08    18.8 2451.52      83 2411.34    93.9 2402.89   131.1 2378.86
   159.2 2356.34   179.3 2345.03   205.3 2325.37   238.8 2302.68   283.6  2277.4
   339.8 2250.07   351.8 2241.16   355.8 2238.53   391.1 2238.48   512.3 2238.49
   536.4 2240.65   564.5 2244.03   576.6 2242.83   600.6 2247.23   659.2 2251.34
   769.2 2253.03     825 2252.09   955.9 2255.84   973.4 2254.58   986.5 2258.36
   999.6 2257.67  1060.2 2265.35  1078.4 2269.57  1130.5 2286.59  1188.6 2299.09
#Mann= 3 ,-1,0
       0      .1       0   351.8    .035       0   536.4      .1       0
Bank Sta=351.8,536.4
XS Rating Curve= 0 ,0
Exp/Cntr=0.3,0.1

Type RM Length L Ch R = 1 ,193089  ,500.2,493.6,487.4
XS GIS Cut Line= 2
     2260884.959      475184.1052259939.35365878475903.188343915
#Sta/Elev= 30
       0 2532.99    32.7 2509.13    86.4 2464.59   129.8 2434.24   153.8 2414.23
   181.9 2396.72     202 2380.42   219.8  2363.6   299.1 2300.24   357.8 2261.51
   369.6  2251.5     381 2239.73   383.8 2237.79   387.9  2237.5   510.6 2237.51
   523.6 2239.45   572.2  2242.8   578.9 2244.36   588.9 2250.01     594 2250.61
   724.6 2249.47   779.9 2251.62   960.8 2253.22   975.9 2255.37   990.9 2254.05
    1026 2255.43  1081.4 2259.41    1106  2262.9  1157.4 2271.46    1188 2280.26
#Mann= 3 ,-1,0
       0      .1       0     381    .035       0   523.6      .1       0
Bank Sta=381,523.6
XS Rating Curve= 0 ,0
Exp/Cntr=0.3,0.1

Type RM Length L Ch R = 1 ,192595  ,506.5,503.1,500.9
XS GIS Cut Line= 2
2260387.06683208474922.4257572632259699.86283208475524.908874594
#Sta/Elev= 30
       0 2370.99    41.1 2334.75    83.1    2303     106  2284.5   131.6 2265.68
   148.6 2252.03   161.9 2239.13   165.6 2236.77   168.8 2236.22   318.6 2236.26
   327.1 2238.55   338.5 2240.87   362.2 2240.23   375.3  2244.6   381.5 2248.77
   386.9  2250.6   451.9 2246.88   507.8 2250.31   579.4 2249.75   610.6 2252.84
   623.1 2252.49   631.6 2253.39   668.8 2253.81   687.1 2251.01   796.5 2252.64
   828.4 2254.51   840.2  2256.1   849.7 2259.85   860.3 2261.34   913.9 2275.72
#Mann= 4 ,-1,0
       0      .1       0     140    .025       0   161.9    .035       0
   327.1      .1       0
#XS Ineff= 2 , 0
                          660.78         2262.77
Permanent Ineff=
       F       F
Bank Sta=161.9,327.1
XS Rating Curve= 0 ,0
Exp/Cntr=0.3,0.1

Type RM Length L Ch R = 1 ,192092  ,486.5,498.6,508.1
XS GIS Cut Line= 2
2260041.94165608474549.318874594 2259405.2214774475132.076405272
#Sta/Elev= 30
       0 2325.64    15.3 2321.17    29.5 2313.01   124.2 2238.84   130.1 2235.51
   136.1 2235.03   301.3 2235.06   306.9 2235.48   315.4 2238.67   322.3    2242
   349.3 2248.36   354.9 2248.78   392.8 2248.79   414.5 2247.31   476.8 2249.35
   491.5 2247.18   510.8 2248.62   522.1 2252.75   527.1 2253.16   539.1 2252.26
   547.6 2248.07   555.5 2246.92   604.1 2248.72   663.9 2247.94   683.5 2249.42
   698.9 2251.71   710.7 2255.49   722.6  2256.8   805.2 2276.52   863.1 2291.74
#Mann= 4 ,-1,0
       0      .1       0      80    .025       0   124.2    .035       0
   315.4      .1       0
#XS Ineff= 2 , 0
                          529.58         2270.65
Permanent Ineff=
       F       F
Bank Sta=124.2,315.4
XS Rating Curve= 0 ,0
Exp/Cntr=0.3,0.1

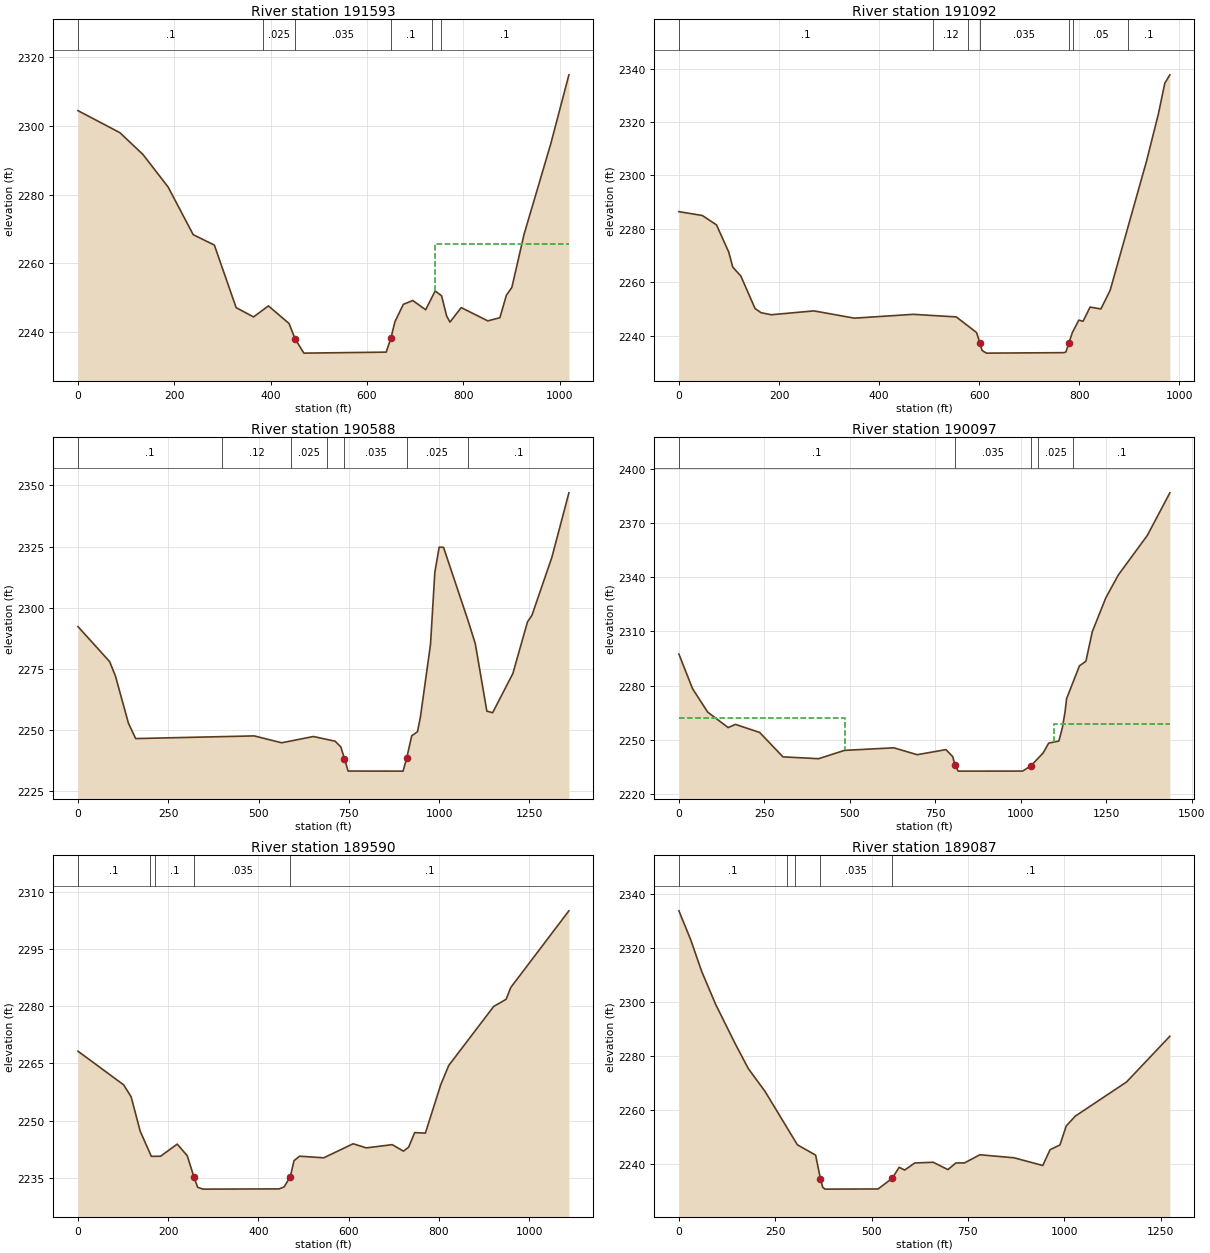
Type RM Length L Ch R = 1 ,191593  ,468.2,501.1,529.8
XS GIS Cut Line= 3
2260051.06475726 474131.389583962259787.38891753474144.479571651
     2259186.154      474600.931
#Sta/Elev= 30
       0 2304.45      87 2298.03   135.1 2291.64   187.1  2282.2   239.2 2268.31
   283.1 2265.28   328.3 2247.05   364.4 2244.35   395.3 2247.56   438.1 2242.43
   450.4 2238.02   468.9  2233.8   639.7 2234.09   649.3  2238.1   657.9 2242.96
   675.3 2248.02   694.9 2249.13   721.6 2246.44   741.4 2251.92   754.7 2250.49
   765.2  2244.6   772.1 2242.84   795.4 2247.06   850.6  2243.2   875.7 2244.12
   889.1 2250.65   900.6 2252.97   925.9 2268.44   981.2 2294.74  1018.9 2314.88
#Mann= 6 ,-1,0
       0      .1       0     384    .025       0   450.4    .035       0
   649.3      .1       0     734     .05       0     754      .1       0
#XS Ineff= 2 , 0
                          741.63         2265.48
Permanent Ineff=
       F       F
Bank Sta=450.4,649.3
XS Rating Curve= 0 ,0
Exp/Cntr=0.3,0.1

Type RM Length L Ch R = 1 ,191092  ,463.7,504.6,541.1
XS GIS Cut Line= 3
2259954.31275188473857.9142879422259561.28445897 473793.42264916
2259018.72610925474006.279885362
#Sta/Elev= 30
       0 2286.45    46.8 2285.01    75.1  2281.5    99.5 2271.37   107.6 2265.69
   123.8 2262.35   152.1  2250.2   164.3 2248.62   184.6 2247.87   269.7 2249.31
   350.7 2246.59   468.2 2248.02   554.2 2247.06   594.8 2241.22   601.4 2237.33
   605.7 2234.54   614.3  2233.5     769 2233.68   773.3 2233.91  779.39 2237.35
   786.2 2241.18   799.1 2245.84   807.7 2245.43   821.7 2250.74   843.3 2250.03
   861.9 2257.08   934.3 2305.23   958.1 2322.93     971 2334.53   981.1 2337.66
#Mann= 7 ,-1,0
       0      .1       0  508.28     .12       0  578.28    .025       0
   601.4    .035       0  779.39      .1       0  788.28     .05       0
  898.28      .1       0
Bank Sta=601.4,779.39
XS Rating Curve= 0 ,0
Exp/Cntr=0.3,0.1

Type RM Length L Ch R = 1 ,190588  ,495.3,490.1,487.1
XS GIS Cut Line= 2
2260083.96750914473386.133824005 2258725.0976507473411.855824004
#Sta/Elev= 30
       0 2292.32    87.8 2277.98   103.8 2272.09   139.8 2252.79   159.8 2246.53
   487.9 2247.62   563.9 2244.81   651.9 2247.37   711.9 2245.46   727.9 2243.09
  737.84 2238.25   747.9 2233.25     900 2233.22   909.8 2238.41     924 2247.66
     940 2249.34     948 2255.29     976 2285.07     988 2314.56    1000 2324.78
    1012 2324.74    1080 2294.74    1100  2285.3    1132 2257.76    1148  2257.1
    1204 2273.13  1244.5 2294.25  1256.8 2296.93    1312 2320.64  1359.1    2347
#Mann= 7 ,-1,0
       0      .1       0     400     .12       0     590    .025       0
     690     .12       0  737.84    .035       0   909.8    .025       0
    1080      .1       0
Bank Sta=737.84,909.8
XS Rating Curve= 0 ,0
Exp/Cntr=0.3,0.1

Type RM Length L Ch R = 1 ,190097  ,534.5,507.7,490.7
XS GIS Cut Line= 3
2260148.00021043472858.4085306792259016.84872325472924.705518929
2258760.52976534473086.406991924
#Sta/Elev= 30
       0 2297.49    39.9 2278.37      84 2265.47   144.1 2256.89   165.2 2258.65
   236.2  2254.2   304.3  2240.7   408.5 2239.68   484.7 2244.29   628.9 2245.69
     697 2241.89   781.2  2244.7   801.2 2240.77  807.42 2236.04   817.2 2232.81
  1005.5 2232.84  1029.6 2235.71  1065.7 2242.89  1081.7 2248.29  1111.5 2249.44
  1121.7 2256.76  1129.8 2265.79    1134 2272.81  1171.7 2291.01  1190.6 2293.55
  1209.3 2309.89    1249 2328.66  1285.2 2341.18  1370.4 2363.14  1436.2 2386.65
#Mann= 5 ,-1,0
       0      .1       0  807.42    .035       0  1029.6      .1       0
    1050    .025       0 1153.09      .1       0
#XS Ineff= 2 , 0
          486.76 2262.06 1097.01         2259.12
Permanent Ineff=
       F       F
Bank Sta=807.42,1029.6
XS Rating Curve= 0 ,0
Exp/Cntr=0.3,0.1

Type RM Length L Ch R = 1 ,189590  ,556.2,502.7,465.1
XS GIS Cut Line= 3
2259550.41594403472317.5840586652258817.51979268472490.346953814
2258558.05489075472702.852754571
#Sta/Elev= 30
       0 2268.22   101.3 2259.38   117.9 2256.23   137.9 2247.23   162.6 2240.59
   183.1 2240.61   220.1  2243.8   242.3 2240.74   257.1 2235.18   265.3 2232.46
   277.2 2231.97   446.1 2232.03   457.1 2232.56   470.8 2235.23     479 2239.45
   491.3 2240.63   544.8  2240.2   610.1 2243.89   639.3 2242.81   696.8 2243.66
   721.5 2241.95   733.2 2243.01   746.5 2246.83   770.2 2246.69   804.3 2259.41
   821.9 2264.45   921.6 2279.97   949.2 2281.86   959.5 2284.96  1088.4 2305.11
#Mann= 5 ,-1,0
       0      .1       0     160     .12       0     170      .1       0
   257.1    .035       0   470.8      .1       0
Bank Sta=257.1,470.8
XS Rating Curve= 0 ,0
Exp/Cntr=0.3,0.1

Type RM Length L Ch R = 1 ,189087  ,587.7,509.7,401.7
XS GIS Cut Line= 4
     2259332.699      471695.1172258686.21572674472138.983274125
 2258477.9731776472311.9044929372258408.33836024472519.805651859
#Sta/Elev= 30
       0 2333.76    30.6 2323.06    59.4 2311.23    95.5 2299.13   146.2 2284.57
   180.2 2275.41   223.4 2267.01   307.5 2247.24   354.8 2243.42   367.2 2234.71
     373 2231.63   378.7 2230.85   516.8 2230.91   553.8 2234.87   571.5 2238.92
   585.9 2237.91     612 2240.51   659.7 2240.79   698.1 2238.08   718.7 2240.52
   741.2 2240.54     781 2243.56   869.6 2242.44   944.2 2239.59   963.3 2245.44
   988.9 2247.19  1005.2 2254.23  1028.6 2257.83  1161.7 2270.47  1274.1 2287.39
#Mann= 5 ,-1,0
       0      .1       0     280     .12       0     300    .025       0
   367.2    .035       0   553.8      .1       0
Bank Sta=367.2,553.8
XS Rating Curve= 0 ,0
Exp/Cntr=0.3,0.1

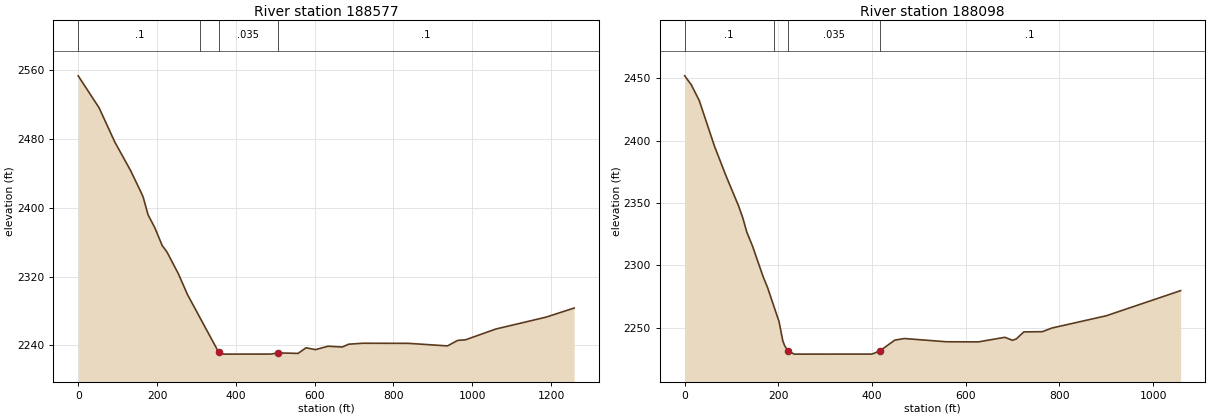
Type RM Length L Ch R = 1 ,188577  ,501.1,479,452
XS GIS Cut Line= 3
2258584.33770667471260.4158213122258531.91416082472035.162978042
2258367.07812271472488.215215817
#Sta/Elev= 30
       0 2553.36    52.9 2516.24      93  2476.3   133.1  2443.1   161.1 2416.35
   165.1 2411.99   177.2 2391.86   194.2 2376.99   213.2 2356.02   225.3 2348.53
   254.4 2323.02   277.4 2298.97  356.57 2231.94   369.6 2229.81   489.9  2229.9
   505.9 2231.25     558 2230.66   578.1 2237.16   602.1 2235.06   634.2 2238.99
   670.3 2238.08   686.3 2241.35   722.4 2242.47   838.3 2242.34   937.1 2239.38
   962.9 2245.74     983 2246.47  1059.6 2258.96  1187.3 2272.81  1258.6  2283.4
#Mann= 4 ,-1,0
       0      .1       0     310    .025       0  356.57    .035       0
   505.9      .1       0
Bank Sta=356.57,505.9
XS Rating Curve= 0 ,0
Exp/Cntr=0.3,0.1

Type RM Length L Ch R = 1 ,188098  ,503.6,504.6,505.3
XS GIS Cut Line= 3
2258030.99776265471390.3526399332258148.13159302472118.464620667
     2258160.581472439.364690522
#Sta/Elev= 30
       0 2451.87      14 2444.77    31.2 2431.99    63.6 2395.47    87.9 2371.97
   115.2 2347.39   124.4 2337.55   132.6 2326.56   144.7 2315.42   167.5 2290.75
   177.1 2281.94   201.4  2254.8   209.5  2239.3   213.5 2235.41   219.9 2231.55
   233.8 2228.69   399.9 2228.74   416.1 2231.13   448.5 2239.92   468.8 2241.21
   558.4 2238.61   626.8  2238.5   683.5 2242.19   699.7 2239.78   707.8 2240.86
     724 2246.53   763.3 2246.68   784.2 2249.64   900.3 2259.49  1058.6 2279.61
#Mann= 4 ,-1,0
       0      .1       0     190    .025       0   219.9    .035       0
   416.1      .1       0
Bank Sta=219.9,416.1
XS Rating Curve= 0 ,0
Exp/Cntr=0.3,0.1