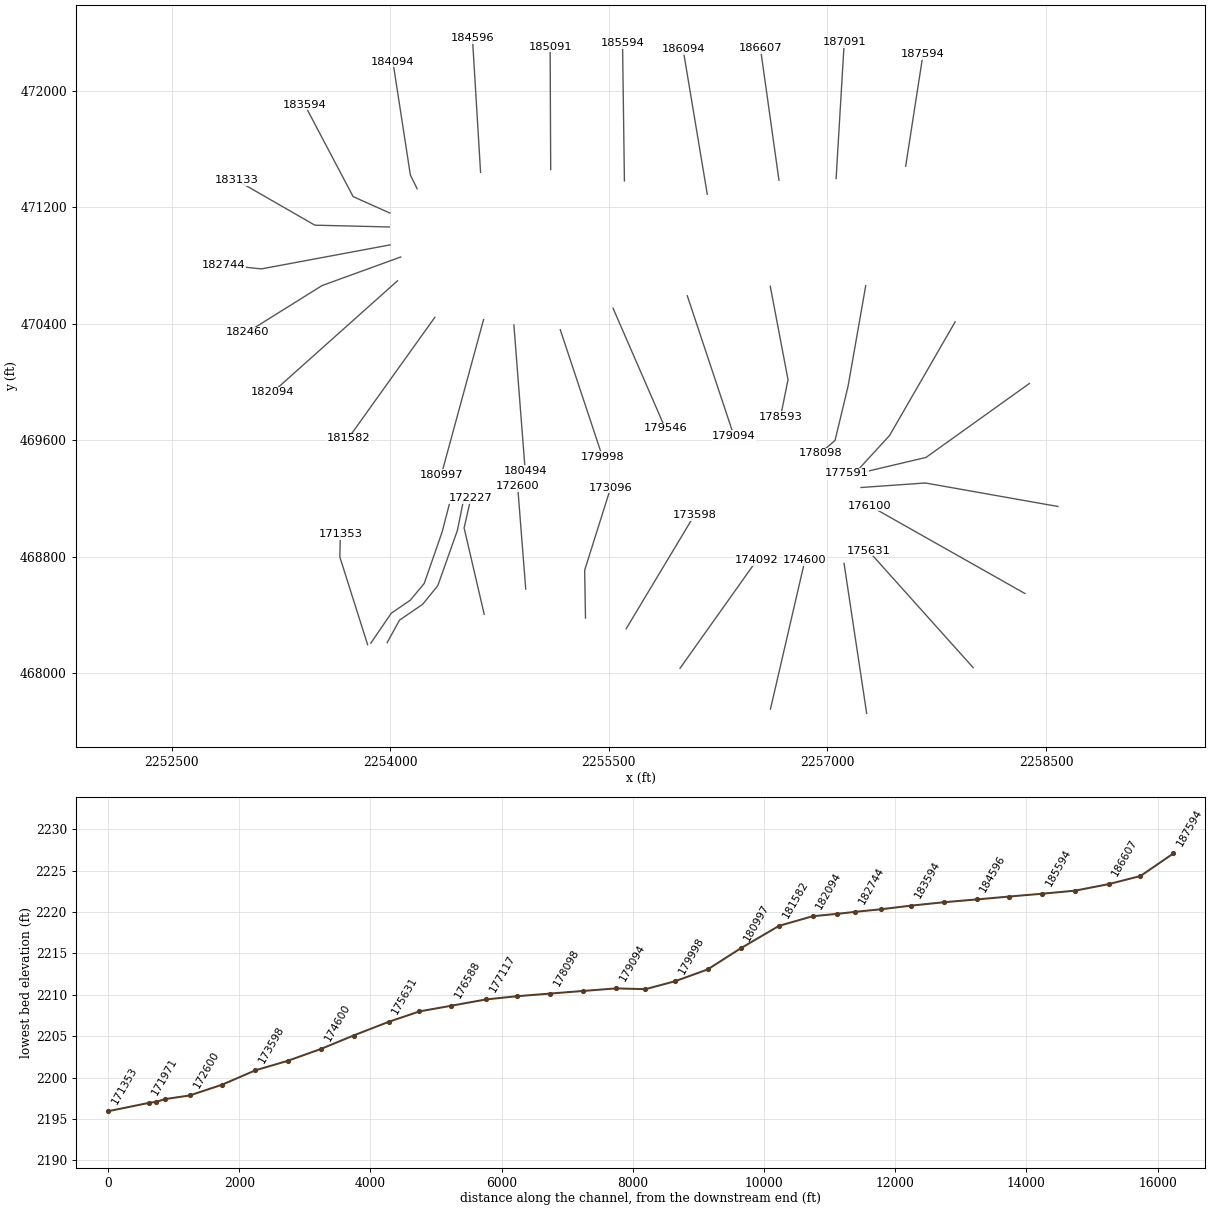
HEC-RAS study GRNBRRRV.prj: GRNBRRRV

--- GRNBRRRV.g01 (geometry) --- (continued)

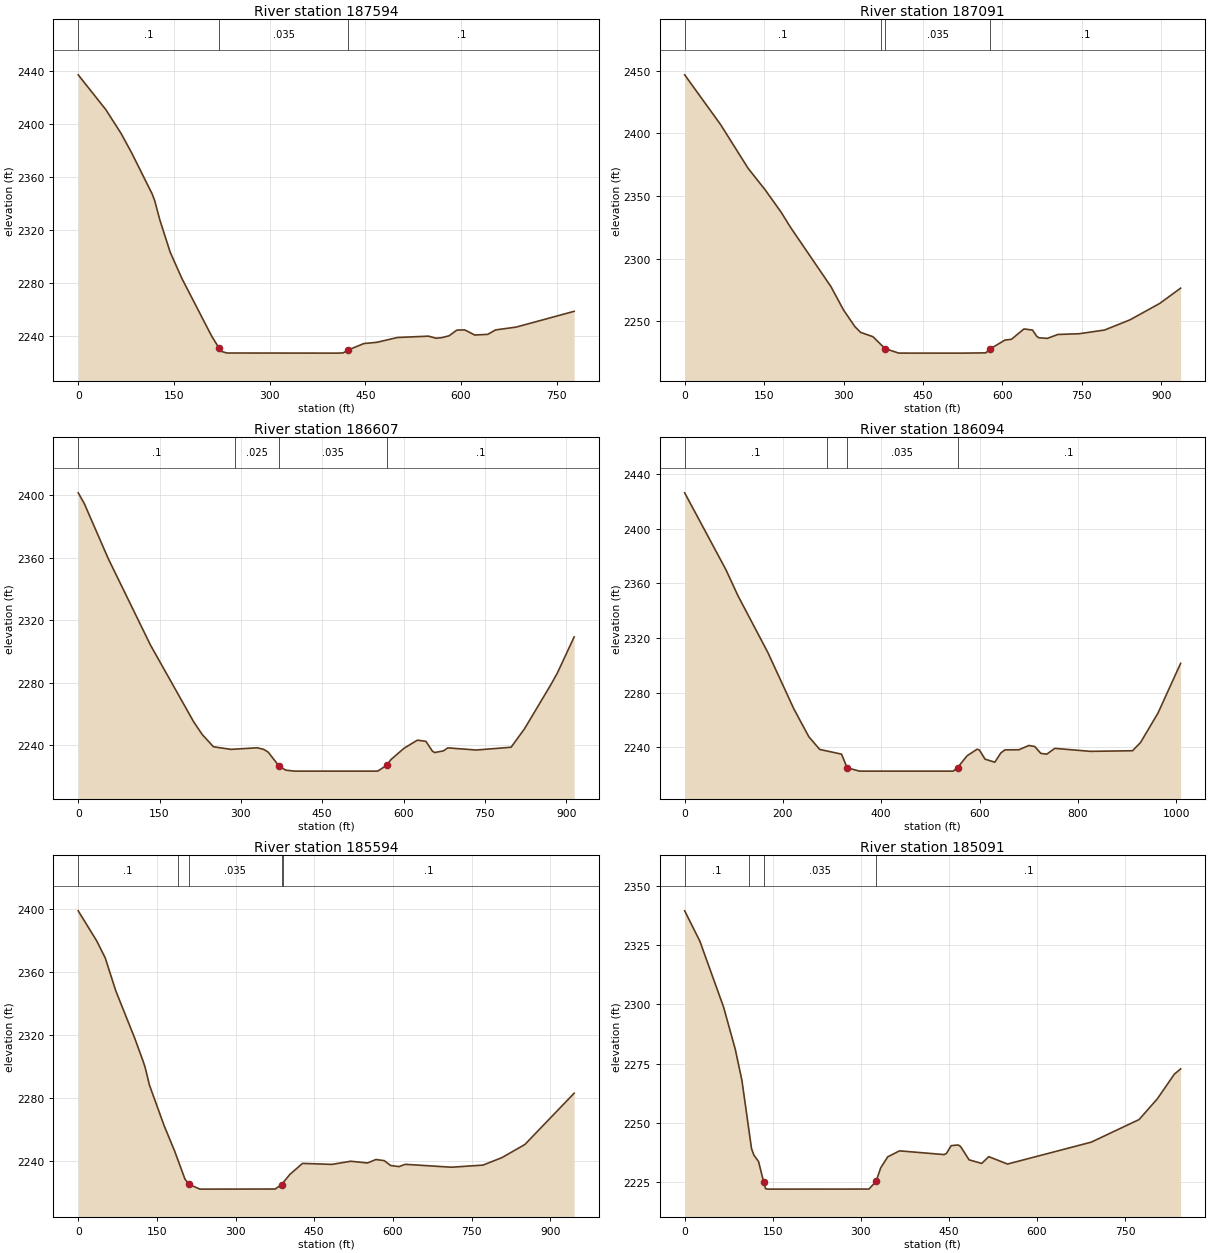
Type RM Length L Ch R = 1 ,187594  ,492.7,502.6,515
XS GIS Cut Line= 2
2257537.22041066471482.645581268     2257656.127      472250.951
#Sta/Elev= 30
       0  2437.2    43.4 2410.86    67.3 2392.88    83.5 2378.56   115.9  2347.3
   119.9 2342.25     128 2327.61   144.2  2303.3   162.5  2283.5     209 2240.14
   221.1 2230.65   225.2  2228.3   233.3 2227.18   407.3 2227.09   415.4 2227.26
   423.5 2229.52   447.8 2234.32     468 2235.24   500.4 2238.88     549 2239.91
   561.1 2238.33   569.4  2238.7   581.4 2240.19   593.5 2244.44   605.7 2244.66
   621.8 2240.75   642.1 2241.27   654.2  2244.6   686.6 2246.75   777.5 2258.65
#Mann= 3 ,0,0
       0      .1       0   221.1    .035       0   423.5      .1       0
Bank Sta=221.1,423.5
XS Rating Curve= 0 ,0
Exp/Cntr=0.3,0.1

Type RM Length L Ch R = 1 ,187091  ,463.6,483.8,510.9
XS GIS Cut Line= 2
     2257059.685      471397.5842257115.34394133472332.468527987
#Sta/Elev= 30
       0 2446.88    67.7 2407.18   119.8 2372.13   151.9 2354.98   182.3 2336.94
   199.9 2324.92   276.2 2277.55   300.1 2258.77   321.5 2245.51   332.2 2240.96
   355.6 2237.48   378.3 2227.99   378.3 2227.98   404.3 2224.38   524.5 2224.36
   568.6 2224.57   576.6 2227.66   604.7 2234.79   616.9 2235.39   640.7 2243.71
   656.8  2242.8   664.8 2237.82   668.8 2236.64   684.8 2236.16   704.8 2239.28
   744.7 2239.86     793 2242.84   841.1 2251.02   897.2 2264.13   936.5 2276.31
#Mann= 4 ,-1,0
       0      .1       0     370    .025       0   378.3    .035       0
   576.6      .1       0
Bank Sta=378.3,576.6
XS Rating Curve= 0 ,0
Exp/Cntr=0.3,0.1

Type RM Length L Ch R = 1 ,186607  ,513.3,513.2,517.1
XS GIS Cut Line= 2
     2256667.586      471386.0982256540.45352799472291.913175996
#Sta/Elev= 30
       0 2401.55    11.2 2394.69    55.6 2359.29   133.3 2304.07   213.1 2254.86
   228.9 2246.76   249.5 2238.97   281.8 2237.31   330.3 2238.33   342.4 2237.27
   350.5 2235.51   370.7 2226.49   382.8    2224   398.7 2223.38   552.4 2223.38
   568.6 2227.04   576.7 2230.73     601 2238.04   625.6 2243.21   641.3 2242.46
   653.4 2236.11   657.5 2235.28   673.6 2236.36   681.7 2238.27   734.2 2236.89
   798.4 2238.68   823.1 2250.47   871.5 2278.59   883.7 2286.18   914.7 2309.29
#Mann= 4 ,-1,0
       0      .1       0     290    .025       0   370.7    .035       0
   568.6      .1       0
Bank Sta=370.7,568.6
XS Rating Curve= 0 ,0
Exp/Cntr=0.3,0.1

Type RM Length L Ch R = 1 ,186094  ,521.2,500.1,484.9
XS GIS Cut Line= 2
     2256175.444       471290.222256009.56870667472285.781935951
#Sta/Elev= 30
       0 2426.12    84.1  2369.8   108.4 2350.89   169.3 2309.34     222 2268.26
   252.6 2247.81   274.7 2238.48   319.3    2235   330.5 2225.06   355.8 2222.59
   546.4 2222.59   555.3 2225.14   574.8 2233.83   595.1 2238.62   599.8 2238.01
   611.3 2231.36   631.1 2229.11   643.7    2236   651.9 2238.14   680.2 2238.21
   700.3 2241.34   712.6 2240.58   724.8 2235.56     737    2235   753.2 2239.23
   826.2 2237.05   911.4  2237.5   927.6 2243.47   963.1 2264.94  1009.3 2301.41
#Mann= 4 ,-1,0
       0      .1       0     290    .025       0   330.5    .035       0
   555.3      .1       0
Bank Sta=330.5,555.3
XS Rating Curve= 0 ,0
Exp/Cntr=0.3,0.1

Type RM Length L Ch R = 1 ,185594  ,503.8,502.7,502.3
XS GIS Cut Line= 2
     2255606.898471381.5366399332255593.95494134472327.183343915
#Sta/Elev= 30
       0 2398.72    35.6 2379.48    51.6 2368.79    71.6 2348.02   107.7    2318
   123.7  2303.4   127.7 2299.35   135.7 2288.34   164.1 2262.25   183.9 2246.35
   203.7 2228.47   211.8 2225.21   232.1 2222.22   375.7 2222.28   387.7 2225.13
   403.7 2231.59   427.7 2238.54   483.8 2237.91   519.7  2239.9   551.7 2238.81
   567.7    2241   583.7 2240.28   595.7  2237.2   611.7 2236.51   623.7 2237.95
   711.7 2236.12   771.9 2237.45   808.1 2242.22   851.7 2250.52   945.7 2283.05
#Mann= 5 ,-1,0
       0      .1       0     190    .025       0   211.8    .035       0
   387.7    .025       0     390      .1       0
Bank Sta=211.8,387.7
XS Rating Curve= 0 ,0
Exp/Cntr=0.3,0.1

Type RM Length L Ch R = 1 ,185091  ,488.3,495.2,501.4
XS GIS Cut Line= 2
2255100.97788267471459.361282558      2255096.96472303.855991924
#Sta/Elev= 30
       0 2339.59    25.8  2326.8    66.3 2298.85    86.2 2280.99    97.5 2267.83
   113.8 2239.05   117.8 2236.28   125.8 2233.55   134.52224.932   137.8 2222.06
   141.8 2221.88   313.8 2221.91   325.8 2225.11   333.8 2230.89   345.8 2235.54
   365.8 2238.07   441.8 2236.49   445.8    2237   453.8 2240.27   465.8 2240.55
   469.8 2239.92   484.3 2234.27   505.8 2232.75   517.8 2235.61   549.8 2232.49
   692.3 2241.75   773.8 2251.31   804.9  2260.1   833.8  2270.5   844.5 2272.74
#Mann= 4 ,-1,0
       0      .1       0     110    .025       0   134.5    .035       0
   325.8      .1       0
Bank Sta=134.5,325.8
XS Rating Curve= 0 ,0
Exp/Cntr=0.3,0.1

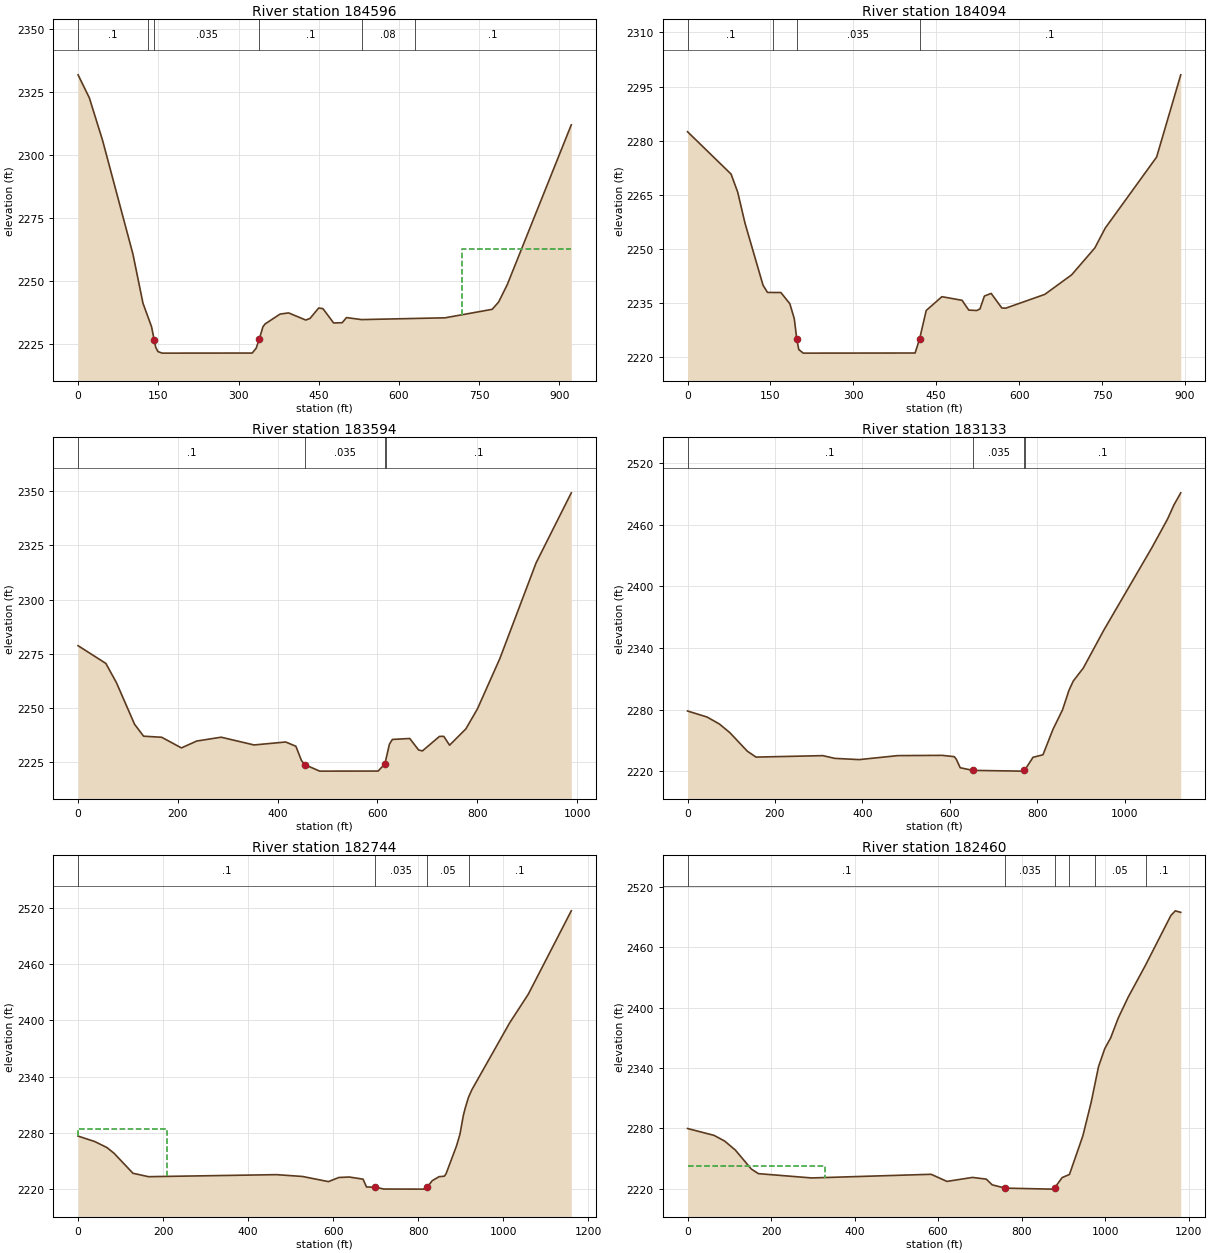
Type RM Length L Ch R = 1 ,184596  ,490.5,502.1,513.2
XS GIS Cut Line= 2
2254619.71201612471440.1512450072254563.96176534472360.765399888
#Sta/Elev= 30
       0 2331.84    21.1  2322.7    45.9  2305.8   102.6 2260.77   121.4 2241.28
   137.3 2232.06   142.4 2226.78   145.3 2223.79   149.3 2222.15   157.3 2221.53
   325.6 2221.56     333 2223.47   338.6 2226.96   345.7 2231.96   349.7 2233.09
   377.7 2237.01   393.7 2237.47   425.8 2234.64   433.8  2235.3   449.9 2239.41
   457.9 2239.16   477.9 2233.49   493.9 2233.59   501.9 2235.62     530 2234.82
   686.3 2235.53   774.4 2238.89   786.5 2241.81   802.5 2248.64   922.3 2312.02
#Mann= 6 ,-1,0
       0      .1       0     130    .025       0   142.4    .035       0
   338.6      .1       0     530     .08       0     630      .1       0
#XS Ineff= 2 , 0
                          717.36         2262.87
Permanent Ineff=
       F       F
Bank Sta=142.4,338.6
XS Rating Curve= 0 ,0
Exp/Cntr=0.3,0.1

Type RM Length L Ch R = 1 ,184094  ,464.6,500.2,536.5
XS GIS Cut Line= 3
     2254184.175471327.7629332592254137.75251236471422.300893016
  2254018.158824472200.300463937
#Sta/Elev= 30
       0  2282.5    78.8 2270.77    90.8 2265.76   104.1 2257.11   136.6    2240
   144.7    2238   168.9 2237.97   185.1 2234.88   193.2 2230.69   197.7 2225.05
   201.3 2222.18   209.4 2221.19   411.8 2221.22   419.9 2225.11   431.9    2233
   460.3 2236.82   496.7 2235.82   508.9 2233.11   523.1 2232.99   529.1 2233.41
   537.2    2237   549.4 2237.73   568.7 2233.69   575.8 2233.64   646.5 2237.46
   695.1 2242.88   737.1 2250.33   755.8 2255.81   848.8 2275.48   892.5 2298.26
#Mann= 4 ,-1,0
       0      .1       0  155.32    .025       0   197.7    .035       0
   419.9      .1       0
Bank Sta=197.7,419.9
XS Rating Curve= 0 ,0
Exp/Cntr=0.3,0.1

Type RM Length L Ch R = 1 ,183594  ,408.6,461.2,511.5
XS GIS Cut Line= 3
2253997.16316792471160.6052319692253745.04476856471273.547959757
     2253413.051      471903.599
#Sta/Elev= 30
       0 2278.68    55.7  2270.5    76.9  2261.6   113.2 2242.42   131.3 2236.91
   167.6 2236.41   207.1  2231.5   237.8 2234.67   286.7 2236.44   352.7 2232.86
     416 2234.23   436.5 2232.26   447.7 2225.66   454.3  2223.8   484.1 2220.78
   601.4 2220.81   614.9 2224.16     624 2233.26   629.9 2235.41   664.7 2235.85
   682.3 2230.57     690  2230.1   724.3 2236.81   732.9 2236.84   744.5 2232.75
   777.1 2240.27   800.3 2249.51   845.2 2272.72   917.9 2316.93   988.4 2349.25
#Mann= 4 ,-1,0
       0      .1       0   454.3    .035       0   614.9    .025       0
  616.26      .1       0
Bank Sta=454.3,614.9
XS Rating Curve= 0 ,0
Exp/Cntr=0.3,0.1

Type RM Length L Ch R = 1 ,183133  ,328.8,388.9,441.3
XS GIS Cut Line= 3
2253992.77401063471064.9888323192253482.18844073471077.313311593
2252946.95391228471385.425293431
#Sta/Elev= 30
       0 2278.84    44.6 2272.97    72.6 2266.26    96.6 2257.86   136.6  2239.8
   156.6 2233.99   309.4 2235.41   336.8 2232.75   392.7 2231.54   480.7 2235.43
   582.3 2235.69     610 2234.43   614.7 2232.02   623.8 2223.63   652.7 2221.07
   762.3 2220.34   769.9 2221.07   772.8 2222.28   790.4 2233.81   813.1 2236.25
   836.1 2261.08   857.8 2279.91   872.4 2298.76   882.3 2307.94   905.4 2320.64
   951.6 2356.96  1062.3 2437.77    1098 2465.46  1112.6  2479.2  1128.3 2491.07
#Mann= 4 ,-1,0
       0      .1       0   652.7    .035       0   769.9    .025       0
   772.8      .1       0
Bank Sta=652.7,769.9
XS Rating Curve= 0 ,0
Exp/Cntr(USF)=0,0
Exp/Cntr=0.3,0.1

Type RM Length L Ch R = 1 ,182744  ,252.1,283.7,311.6
XS GIS Cut Line= 3
2253999.09646263470941.9167454552253115.02295903 470776.88969145
 2252855.6947313470804.394200451
#Sta/Elev= 30
       0 2276.61    39.6 2270.72    68.1 2264.31    84.4 2258.38   129.1 2236.95
   165.7  2233.3   466.8 2235.47   527.9 2233.53   588.9 2228.04   613.3 2232.44
   637.8 2232.94   670.3 2230.67   678.4 2222.34   699.2 2222.07   719.1 2220.13
   812.7 2220.03   820.9 2222.01   833.1 2229.07   849.3 2233.32   861.6 2233.82
   865.6 2236.48     890 2265.93   898.2 2278.51   906.2  2298.6   910.3 2305.91
   918.3 2317.97   926.3 2326.07  1014.9 2397.17  1059.1 2428.01  1160.1 2516.83
#Mann= 4 ,-1,0
       0      .1       0   699.2    .035       0   820.9     .05       0
  919.34      .1       0
#XS Ineff= 2 , 0
           209.3 2283.66
Permanent Ineff=
       F       F
Bank Sta=699.2,820.9
XS Rating Curve= 0 ,0
Exp/Cntr(USF)=0,0
Exp/Cntr=0.3,0.1

Type RM Length L Ch R = 1 ,182460  ,349.9,366.2,378.5
BEGIN DESCRIPTION:
IFA added to correct profile crossing
END DESCRIPTION:
XS GIS Cut Line= 3
2254071.75634969470858.6394476972253532.37421414470662.744443241
2253017.14351749470340.725257833
#Sta/Elev= 30
       0 2279.94    63.4 2273.14    88.9 2267.48   114.5 2258.55   152.8  2239.7
   169.8 2235.14   297.4 2230.88   583.5  2234.5   621.3 2227.44   682.5  2231.4
   715.6  2229.7   729.7 2224.04   760.9 2220.77   871.3 2219.78   879.4  2221.1
   897.3 2231.23   914.8 2234.34   946.9 2272.63     967 2306.31     975 2322.41
   984.5 2341.44   999.4 2359.21  1013.5 2369.86  1031.6 2389.47  1055.2 2410.07
  1097.6  2442.5  1097.6 2442.55  1157.9 2491.43  1168.4 2495.95  1181.4 2494.43
#Mann= 6 ,-1,0
       0      .1       0   760.9    .035       0   879.4     .05       0
   914.8      .1       0     975     .05       0  1097.6      .1       0
#XS Ineff= 2 , 0
          328.56 2242.94
Permanent Ineff=
       F       F
Bank Sta=760.9,879.4
XS Rating Curve= 0 ,0
Exp/Cntr(USF)=0,0
Exp/Cntr=0.3,0.1

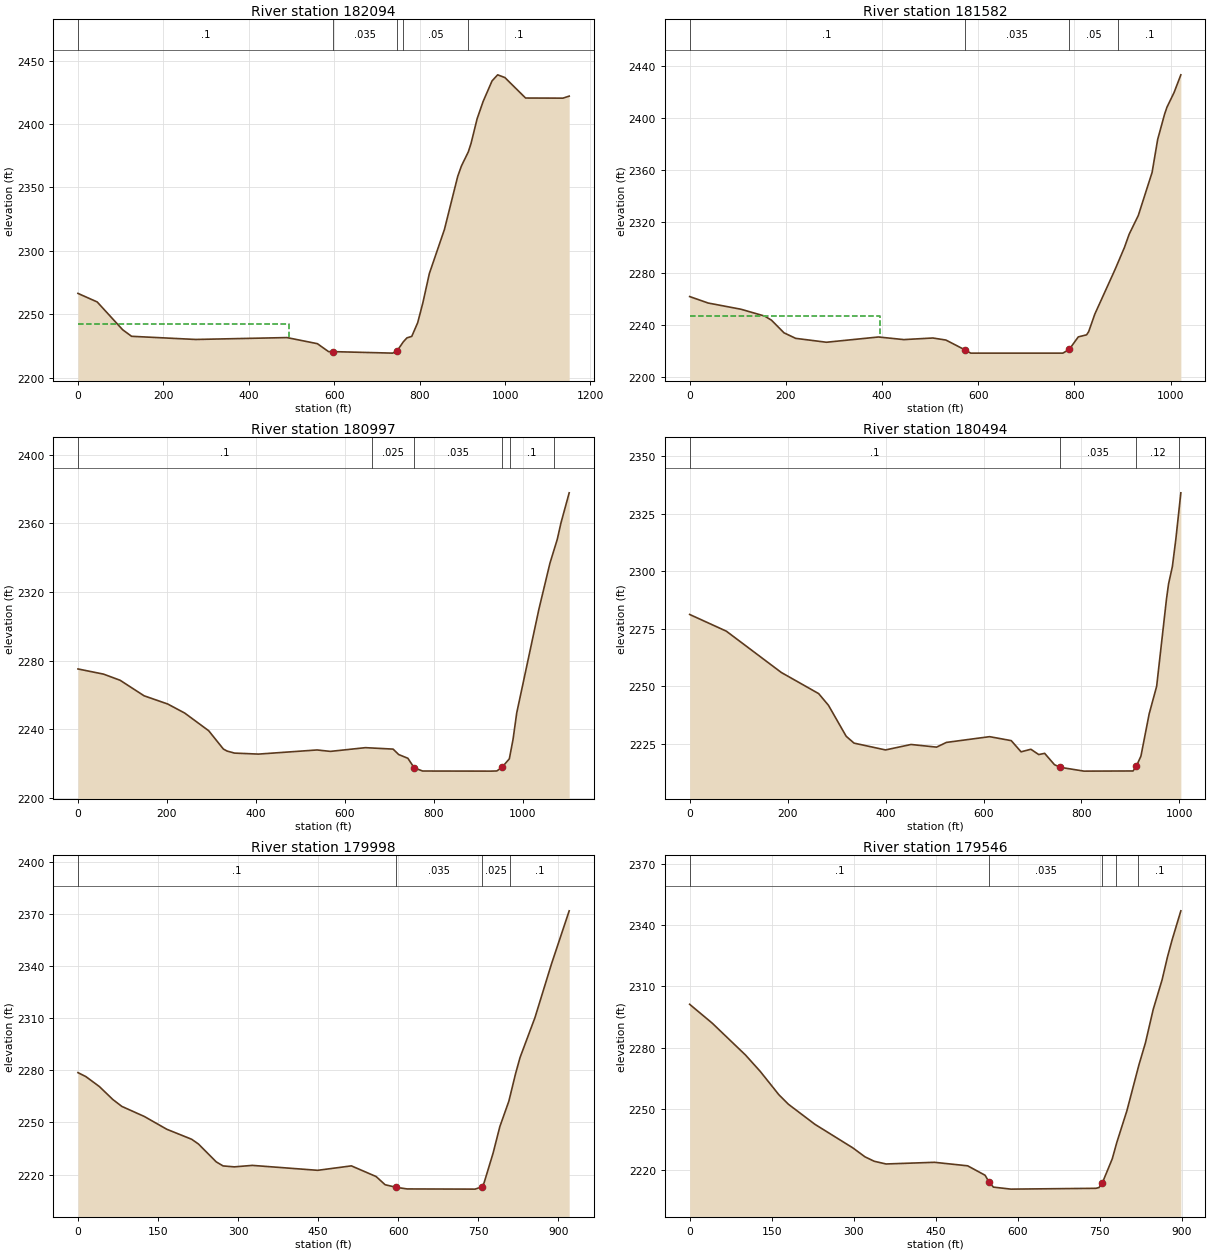
Type RM Length L Ch R = 1 ,182094  ,483.6,512.3,535.8
BEGIN DESCRIPTION:
IFA added to block the 100 yr to correct profile crossing on immediate US xs
END DESCRIPTION:
XS GIS Cut Line= 2
2254049.72851991470695.231167919     2253192.107      469928.856
#Sta/Elev= 30
       0 2266.55      45 2259.82   104.5 2237.96   125.5 2232.75   275.7 2230.26
   489.3 2231.75   560.6 2226.94   586.8 2220.68   597.5 2220.68     737  2219.5
   747.5 2221.44   761.8  2228.4   770.3 2231.52   781.6  2232.7   795.5 2243.53
   807.5 2259.04   822.8 2282.25   858.1 2316.93   889.2 2358.76   897.9 2366.96
     914 2378.06   920.4 2384.71   934.6  2404.1   948.7 2417.77   969.6 2433.97
   982.7 2438.74   999.6 2436.59  1048.1 2420.46  1135.7 2420.37  1150.2 2421.97
#Mann= 5 ,-1,0
       0      .1       0   597.5    .035       0   747.5      .1       0
   761.8     .05       0     914      .1       0
#XS Ineff= 2 , 0
          493.72 2242.61
Permanent Ineff=
       F       F
Bank Sta=597.5,747.5
XS Rating Curve= 0 ,0
Exp/Cntr=0.3,0.1

Type RM Length L Ch R = 1 ,181582  ,540.6,584.9,626.9
XS GIS Cut Line= 2
2254306.04445078470444.5816231322253712.15064262469613.688877286
#Sta/Elev= 30
       0 2262.08    38.6 2257.06   106.4  2252.3   155.7 2247.02   170.1 2243.83
   196.2 2234.04   220.5 2229.76   284.4 2226.75   392.6 2230.81   445.3  2228.8
   505.7 2230.03   532.9 2228.44   571.5 2221.03   584.4 2218.34   776.1 2218.34
   789.4 2221.29     808 2230.88   825.3 2232.49   829.6  2234.9   842.4 2248.48
   884.3 2282.83   904.1 2300.12   913.8 2310.26   932.8 2324.72   961.5 2358.03
   973.1 2383.54   987.5  2403.1   992.4 2408.46  1007.2 2419.82  1021.3 2433.49
#Mann= 4 ,-1,0
       0      .1       0   571.5    .035       0   789.4     .05       0
     890      .1       0
#XS Ineff= 2 , 0
          396.17 2247.42
Permanent Ineff=
       F       F
Bank Sta=571.5,789.4
XS Rating Curve= 0 ,0
Exp/Cntr=0.3,0.1

Type RM Length L Ch R = 1 ,180997  ,465.1,503.2,539.8
XS GIS Cut Line= 2
 2254640.2068647470428.5619216222254350.45492337469363.417461251
#Sta/Elev= 30
       0 2275.15    57.4 2272.14    94.7 2268.56   148.6 2259.51   201.6 2254.73
   239.8 2249.46   293.7 2239.17   326.8 2228.48     335 2227.32   351.7 2226.13
   405.6 2225.54   537.2 2227.95   567.3 2227.12     646 2229.29   708.2 2228.45
   720.7 2225.29   741.4  2223.1   755.6 2217.54   774.5 2215.68   928.3 2215.62
   941.3 2215.72   952.8  2217.8   969.4  2222.8   977.7 2234.09     986 2249.53
  1035.8 2309.92  1060.6 2336.72  1077.2 2350.75  1085.4 2360.23  1103.9 2377.77
#Mann= 6 ,-1,0
       0      .1       0     660    .025       0   755.6    .035       0
   952.8    .025       0     970      .1       0    1070     .12       0
Bank Sta=755.6,952.8
XS Rating Curve= 0 ,0
Exp/Cntr(USF)=0,0
Exp/Cntr=0.3,0.1

Type RM Length L Ch R = 1 ,180494  ,470.4,495.6,517.5
XS GIS Cut Line= 2
2254848.33854086470391.8328022992254925.87779277469391.984554058
#Sta/Elev= 30
       0 2281.23    74.9 2273.96   187.2 2255.98   263.4  2246.8   283.5 2241.69
   319.6 2228.24   335.7 2225.25   399.9 2222.29     452 2224.66   504.2 2223.51
   524.2 2225.56   612.5 2228.06   656.6 2226.34   676.7 2221.47   696.7 2222.58
   712.8 2220.27   724.8 2220.81   744.9 2215.86   756.9 2214.72   805.1 2213.07
   905.4 2213.14   912.1 2215.28   921.4  2219.6   938.2 2237.97   953.5 2249.99
   973.6 2288.02   977.8 2294.51   985.6 2302.09   992.7 2314.03  1002.9 2334.14
#Mann= 4 ,-1,0
       0      .1       0   756.9    .035       0   912.1     .12       0
    1000      .1       0
Bank Sta=756.9,912.1
XS Rating Curve= 0 ,0
Exp/Cntr(USF)=0,0
Exp/Cntr=0.3,0.1

Type RM Length L Ch R = 1 ,179998  ,444.2,452.2,460.6
XS GIS Cut Line= 2
  2255166.657575470359.1846962342255456.40951633469485.847858995
#Sta/Elev= 30
       0 2278.68    14.8 2276.39      40 2270.69    65.3 2263.21    82.2 2259.24
   124.3 2253.45   166.5 2246.07   212.8 2240.36   225.5 2237.66   259.1  2227.3
   271.8    2225   292.9 2224.46   326.6 2225.31     449 2222.47   512.1 2225.03
   558.4  2218.9   575.3 2214.18   596.3 2212.67   616.7 2211.76   743.8 2211.65
   756.5 2212.94   760.7 2215.29   777.6  2232.4   790.2 2247.61   807.1 2262.26
   819.7 2278.13   828.1 2287.42   855.9 2310.26   887.1 2341.37   920.1 2371.77
#Mann= 4 ,-1,0
       0      .1       0   596.3    .035       0   756.5    .025       0
     810      .1       0
Bank Sta=596.3,756.5
XS Rating Curve= 0 ,0
Exp/Cntr(USF)=0,0
Exp/Cntr=0.3,0.1

Type RM Length L Ch R = 1 ,179546  ,464.1,452.1,443.3
XS GIS Cut Line= 2
2255528.77285416470506.9097159392255886.91666855469682.751676165
#Sta/Elev= 30
       0 2301.18    41.1 2291.99   102.2 2276.34     129 2268.37   163.3 2256.88
   180.7 2252.24   229.3  2242.4   298.5 2230.89   320.7 2226.51   337.7 2224.33
   359.3    2223   447.8 2223.82   508.6  2222.1   540.5 2217.48   548.1 2213.98
   555.8 2211.67   587.6 2210.69   743.3 2211.09   748.8 2211.46   754.8 2213.63
   773.1 2225.52   781.3 2233.43     800 2249.16   821.8 2271.42   833.9  2282.4
     848 2298.64   864.3 2313.18   874.2 2324.44   882.5 2332.61   898.6 2346.93
#Mann= 5 ,-1,0
       0      .1       0   548.1    .035       0   754.8      .1       0
     780    .025       0     820      .1       0
Bank Sta=548.1,754.8
XS Rating Curve= 0 ,0
Exp/Cntr=0.3,0.1

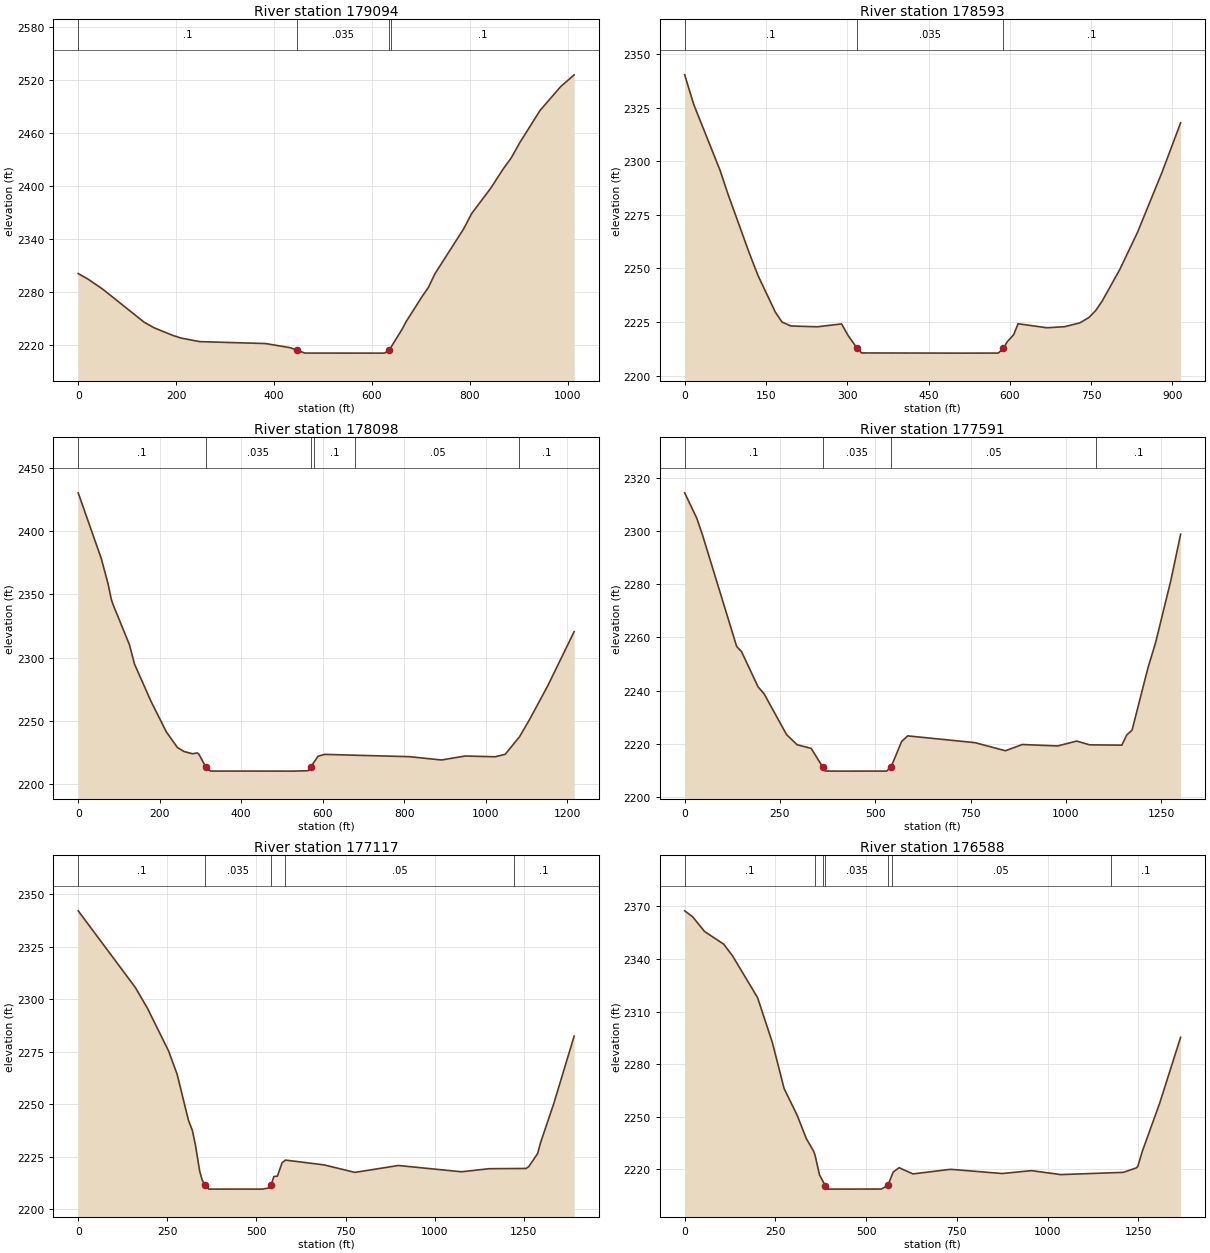
Type RM Length L Ch R = 1 ,179094  ,521.9,501,484.8
XS GIS Cut Line= 2
2256038.29889394470592.424318195     2256358.235      469631.019
#Sta/Elev= 30
       0 2300.97    20.3 2294.59    49.8  2283.4   134.8 2245.82   155.2 2239.45
   193.1 2230.91   209.6 2227.95   247.9 2223.83   382.8 2221.63   433.4 2216.92
   446.1 2214.35   462.9 2210.84   623.1 2210.78   627.3 2211.19   635.8 2214.45
     640 2218.36     662 2238.14   669.5 2246.09   703.2 2275.51   715.4 2285.17
   728.5 2300.46   787.5  2351.7     804 2369.15   842.3 2397.35   867.6 2419.06
   884.5 2431.93   902.4 2449.62   943.5 2485.85   985.7 2512.94  1013.2 2526.26
#Mann= 4 ,-1,0
       0      .1       0   446.1    .035       0   635.8    .025       0
     640      .1       0
Bank Sta=446.1,635.8
XS Rating Curve= 0 ,0
Exp/Cntr=0.3,0.1

Type RM Length L Ch R = 1 ,178593  ,551.6,494.9,441.9
XS GIS Cut Line= 3
     2256607.848      470657.6062256729.68565286470016.379582551
 2256677.8846818469759.162986742
#Sta/Elev= 30
       0 2340.45    16.7 2326.64    65.6 2295.65    79.3 2285.17   118.5 2257.71
   134.8 2246.99   167.4 2229.56   179.6 2224.99   195.9 2223.15   244.7 2222.77
   289.5 2224.11   301.7 2218.65     318 2212.86   326.2 2210.56   512.8 2210.47
   578.6  2210.5   588.2 2212.66   594.9 2215.69   607.1  2219.1   615.2 2224.19
   668.2 2222.32   700.9 2222.81   729.4 2224.62   745.7 2227.07     758 2230.23
   770.2 2234.71   802.9 2249.55   835.5 2266.86   880.9 2294.99   915.1 2318.04
#Mann= 3 ,-1,0
       0      .1       0     318    .035       0   588.2      .1       0
Bank Sta=318,588.2
XS Rating Curve= 0 ,0
Exp/Cntr=0.3,0.1

Type RM Length L Ch R = 1 ,178098  ,559.5,506.9,463.1
XS GIS Cut Line= 4
     2257262.922      470661.1572257141.86799193469971.488436712
2257052.54106611469599.0722151242256951.21165563469510.867946839
#Sta/Elev= 30
       0 2430.35    56.8 2378.18    73.1 2358.63    81.2 2346.17    85.3 2342.16
   125.9 2310.09   138.1 2294.95   178.8 2265.33   216.5 2241.14   243.6 2228.84
   259.9 2225.68   280.2 2223.93   292.6 2224.55   296.4 2223.51   312.7 2213.72
   324.9 2210.21   527.5 2210.16   564.5 2210.49   571.2 2213.56   588.8 2221.96
   605.1 2223.41   813.7 2221.58   891.8 2218.98     950 2222.12  1023.4 2221.52
  1048.1 2223.45  1083.2 2237.25  1107.5 2250.66  1152.6 2277.62  1217.5 2320.53
#Mann= 6 ,-1,0
       0      .1       0   312.7    .035       0   571.2    .025       0
     580      .1       0     680     .05       0 1083.19      .1       0
Bank Sta=312.7,571.2
XS Rating Curve= 0 ,0
Exp/Cntr=0.3,0.1

Type RM Length L Ch R = 1 ,177591  ,523,473.8,427.6
XS GIS Cut Line= 4
      2257876.37      470412.6992257426.77507037469632.764336287
 2257218.8369409469405.8290217622257132.40168666469371.550864002
#Sta/Elev= 30
       0 2314.26    31.8 2304.72    46.7 2298.46   136.5 2256.59   149.2 2254.65
   192.6 2241.45   208.6  2238.8   267.2 2223.56   294.9 2219.75   331.9 2218.37
362.29092211.348   368.8 2209.88     401 2209.84   529.9 2209.85541.88642211.563
   569.1 2220.96   585.1 2223.07   761.2 2220.53   841.4 2217.49   885.9 2219.83
   978.2 2219.28  1028.4 2221.12  1062.4  2219.7  1146.8 2219.58  1159.4 2223.36
  1173.6 2225.21  1215.2 2248.51  1235.2 2257.97  1275.3 2281.31    1301 2298.74
#Mann= 4 ,-1,0
       0      .1       0362.2909    .035       0541.8864     .05       0
 1080.24      .1       0
Bank Sta=362.2909,541.8864
XS Rating Curve= 0 ,0
Exp/Cntr=0.3,0.1

Type RM Length L Ch R = 1 ,177117  ,610.8,528.6,434.8
XS GIS Cut Line= 3
     2258386.311      469990.0612257676.48072875469481.766845737
 2257172.4344488469362.733708321
#Sta/Elev= 30
       0  2342.2   160.1 2305.67   193.9 2295.82   253.5 2275.34   277.4 2264.27
   308.9 2242.48   320.4 2237.34     329 2230.31   340.5 2218.22     347 2214.18
   354.8 2211.27   366.3 2209.47   516.8 2209.45   537.4  2210.1   541.1  2211.4
   548.7 2215.47   558.6 2215.61   571.8 2222.02   581.3  2223.3   688.6 2221.04
   776.2 2217.44     898 2220.72  1074.8 2217.73  1152.5 2219.19  1256.2 2219.31
  1263.8 2220.21  1288.5 2226.41  1296.7 2231.57  1333.7 2250.18    1391 2282.43
#Mann= 5 ,-1,0
       0      .1       0   354.8    .035       0   541.1      .1       0
     580     .05       0 1223.05      .1       0
Bank Sta=354.8,541.1
XS Rating Curve= 0 ,0
Exp/Cntr=0.3,0.1

Type RM Length L Ch R = 1 ,176588  ,518.3,488.4,445
XS GIS Cut Line= 3
     2258581.976      469144.9862257672.39971549469306.283275637
2257230.59352835469275.334946967
#Sta/Elev= 30
       0  2367.5    22.1 2364.09    54.6 2355.75   107.5 2348.48   131.8 2341.84
   200.9 2317.97   241.5 2292.47     274 2266.12   310.6 2250.55   334.9 2237.65
   355.3 2230.36   359.3 2228.07   371.5 2216.83   387.72210.551   391.8 2208.69
   542.1 2208.74     560 2210.88   574.6 2218.41   590.9 2220.91   629.1 2217.37
   732.8    2220   874.7  2217.6   956.1 2219.24  1036.3 2216.98  1208.7 2218.26
  1244.8 2220.82  1248.8 2221.66  1260.8 2230.06  1308.9 2257.68  1366.7 2295.32
#Mann= 7 ,-1,0
       0      .1       0     360     .12       0     380      .1       0
   387.7    .035       0     560      .1       0     570     .05       0
 1173.77      .1       0
Bank Sta=387.7,560
XS Rating Curve= 0 ,0
Exp/Cntr=0.3,0.1

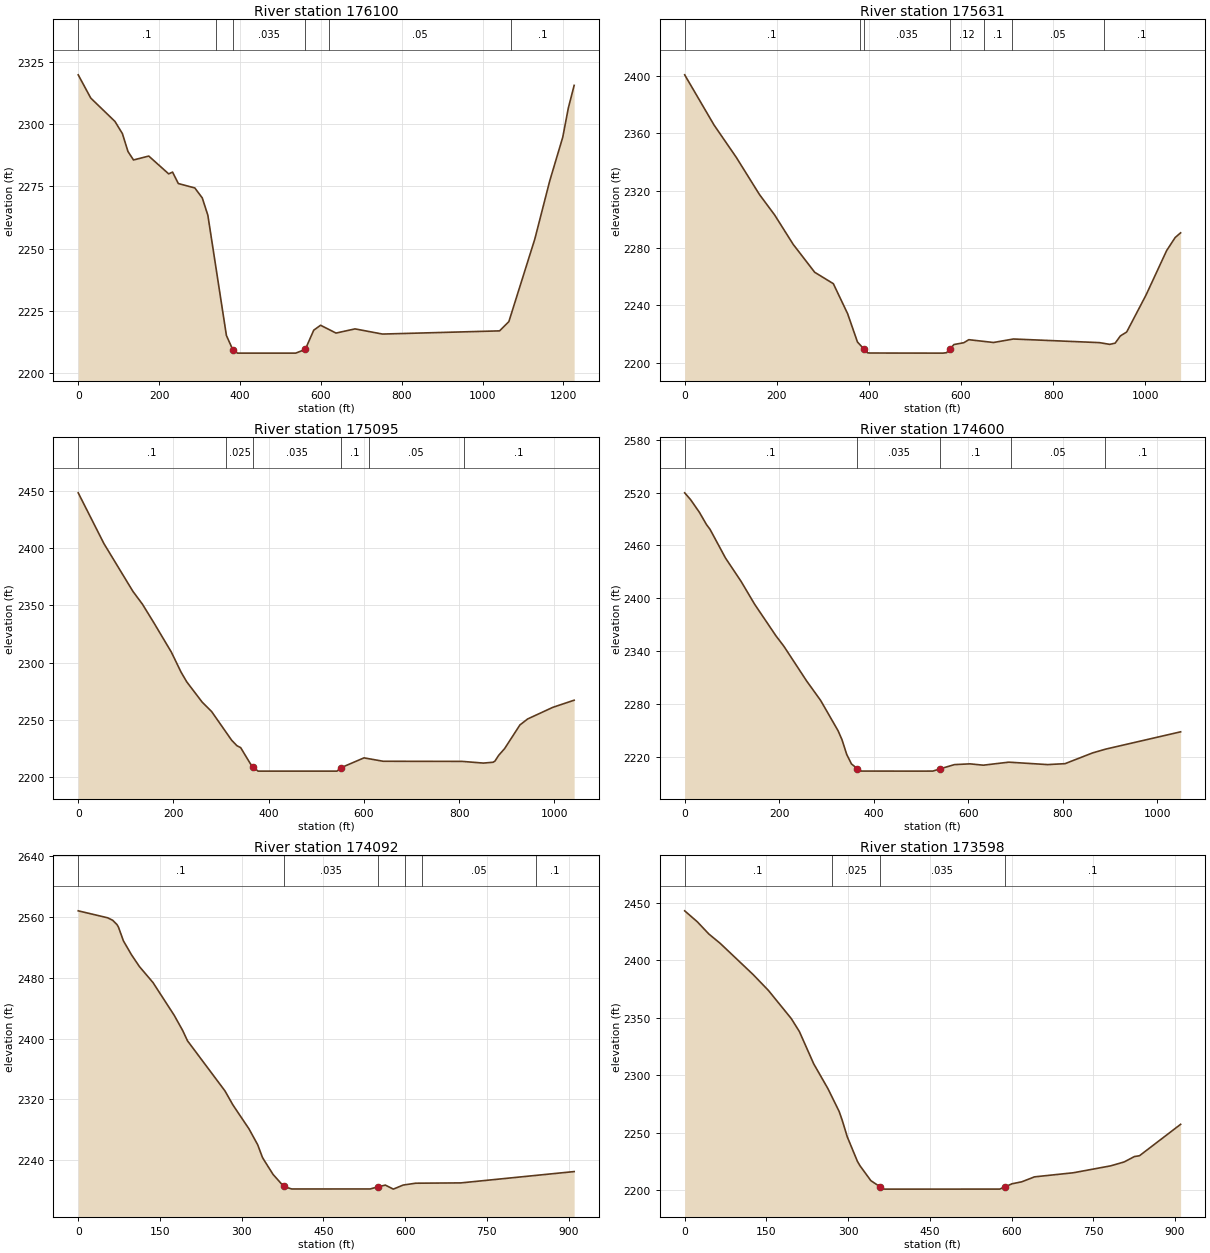
Type RM Length L Ch R = 1 ,176100  ,503.6,469.2,430.7
XS GIS Cut Line= 2
     2258355.278      468547.2542257287.58812496469151.322543583
#Sta/Elev= 30
       0 2319.82    31.1 2310.47    90.9 2301.09   109.3  2296.2   123.1 2289.01
   136.8 2285.61   174.5 2287.18   223.8 2280.02   233.4 2280.74   247.6 2276.14
   288.5 2274.36   306.9 2270.35   320.7 2263.38   366.6 2215.09   382.3 2209.37
   394.1    2208   537.9    2208  561.592209.482   582.6 2217.22   599.5  2219.2
   637.7 2216.06   684.7 2217.74   752.7 2215.66  1042.2 2216.94  1065.2 2220.66
  1129.5 2253.89  1166.3 2277.21  1198.5 2294.75  1212.3 2306.48  1226.7 2315.58
#Mann= 6 ,-1,0
       0      .1       0     340     .12       0   382.3    .035       0
  561.59      .1       0     620     .05       0    1070      .1       0
Bank Sta=382.3,561.59
XS Rating Curve= 0 ,0
Exp/Cntr=0.3,0.1

Type RM Length L Ch R = 1 ,175631  ,598.8,535.6,467.8
XS GIS Cut Line= 2
2258000.51317236468037.6750265162257282.05776135468839.746384486
#Sta/Elev= 30
       0 2400.83    63.8 2365.81   112.1 2343.25   162.4 2317.34   195.3 2303.12
   235.6  2282.6   282.3 2263.13   322.8 2255.17   353.8 2234.24   375.2 2214.46
   390.2 2209.29   396.7 2206.98   402.1 2206.81   560.8 2206.74   568.6 2207.04
     576 2209.65   584.7 2212.74   606.2 2214.01   616.9 2216.11   670.6 2214.16
   713.9 2216.59   900.7 2214.06     923 2212.85   934.7 2213.72     946 2218.73
   959.7 2221.48  1001.7 2247.26  1046.5 2278.29    1065 2287.38  1076.8 2290.63
#Mann= 7 ,-1,0
       0      .1       0     380    .025       0   390.2    .035       0
     576     .12       0     650      .1       0     710     .05       0
     910      .1       0
Bank Sta=390.2,576
XS Rating Curve= 0 ,0
Exp/Cntr=0.3,0.1

Type RM Length L Ch R = 1 ,175095  ,535.1,495,452.1
XS GIS Cut Line= 2
     2257269.469      467723.7022257114.25994697 468753.63342426
#Sta/Elev= 30
       0 2448.34    54.1  2403.9   114.9 2362.22     135 2350.94   159.3 2334.49
   195.7 2309.06   215.9 2291.71     228  2283.1   260.4 2265.38   280.2 2257.16
   322.3 2232.08   333.2 2227.37   341.3 2225.56   361.5 2211.62     368 2208.42
   377.7 2205.09   543.5 2205.09   552.7  2208.2   600.2 2216.68   640.6  2213.7
   806.5  2213.6     851 2212.12   871.2 2212.85   875.2 2213.84   883.3    2219
   895.5 2224.74   927.8 2245.51     944  2250.7   996.6 2260.81  1041.6 2267.09
#Mann= 6 ,-1,0
       0      .1       0     310    .025       0     368    .035       0
   552.7      .1       0     610     .05       0     810      .1       0
Bank Sta=368,552.7
XS Rating Curve= 0 ,0
Exp/Cntr=0.3,0.1

Type RM Length L Ch R = 1 ,174600  ,548,508,464.3
XS GIS Cut Line= 2
     2256609.124      467752.8792256845.59111932468775.395437518
#Sta/Elev= 30
       0  2519.7    12.6 2511.89    31.3 2497.46    46.1 2483.64    53.7 2478.18
    86.5  2445.5   119.4 2419.06   148.1 2393.05   193.3 2357.11     210 2345.31
     258 2305.98   287.7 2283.81   324.6 2249.39   332.9 2239.22   342.9 2222.46
   352.9 2211.68   365.7 2206.17   373.9 2203.53     493 2203.47   525.1 2203.51
   541.1 2206.19     571 2210.88   603.8 2211.74   631.9 2210.22   685.9 2213.66
     768 2210.89     805 2211.96   863.1 2224.15   891.2 2228.51  1049.5 2248.13
#Mann= 5 ,-1,0
       0      .1       0   365.7    .035       0   541.1      .1       0
     690     .05       0     890      .1       0
Bank Sta=365.7,541.1
XS Rating Curve= 0 ,0
Exp/Cntr=0.3,0.1

Type RM Length L Ch R = 1 ,174092  ,485,494,507.5
XS GIS Cut Line= 2
     2255988.562      468033.559      2256515.28      468775.786
#Sta/Elev= 30
       0 2567.85      54 2558.69    63.3 2555.42    71.2 2549.78      74 2546.19
    82.9 2528.47    97.6  2510.3   112.3  2494.6   137.2  2473.6   176.1 2430.58
   191.7 2410.56   200.6 2396.97   269.3 2331.14     284 2312.58   313.4 2281.23
   329.4 2260.32     338 2243.94   340.9 2240.32   357.6 2221.36   377.2 2205.53
   391.9 2202.22   535.9 2202.26   550.3 2205.12   563.6 2207.32   578.3 2202.03
   596.2 2207.36   619.1 2209.81   702.3 2210.22     840 2220.08   910.1  2225.1
#Mann= 6 ,-1,0
       0      .1       0   377.2    .035       0   550.3    .025       0
     600      .1       0     630     .05       0     840      .1       0
Bank Sta=377.2,550.3
XS Rating Curve= 0 ,0
Exp/Cntr=0.3,0.1

Type RM Length L Ch R = 1 ,173598  ,473.4,501.8,536.6
XS GIS Cut Line= 2
     2255619.123      468305.304     2256087.445      469085.934
#Sta/Elev= 30
       0 2443.11    23.2 2433.56    44.4 2422.93    65.2  2414.8   125.8 2387.57
   153.8 2373.77   195.8 2349.24   210.6 2337.99   236.8 2309.99   263.1  2288.2
   283.5 2268.53   289.1 2260.94   298.4 2246.46     317 2225.13   321.7 2221.29
   341.8 2208.23     358 2203.15   363.7  2201.1     368 2200.88   578.3 2200.91
   587.6 2202.74   600.7 2205.52   618.8 2207.26   642.1 2211.56   713.5 2215.13
     782 2221.15   806.8 2224.56   825.5 2229.24   834.8 2229.94   910.3 2257.29
#Mann= 4 ,-1,0
       0      .1       0     270    .025       0     358    .035       0
   587.6      .1       0
Bank Sta=358,587.6
XS Rating Curve= 0 ,0
Exp/Cntr=0.3,0.1

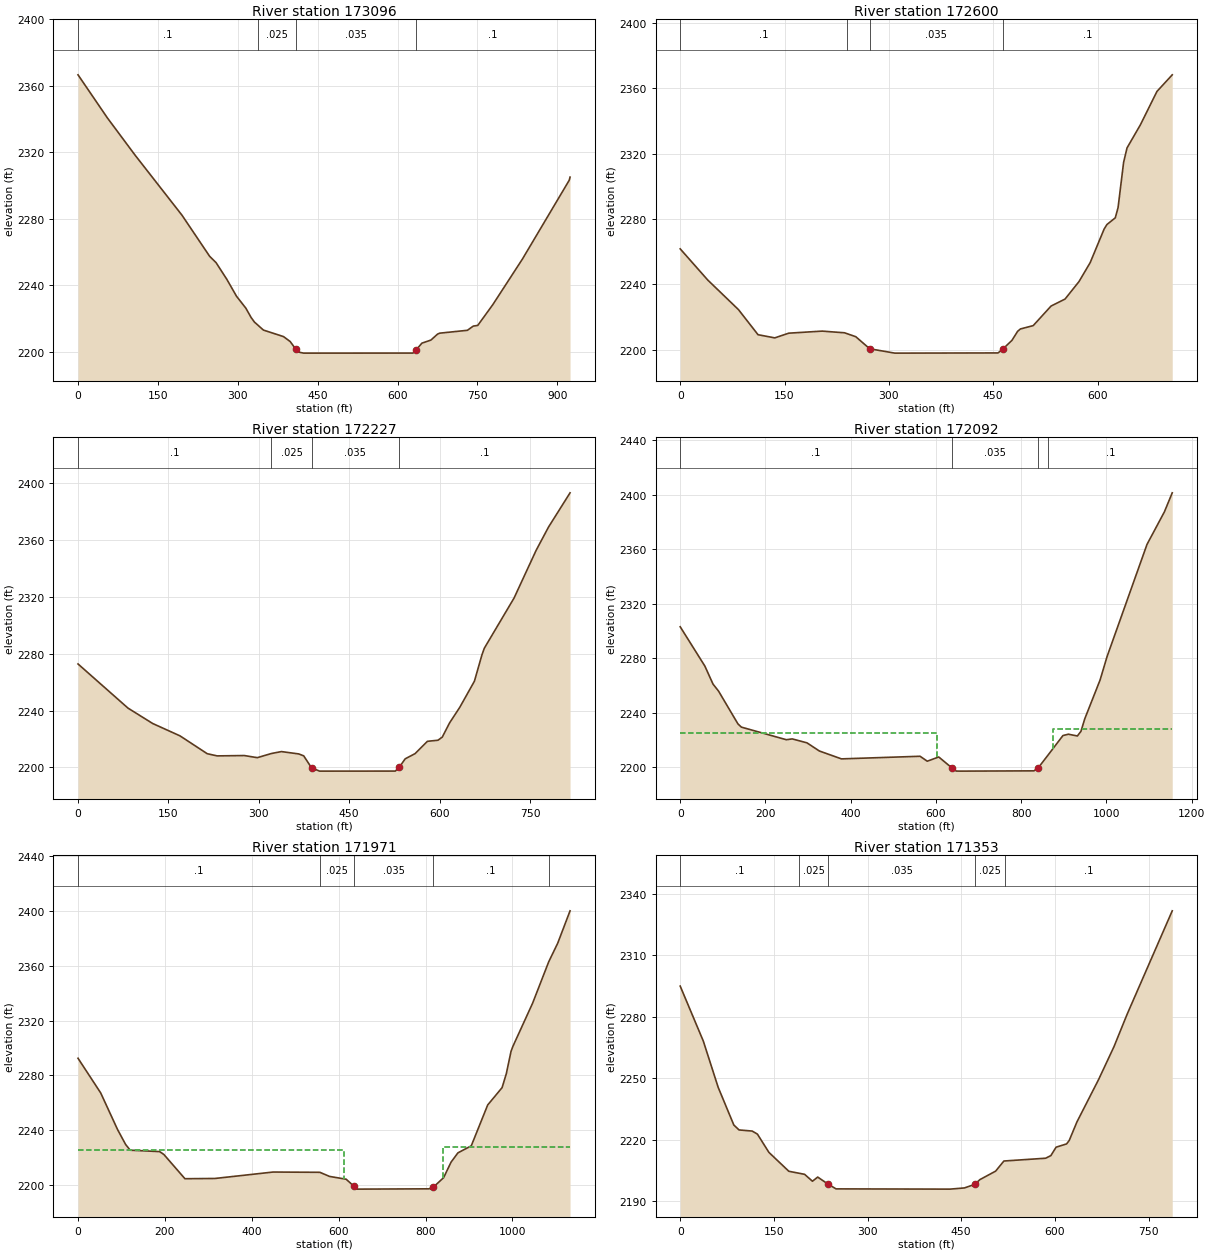
Type RM Length L Ch R = 1 ,173096  ,449.8,496.5,545.5
XS GIS Cut Line= 3
2255339.80923865468378.0556950632255333.97911858468706.374326692
2255512.62574048469274.468265163
#Sta/Elev= 30
       0 2366.55    55.1 2340.66   107.1 2318.26   195.2 2282.13   247.2 2257.38
   259.2 2253.59   279.2 2243.68   297.5 2233.43   315.2 2226.17     325  2220.6
   331.3 2217.83   348.1 2213.03   385.8 2209.11   398.4 2206.13   408.8 2201.59
   415.2 2199.72   423.6 2199.16     629 2199.19   635.4 2201.33   645.8 2205.17
   662.6    2207   675.1  2210.6   679.3 2211.17   731.1 2212.89   742.2 2215.42
   750.6 2215.83     779 2228.39   834.5 2255.77   922.4 2303.17   923.9 2305.03
#Mann= 4 ,-1,0
       0      .1       0  338.37    .025       0   408.8    .035       0
   635.4      .1       0
Bank Sta=408.8,635.4
XS Rating Curve= 0 ,0
Exp/Cntr=0.3,0.1

Type RM Length L Ch R = 1 ,172600  ,355.2,372.9,391.6
XS GIS Cut Line= 2
     2254929.624      468577.5982254874.19891679469282.831371228
#Sta/Elev= 30
       0  2261.7    39.7 2242.57    83.8 2224.49   111.9 2209.13     136 2207.19
   156.1 2210.07   204.2 2211.33   236.3  2210.3   252.4 2207.91   272.5 2200.51
   308.5 2197.85     457 2197.97   463.9 2200.36     477 2205.69   485.1 2211.19
   489.1 2212.65   507.5 2214.69   533.2 2226.68   553.3 2230.96   573.3 2241.63
   589.4 2253.24   609.5 2273.85   613.5 2276.59   625.5 2280.69   629.5 2286.92
   637.5 2314.72   642.4  2323.5   661.6 2337.64   685.4 2358.08   707.4 2368.26
#Mann= 4 ,-1,0
       0      .1       0     240    .025       0   272.5    .035       0
   463.9      .1       0
Bank Sta=272.5,463.9
XS Rating Curve= 0 ,0
Exp/Cntr=0.3,0.1

Type RM Length L Ch R = 1 ,172227  ,225.8,135.2,85.4
BEGIN DESCRIPTION:
structure xs 4
c/e 0.5/0.7 to correct drawdown
END DESCRIPTION:
XS GIS Cut Line= 3
2254644.54324266468404.3885805432254506.72558999468997.422116271
2254552.66480755 469199.97230277
#Sta/Elev= 30
       0 2272.82    82.9 2241.76     124  2230.9   169.2 2222.23   214.4 2209.67
   230.8 2208.13     276 2208.37   297.5 2206.88   320.9 2209.81   337.6 2211.16
   366.3 2209.51   374.5 2208.17   387.5 2199.72   400.8 2197.41   526.5 2197.44
  532.93 2200.04   542.9 2206.06   559.3 2209.71   579.8 2218.39   597.4 2219.16
   604.5 2221.38   616.5  2231.3   633.5 2242.31   657.8 2260.69   670.2  2279.1
   674.2 2283.88   723.5 2319.14   760.3 2352.85   780.9 2369.24   816.5 2393.23
#Mann= 4 ,-1,0
       0      .1       0   320.9    .025       0   387.5    .035       0
  532.93      .1       0
Bank Sta=387.5,532.93
XS Rating Curve= 0 ,0
Exp/Cntr(USF)=0,0
Exp/Cntr=0.7,0.5

Type RM Length L Ch R = 1 ,172092  ,105,120.7,114.4
BEGIN DESCRIPTION:
structure xs 3
END DESCRIPTION:
XS GIS Cut Line= 6
2253979.09878383468210.4189716412254063.68267674468364.405033092
2254222.00637373468472.8459214382254326.10962654468600.806169685
2254460.57632809468980.3492788952254503.95268343 469195.06223782
#Sta/Elev= 30
       0 2303.06    57.9 2274.18      77 2260.97    89.9 2255.87   135.5 2231.74
   143.5 2229.39     249 2220.14   262.9 2220.74   297.4 2217.85   326.6 2211.85
   378.3 2206.08   562.7    2208   579.6 2204.37   606.5 2207.48  637.18 2199.53
   647.5 2197.14   656.7 2197.09     830 2197.29  839.85 2199.47   863.5  2209.1
   897.9  2223.2   910.6 2224.19   931.8 2222.89   940.1 2226.29   949.1 2235.51
     985 2263.96  1001.3 2281.07  1095.1  2363.5    1136 2387.45  1154.3 2401.36
#Mann= 4 ,-1,0
       0      .1       0  637.18    .035       0  839.85    .025       0
   863.5      .1       0
#XS Ineff= 2 , 0
             603 2225.26     874         2228.03
Permanent Ineff=
       F       F
Bank Sta=637.18,839.85
XS Rating Curve= 0 ,0
Exp/Cntr(USF)=0,0
Exp/Cntr=0.5,0.3

Type RM Length L Ch R = 1 ,171971  ,539.6,618.3,670.5
BEGIN DESCRIPTION:
structure xs 2
c/e 0.5/0.7 to correct drawdown
END DESCRIPTION:
XS GIS Cut Line= 6
2253866.32025995468206.081336107 2254007.2934148468412.119023964
2254137.42248082468501.0405524072254232.85046256468615.987894054
2254356.47307528468971.6740078282254406.35588392469164.698789083
#Sta/Elev= 30
       0 2292.46    52.2 2267.16      91 2240.45   109.5 2229.58   120.1 2225.35
   187.9 2224.33   197.6 2222.24   246.1 2204.54   315.3 2204.72     449 2209.41
   556.7 2209.21     579 2206.21   617.2 2204.17   635.6  2198.9   642.6 2196.94
   807.8 2197.16   817.9  2198.4   841.6 2205.32   858.7 2216.64   874.5 2223.42
   905.2 2228.54     943 2258.36   976.1    2271   985.9 2281.23   996.7 2297.45
  1000.9 2301.06  1046.3 2332.59  1083.5 2362.89  1104.2 2376.46  1132.6 2400.07
#Mann= 5 ,-1,0
       0      .1       0   556.7    .025       0   635.6    .035       0
   817.9      .1       0  1083.5     .12       0
#XS Ineff= 2 , 0
             613 2225.26     840         2228.03
Permanent Ineff=
       F       F
Bank Sta=635.6,817.9
XS Rating Curve= 0 ,0
Exp/Cntr(USF)=0,0
Exp/Cntr=0.7,0.5

Type RM Length L Ch R = 1 ,171353  ,377,387.6,401.6
XS GIS Cut Line= 3
2253844.63208229468195.237247273 2253653.7761188468798.168586474
2253657.56494067468953.731617278
#Sta/Elev= 30
       0 2294.89      37 2268.11    60.8 2245.58    85.9 2227.18    94.3 2224.78
   115.3 2224.24   123.7 2222.74   142.1 2213.84     174 2204.64   199.2 2203.16
   211.8 2199.79   220.2 2201.81     237 2198.34   249.6 2196.06   432.1 2195.94
   455.2 2196.52   471.9 2198.29   479.9 2200.56   505.2 2204.72   518.4 2209.64
   585.2    2211   593.6 2212.27     602 2216.38   618.8 2217.98     623 2219.65
   635.4 2228.71     670 2249.31   694.6  2265.3   715.8  2281.2     788 2331.57
#Mann= 5 ,-1,0
       0      .1       0     190    .025       0     237    .035       0
   471.9    .025       0     520      .1       0
Bank Sta=237,471.9
XS Rating Curve= 0 ,0
Exp/Cntr=0.3,0.1