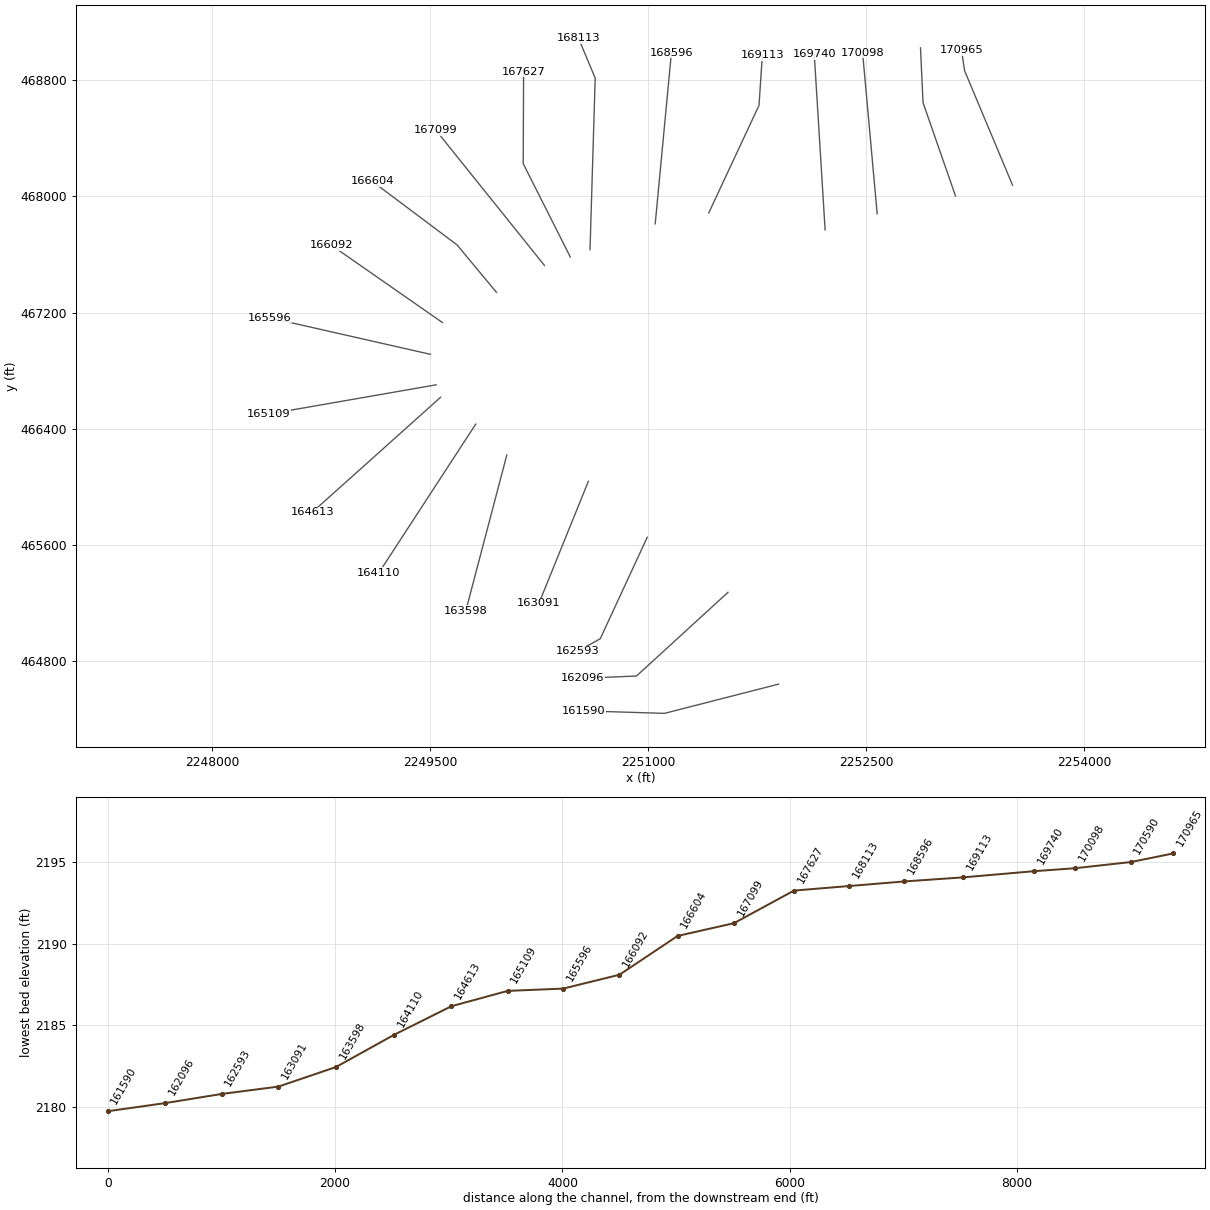
HEC-RAS study GRNBRRRV.prj: GRNBRRRV

--- GRNBRRRV.g01 (geometry) --- (continued)

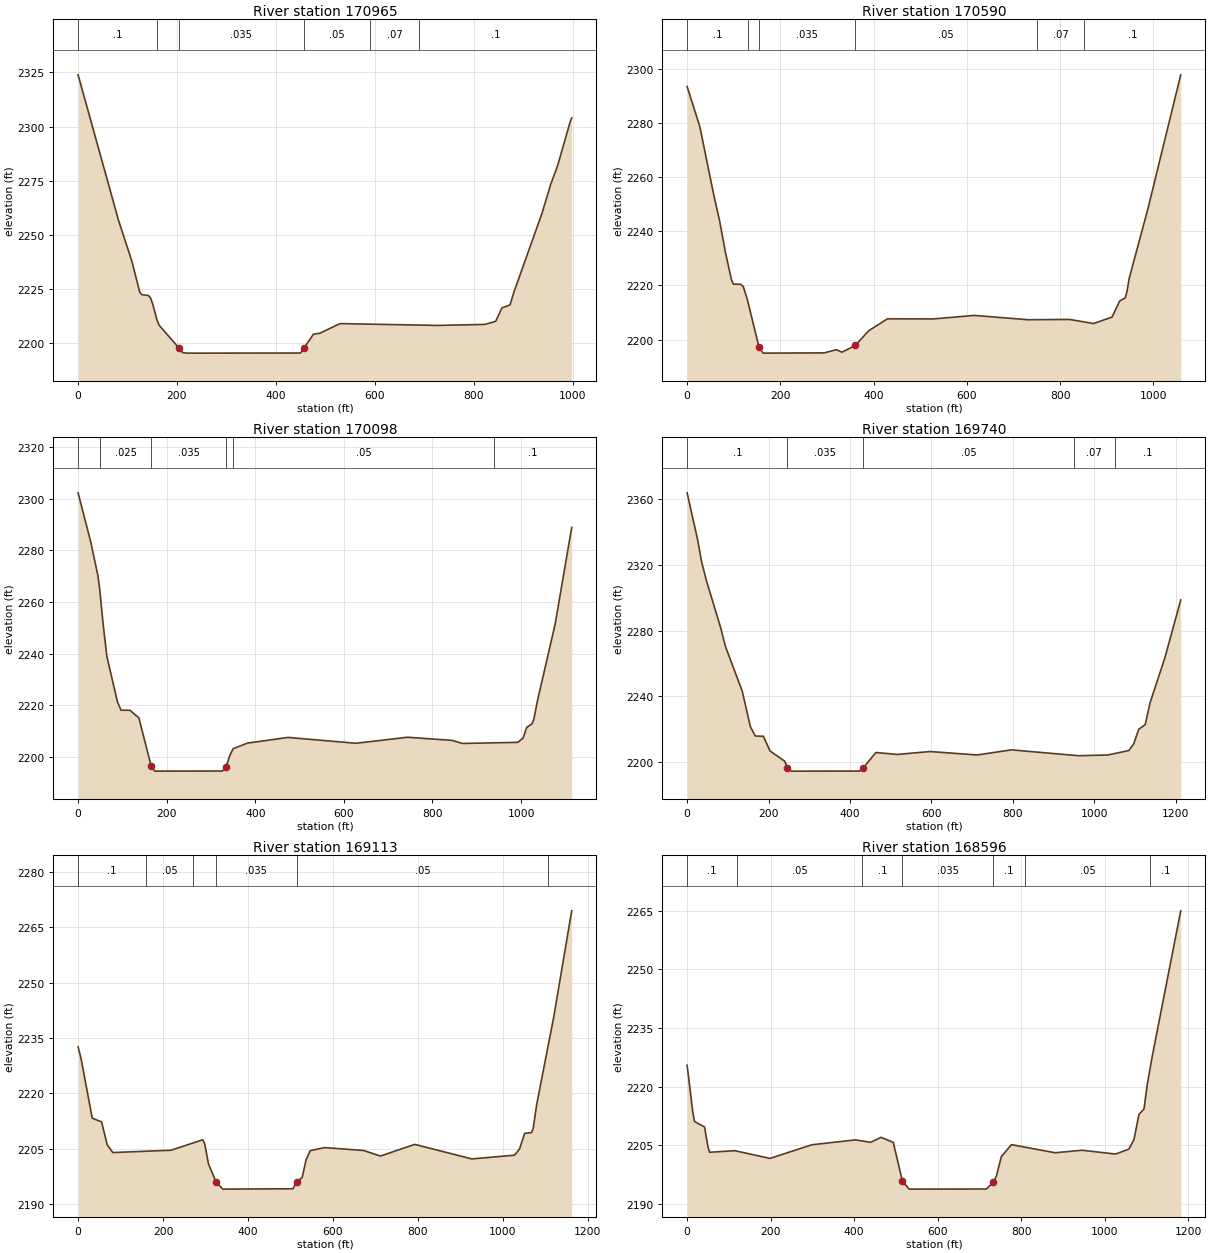
Type RM Length L Ch R = 1 ,170965  ,384,375.2,366.9
XS GIS Cut Line= 3
2253506.29651065 468078.121087862253176.63621008468865.401937249
2253154.94803241469008.543909865
#Sta/Elev= 30
       0 2323.92    81.4 2257.07   109.1 2237.69   124.7 2223.64   129.1 2222.47
   142.1 2222.13   146.4 2221.09   150.8 2218.26   159.4 2210.95   163.8 2208.42
   203.2 2198.12   211.5 2195.78   220.1 2195.53   447.2 2195.57     450 2195.62
   456.8 2197.82     476 2204.25     489 2204.73   529.7 2209.15   727.5 2208.31
   822.9 2208.78   844.6 2210.22   857.3 2216.43   873.5 2217.76   881.6 2223.79
     938 2259.89   955.6 2273.21   969.7 2281.96   994.9 2301.98   998.3 2304.03
#Mann= 6 ,-1,0
       0      .1       0     160    .025       0   203.2    .035       0
   456.8     .05       0     590     .07       0     690      .1       0
Bank Sta=203.2,456.8
XS Rating Curve= 0 ,0
Exp/Cntr(USF)=0,0
Exp/Cntr=0.3,0.1

Type RM Length L Ch R = 1 ,170590  ,521.2,492.1,464.4
XS GIS Cut Line= 3
2253113.90201369468003.4013279542252890.35226484468646.351342791
2252872.88572893469023.813660473
#Sta/Elev= 30
       0 2293.54    27.3 2278.69    56.9 2253.68    69.6 2243.97    82.3 2232.12
      95 2222.17    99.3 2220.49   114.9 2220.46   120.5 2219.55   128.9 2214.99
   154.3 2197.13     163    2195   294.1 2195.09   320.1 2196.26   332.2 2195.35
     361 2197.89   389.6 2203.29   429.6 2207.68   527.5 2207.64   615.9 2208.94
   731.6 2207.34   819.7 2207.46   871.7 2205.94   911.3 2208.33   927.8 2214.31
   939.8 2215.45   943.8 2218.22   947.8 2222.46   987.9 2248.13  1058.6 2297.87
#Mann= 6 ,-1,0
       0      .1       0     130    .025       0   154.3    .035       0
     361     .05       0   750.7     .07       0   850.7      .1       0
Bank Sta=154.3,361
XS Rating Curve= 0 ,0
Exp/Cntr=0.3,0.1

Type RM Length L Ch R = 1 ,170098  ,360.6,357.4,354.7
XS GIS Cut Line= 2
2252574.85727563467880.5614167892252474.51255126468990.436286879
#Sta/Elev= 30
       0 2302.22    28.6 2283.22    44.8 2270.14    48.8 2264.93    56.8 2251.04
    64.9 2239.03      89 2221.32      97 2218.17   117.1 2218.16   137.2 2215.19
   165.1 2196.54   173.3 2194.62   325.9 2194.66   334.5 2196.35   342.1 2200.48
     350  2203.3   382.2 2205.44     474 2207.65   627.2 2205.39   743.6 2207.72
     844 2206.51   868.1 2205.32   992.6 2205.75  1004.7 2207.42  1012.7  2211.5
  1024.8 2212.94  1028.8 2214.52  1036.8 2221.61    1077 2251.45  1114.4 2288.86
#Mann= 6 ,-1,0
       0      .1       0      50    .025       0   165.1    .035       0
   334.5    .025       0     350     .05       0     940      .1       0
Bank Sta=165.1,334.5
XS Rating Curve= 0 ,0
Exp/Cntr=0.3,0.1

Type RM Length L Ch R = 1 ,169740  ,687.1,627.4,570.8
XS GIS Cut Line= 2
 2252216.5831271467770.0878963972252141.92803124468980.286292437
#Sta/Elev= 30
       0 2363.86      26 2335.12    35.2  2322.3    47.2 2310.59    82.6  2281.6
    93.9 2270.49   135.3 2243.18   155.4 2221.49   167.4 2215.82   187.4 2215.67
   203.5 2206.74   239.5 2200.54   246.3 2196.62   255.6 2194.44   423.9 2194.47
   431.9 2196.26   463.8 2205.78   516.1  2204.6   596.5 2206.37   712.4 2204.27
   796.6 2207.38   960.9 2203.83  1033.1 2204.26  1085.2 2206.98  1097.2 2211.17
  1109.2 2219.84  1125.2 2222.78  1137.2 2236.08  1173.5 2263.37  1212.5 2298.62
#Mann= 5 ,-1,0
       0      .1       0   246.3    .035       0   431.9     .05       0
     950     .07       0    1050      .1       0
Bank Sta=246.3,431.9
XS Rating Curve= 0 ,0
Exp/Cntr(USF)=0,0
Exp/Cntr=0.3,0.1

Type RM Length L Ch R = 1 ,169113  ,475.9,517.6,560.8
XS GIS Cut Line= 3
2251416.05995038467887.043658396 2251761.8018075468627.699606761
 2251784.6768944468971.657149456
#Sta/Elev= 30
       0 2232.62     6.8 2229.57    33.3 2213.28    55.3 2212.29    68.6 2206.07
    81.8 2203.98   218.7  2204.6   293.7 2207.44   298.1 2206.33   306.9 2200.93
   324.6    2196   340.7 2194.06   505.6 2194.16   514.4 2195.93   527.7 2197.28
   536.5 2201.91   546.4  2204.5   580.6 2205.31   671.7 2204.54   711.9 2203.03
   792.5 2206.19   927.1 2202.25  1027.3 2203.26  1039.3 2204.94  1051.4 2209.18
  1067.4 2209.37  1071.4  2210.5  1079.4 2216.83  1119.5 2240.53  1162.1 2269.49
#Mann= 6 ,-1,0
       0      .1       0     160     .05       0     270      .1       0
   324.6    .035       0   514.4     .05       0 1107.38      .1       0
Bank Sta=324.6,514.4
XS Rating Curve= 0 ,0
Exp/Cntr=0.3,0.1

Type RM Length L Ch R = 1 ,168596  ,474.9,482.5,493.8
XS GIS Cut Line= 2
2251047.53013041467811.5823848792251158.85231679468988.796217544
#Sta/Elev= 30
       0 2225.46    13.7 2213.44    17.7 2211.12    41.8 2209.68    49.8 2204.66
    53.8 2203.23   114.1 2203.64   198.5 2201.66   298.9 2205.15   403.4  2206.4
   439.5 2205.77   464.6 2207.05   493.9 2205.76   515.8 2195.81     532 2193.81
   716.8 2193.84   733.2 2195.56   740.9 2197.15   752.9 2202.16     777 2205.18
   881.5 2203.11   946.2 2203.75  1026.6 2202.78  1058.3 2204.05  1070.5 2206.49
  1082.4 2212.91  1094.5 2214.29  1102.5  2220.7  1114.5 2227.91  1182.5 2264.95
#Mann= 7 ,-1,0
       0      .1       0     120     .05       0     420      .1       0
   515.8    .035       0   733.2      .1       0     810     .05       0
    1110      .1       0
Bank Sta=515.8,733.2
XS Rating Curve= 0 ,0
Exp/Cntr=0.3,0.1

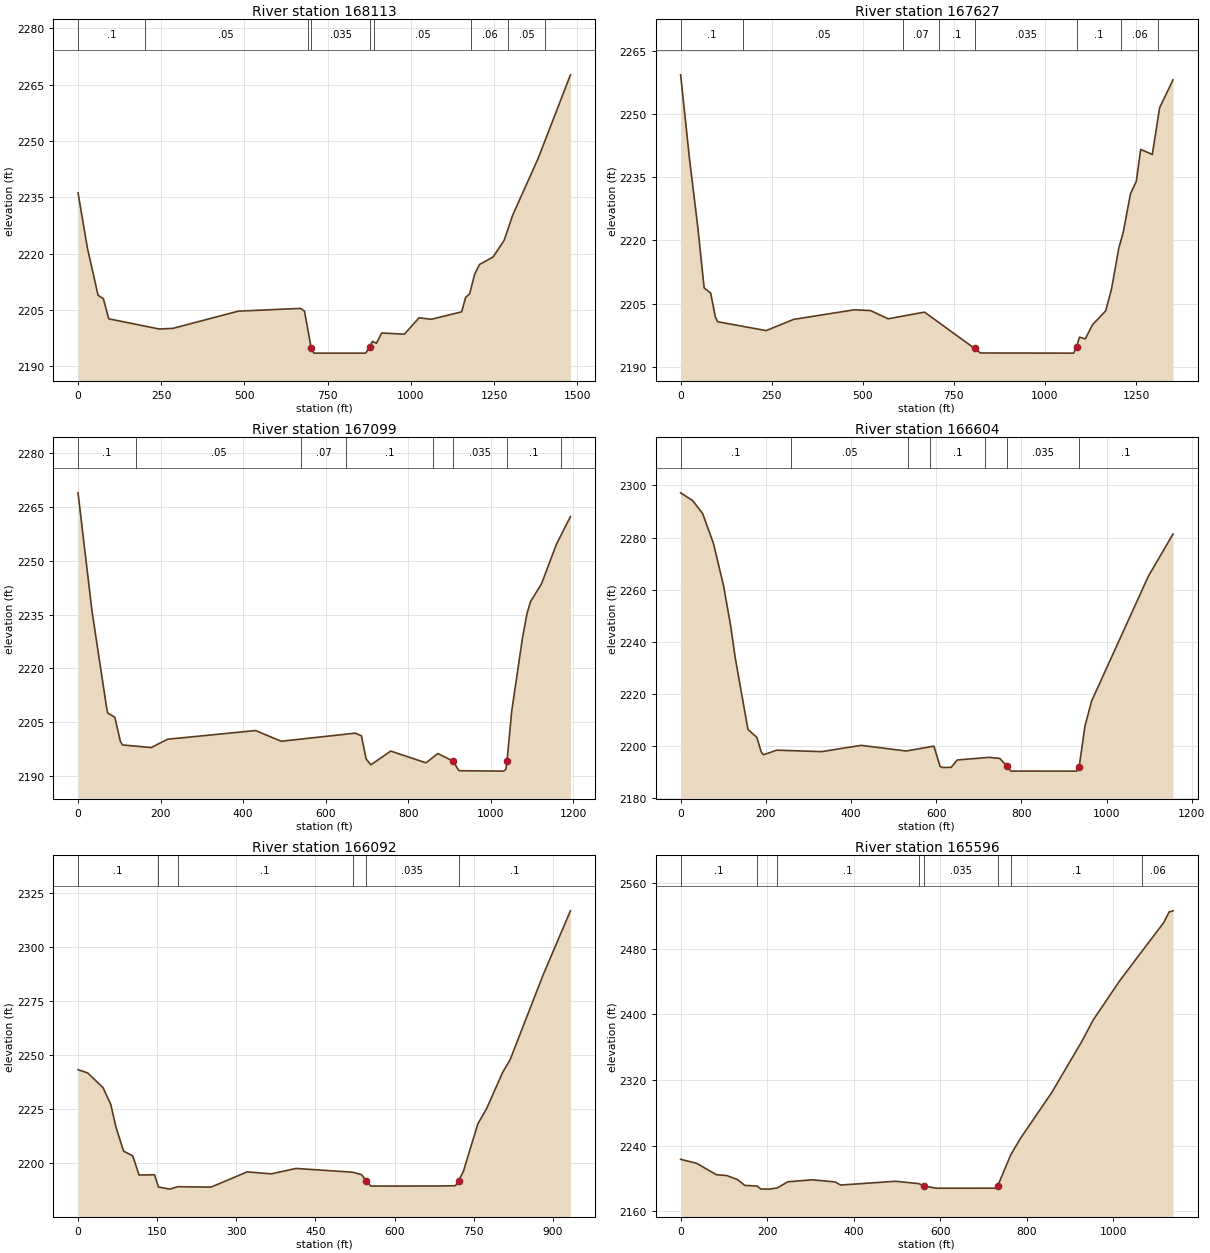
Type RM Length L Ch R = 1 ,168113  ,480.8,486.2,493.3
XS GIS Cut Line= 3
     2250598.897467633.0431361752250634.55207926468815.128302667
2250520.09875764469089.212907101
#Sta/Elev= 30
       0 2236.19    28.1 2221.53    60.2 2208.92    76.2 2208.02    92.2 2202.66
   244.2 2199.95     285 2200.12   481.6  2204.7   668.4 2205.44   680.4 2204.71
   700.5 2194.96   708.5 2193.53   864.5 2193.53   876.5 2195.19   884.5 2196.66
   896.5 2196.14   912.6 2198.89   980.6 2198.57  1024.6 2202.93  1061.9 2202.54
  1152.7 2204.52  1164.7 2208.36  1176.7 2209.34  1192.1 2214.63  1206.5 2217.12
  1247.2 2219.12  1280.2 2223.51  1306.2 2230.26    1383 2245.44  1479.6 2267.59
#Mann= 9 ,-1,0
       0      .1       0     200     .05       0     690    .025       0
   700.5    .035       0   876.5    .025       0     890     .05       0
    1180     .06       0 1292.62     .05       0 1402.62      .1       0
Bank Sta=700.5,876.5
XS Rating Curve= 0 ,0
Exp/Cntr=0.3,0.1

Type RM Length L Ch R = 1 ,167627  ,428.1,528.2,603.5
XS GIS Cut Line= 3
2250463.18870015467583.4540152842250139.20481151468226.066686962
2250141.88236431468857.969147445
#Sta/Elev= 30
       0 2259.33    24.3 2239.45    46.7 2223.51    64.6 2208.74    82.6  2207.5
    95.5 2201.78   101.8  2200.7   234.9  2198.6   310.3 2201.26   476.8 2203.54
   521.6 2203.35   569.4  2201.4   669.4 2202.99   806.8 2194.37   822.8 2193.28
  1078.8 2193.25  1086.8 2194.73  1094.8 2197.04  1110.8 2196.64  1130.8 2200.02
  1166.8 2203.28  1182.8 2208.49  1202.8 2218.18  1214.8 2221.87  1234.8 2231.08
  1250.8 2234.04  1262.8 2241.61  1294.8 2240.43  1314.8 2251.51  1351.6 2258.14
#Mann= 8 ,-1,0
       0      .1       0     170     .05       0     610     .07       0
     710      .1       0   806.8    .035       0  1086.8      .1       0
 1209.66     .06       0 1309.66      .1       0
Bank Sta=806.8,1086.8
XS Rating Curve= 0 ,0
Exp/Cntr(USF)=0,0
Exp/Cntr=0.3,0.1

Type RM Length L Ch R = 1 ,167099  ,470.1,495,516.5
XS GIS Cut Line= 2
2250285.33654703467525.1490802012249538.87995673468455.874856893
#Sta/Elev= 30
       0    2269    33.8 2235.99    69.1 2209.09      72 2207.46    89.1 2206.33
   102.6 2199.57   107.7 2198.56   177.3 2197.84   217.1 2200.16   430.2 2202.59
   492.3  2199.6   671.7 2201.86   686.6 2201.14     698 2194.68   709.4 2193.01
   757.7 2196.85   843.1 2193.57   871.7 2196.16   908.5 2194.07     923 2191.37
  1031.2 2191.25  1036.6 2191.77  1039.4 2194.01  1050.8    2208  1076.8 2228.39
  1087.8 2235.25  1096.3 2238.57    1123 2243.58  1158.9 2254.57  1193.1 2262.36
#Mann= 8 ,-1,0
       0      .1       0     140     .05       0     540     .07       0
     650      .1       0     860    .025       0   908.5    .035       0
  1039.4      .1       0    1170     .06       0
Bank Sta=908.5,1039.4
XS Rating Curve= 0 ,0
Exp/Cntr=0.3,0.1

Type RM Length L Ch R = 1 ,166604  ,508,511.9,515.2
XS GIS Cut Line= 3
2249955.35983267467339.5309809532249684.02083574467666.458152043
2249099.25863993468105.475099248
#Sta/Elev= 30
       0 2297.16    28.1 2294.19    51.7 2289.22    77.3 2277.65   100.9 2261.49
   117.7 2245.97   128.4 2233.75   158.1 2206.46   178.9 2203.42   189.3 2197.79
   194.5 2196.73   225.7 2198.51   330.7 2197.94   423.8 2200.35   529.5 2198.19
   594.7 2200.05   609.3 2192.23   615.3 2191.86   635.3 2191.92   649.5 2194.74
   724.8 2195.75   749.2 2195.34   766.7 2192.34   775.2 2190.48   929.9 2190.47
   935.7 2192.15   949.5 2207.84   964.9 2217.32  1098.1 2265.15  1156.1 2281.37
#Mann= 7 ,-1,0
       0      .1       0     260     .05       0  534.86     .07       0
  584.86      .1       0  714.86    .025       0   766.7    .035       0
   935.7      .1       0
Bank Sta=766.7,935.7
XS Rating Curve= 0 ,0
Exp/Cntr=0.3,0.1

Type RM Length L Ch R = 1 ,166092  ,441,495.6,523.4
XS GIS Cut Line= 2
2249583.09082632467131.8880184632248817.53806232467665.507440852
#Sta/Elev= 30
       0 2243.28    18.2 2241.79    47.4 2234.97    62.1  2227.2    71.8 2216.78
    86.3 2205.63   103.6 2203.48   115.7 2194.61     145 2194.72   152.4 2189.06
   174.2 2188.09   188.8 2189.22   252.2 2189.02   320.5 2196.06     366 2195.14
   413.1 2197.64   520.2 2195.91   537.4 2194.77     546 2191.95   554.7  2189.5
   681.3 2189.53   715.4 2189.68   721.3 2192.05   730.1 2196.13   757.7 2218.25
   773.9 2225.06   804.6 2241.97     819 2247.96   881.2 2286.94   933.2 2316.68
#Mann= 6 ,-1,0
       0      .1       0   152.4    .045       0   188.8      .1       0
   520.2    .025       0     546    .035       0   721.3      .1       0
Bank Sta=546,721.3
XS Rating Curve= 0 ,0
Exp/Cntr=0.3,0.1

Type RM Length L Ch R = 1 ,165596  ,432.3,487.5,513.2
XS GIS Cut Line= 2
2249500.56688229466912.957049624     2248391.224      467165.073
#Sta/Elev= 30
       0 2223.57    37.3 2218.63    82.4 2204.88   107.1  2203.7   131.7 2198.79
   148.1 2191.78   176.8 2190.95     185  2187.4   205.5 2187.24   223.2  2188.7
   247.8 2196.17   303.9 2198.61   357.3 2195.99   369.6 2192.22   496.7 2196.82
   550.1 2193.96   562.9 2190.97   591.1 2188.34   726.5 2188.38   732.5 2191.06
   762.6 2228.89   783.9 2248.07   857.7 2305.16   927.5 2367.68   953.1 2393.25
  1013.6 2440.42  1066.9 2477.75  1116.1 2511.83  1128.5 2524.83  1137.6 2526.25
#Mann= 8 ,-1,0
       0      .1       0   176.8     .04       0   223.2      .1       0
   550.1     .07       0   562.9    .035       0   732.5    .025       0
   762.6      .1       0  1066.9     .06       0
Bank Sta=562.9,732.5
XS Rating Curve= 0 ,0
Exp/Cntr=0.3,0.1

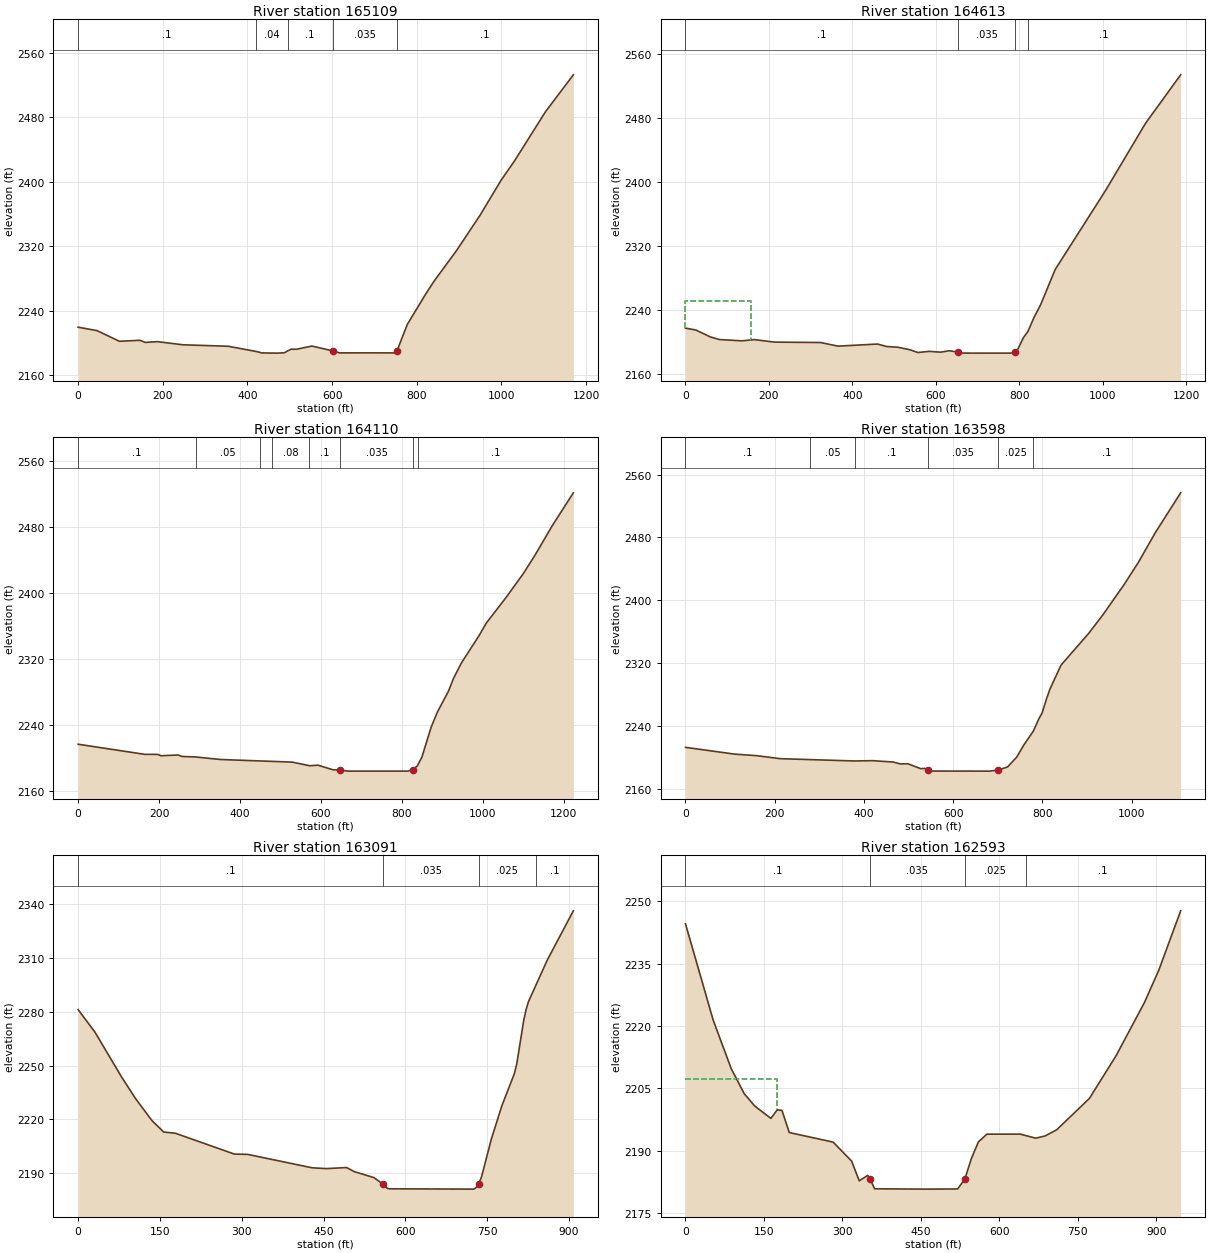
Type RM Length L Ch R = 1 ,165109  ,433.3,495.3,534.5
XS GIS Cut Line= 2
2249540.23196307466702.837925564     2248387.697      466501.767
#Sta/Elev= 30
       0  2219.3    44.7 2215.03    97.5 2201.79   146.2 2203.04   158.4  2200.4
   186.8 2201.36   247.7 2197.44   354.1 2195.65   419.8 2189.24   434.5 2187.34
   471.1  2187.1   487.3 2187.59   494.8 2189.86   503.5    2192   515.7 2191.88
   552.3 2195.88     601 2189.99   617.2 2187.44   747.2 2187.38   751.2 2188.09
  753.38 2190.17   777.7 2222.77   820.3 2259.83   841.6 2276.99   893.5 2314.11
   950.2  2358.9   998.9 2401.53  1031.4 2426.17  1104.3 2487.04  1169.9 2532.68
#Mann= 5 ,-1,0
       0      .1       0   419.8     .04       0   494.8      .1       0
     601    .035       0  753.38      .1       0
Bank Sta=601,753.38
XS Rating Curve= 0 ,0
Exp/Cntr=0.3,0.1

Type RM Length L Ch R = 1 ,164613  ,472.8,503.6,523.9
XS GIS Cut Line= 2
2249570.80337911466617.178435087     2248687.589      465825.204
#Sta/Elev= 30
       0 2217.38      25 2214.96    59.9  2206.3    81.2 2203.12     135 2201.49
   164.7 2203.03   213.1 2199.91   323.5  2199.4   365.5 2194.89   460.2  2197.5
   481.7 2194.42   508.6 2193.54   537.2 2190.43   556.9 2186.93   583.8 2188.38
   611.1 2187.35   632.1 2189.16   653.6 2187.32   664.7 2186.19   778.9 2186.16
   789.3 2187.48   796.9 2191.74   809.4 2205.31   820.5 2213.34   834.7 2230.37
   850.8 2246.51   885.6 2290.42  1006.6 2389.28  1102.4 2473.16  1186.3 2533.44
#Mann= 4 ,-1,0
       0      .1       0   653.6    .035       0   789.3    .025       0
     820      .1       0
#XS Ineff= 2 , 0
          156.68 2250.92
Permanent Ineff=
       F       F
Bank Sta=653.6,789.3
XS Rating Curve= 0 ,0
Exp/Cntr=0.3,0.1

Type RM Length L Ch R = 1 ,164110  ,467.4,512,535.1
XS GIS Cut Line= 2
2249812.69985113466432.254043859     2249144.968      465406.518
#Sta/Elev= 30
       0 2217.02   164.5 2204.76   196.3 2204.72     205 2203.08   247.1 2203.99
   256.6  2202.2     290  2201.6   352.1  2198.5   528.7 2195.35   572.8 2190.91
   592.4 2191.65   629.9 2186.06     648 2185.68   667.1 2184.41     815 2184.41
   826.5 2186.31   838.1 2190.58   849.6 2201.41   872.3  2237.5   888.1 2256.24
   915.3 2281.34   927.7 2296.84   947.9 2316.13   990.8 2348.65  1008.6 2363.82
  1058.5 2395.53  1101.4 2424.72  1130.1    2447    1173 2482.94  1223.9 2521.83
#Mann= 8 ,-1,0
       0      .1       0     290     .05       0     450      .1       0
     480     .08       0     570      .1       0     648    .035       0
   826.5    .025       0     840      .1       0
Bank Sta=648,826.5
XS Rating Curve= 0 ,0
Exp/Cntr=0.3,0.1

Type RM Length L Ch R = 1 ,163598  ,522.5,506.8,497
XS GIS Cut Line= 2
2250026.33984478466219.270354302      2249744.09      465145.866
#Sta/Elev= 30
       0 2212.71   109.7 2204.12   159.3  2202.1   213.1 2198.28   378.5 2195.37
   419.4 2195.75   465.4 2194.02   481.9  2191.6   498.5 2191.82   527.4 2185.53
   535.7 2185.97   543.3 2183.98   553.7 2182.53   681.4 2182.43     701 2183.81
   721.8 2187.72   742.5 2200.32     759 2216.26   779.6 2233.28   792.1 2249.08
   799.3 2256.44   809.1 2274.28   816.9 2286.84   841.8 2317.47   904.1 2358.08
   936.9 2382.45   982.7 2419.64  1015.2 2448.27  1052.7 2485.73  1109.9 2536.81
#Mann= 6 ,-1,0
       0      .1       0     280     .05       0     380      .1       0
   543.3    .035       0     701    .025       0     780      .1       0
Bank Sta=543.3,701
XS Rating Curve= 0 ,0
Exp/Cntr=0.3,0.1

Type RM Length L Ch R = 1 ,163091  ,504,498.1,493.2
XS GIS Cut Line= 2
2250587.75447836466038.5191431072250246.95358396465196.928143107
#Sta/Elev= 30
       0 2281.15    30.9 2268.59    79.1 2243.91   105.1  2231.7   135.2 2219.42
   156.8 2213.03   178.4 2212.33   286.3 2200.75   310.9 2200.57   428.7 2193.12
   454.6 2192.65   492.2 2193.25   506.4 2190.97   542.4 2187.64   558.1 2184.15
   566.8 2181.68   571.1 2181.41   725.6 2181.23   730.8 2182.37   734.2 2183.98
   739.4 2187.82   757.4 2208.82   776.8 2227.53   799.8 2245.48   804.1 2250.71
   817.1 2275.32   821.4 2281.24   825.7 2285.59   860.2 2308.75     908 2336.17
#Mann= 4 ,-1,0
       0      .1       0   558.1    .035       0   734.2    .025       0
     840      .1       0
Bank Sta=558.1,734.2
XS Rating Curve= 0 ,0
Exp/Cntr=0.3,0.1

Type RM Length L Ch R = 1 ,162593  ,549.6,496.7,458.6
XS GIS Cut Line= 3
     2250992.892      465653.2822250669.36026564464954.097167002
2250515.68565205 464868.19729198
#Sta/Elev= 30
       0 2244.55      53 2221.38    87.4 2209.75   112.1 2203.75   132.3 2200.76
   163.2 2197.79   175.4 2199.83   184.4 2199.71   198.4 2194.38   282.2 2192.08
   317.5 2187.53   332.1 2182.78   348.3 2184.08   352.7 2183.28   361.5 2180.86
   458.1 2180.78   520.2 2180.82     534 2183.22   546.6 2188.17   559.9 2192.14
   576.1 2193.99   639.9    2194   669.5 2193.03   687.6 2193.57   709.7 2195.06
     772 2202.57   823.1 2212.84   877.2 2225.62   904.7 2233.39   946.5 2247.67
#Mann= 4 ,-1,0
       0      .1       0   352.7    .035       0     534    .025       0
     650      .1       0
#XS Ineff= 2 , 0
          175.77 2207.35
Permanent Ineff=
       F       F
Bank Sta=352.7,534
XS Rating Curve= 0 ,0
Exp/Cntr=0.3,0.1

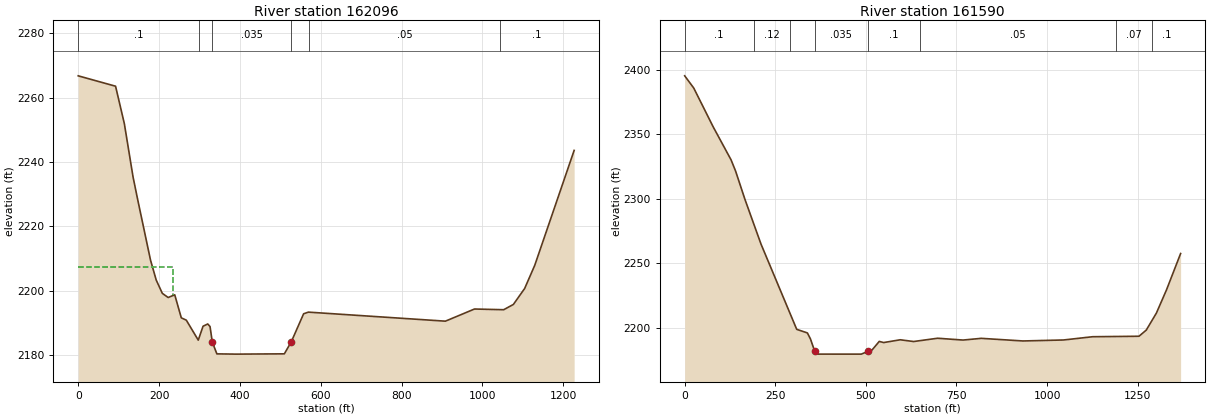
Type RM Length L Ch R = 1 ,162096  ,569.6,506.2,466.3
XS GIS Cut Line= 3
     2251548.301       465273.712250918.37267592464697.052098331
2250545.90690017464682.199527987
#Sta/Elev= 30
       0 2266.77    92.4 2263.54   114.1 2251.91   135.7 2235.29   146.6  2228.6
   178.8 2209.49     193 2203.24   208.1 2199.12   222.5 2197.83   238.8 2198.67
     255 2191.51   267.4 2190.78     297 2184.57   308.8 2188.89   320.4  2189.6
   326.1 2188.79   331.7 2183.98     343  2180.3   390.6 2180.22   509.9 2180.31
   527.1 2184.06   557.6 2192.77   569.5 2193.28   908.3 2190.47   980.3 2194.25
  1052.4 2194.03  1076.4 2195.66  1104.4 2200.64  1129.3 2207.83  1226.8 2243.58
#Mann= 6 ,-1,0
       0      .1       0     300    .025       0   331.7    .035       0
   527.1      .1       0     570     .05       0 1044.02      .1       0
#XS Ineff= 2 , 0
          235.04 2207.39
Permanent Ineff=
       F       F
Bank Sta=331.7,527.1
XS Rating Curve= 0 ,0
Exp/Cntr=0.3,0.1

Type RM Length L Ch R = 1 ,161590  ,565.2,496.9,445.3
XS GIS Cut Line= 3
     2251896.261      464641.4932251111.15647742 464440.00702966
2250553.35391863 464457.42029198
#Sta/Elev= 30
       0 2395.19    24.9 2385.79    78.6 2355.73   128.1 2330.09   140.5 2321.46
   166.3 2299.54   210.6 2264.95   309.2 2198.91   338.6 2196.14     347 2191.55
   358.5 2182.25   367.6 2179.73   487.4 2179.72   505.2 2181.77   516.3 2182.66
   536.9 2189.55   549.3 2188.68   594.8 2190.82   631.9 2189.48     698 2192.02
   768.2 2190.61   818.5 2191.94   933.6 2189.91  1045.6 2190.67  1125.7 2193.19
  1253.7 2193.56  1273.8 2198.33  1301.8 2211.52  1329.8 2229.57  1368.6  2257.6
#Mann= 8 ,-1,0
       0      .1       0     190     .12       0     290      .1       0
   358.5    .035       0   505.2      .1       0     650     .05       0
 1190.55     .07       0 1290.55      .1       0
Bank Sta=358.5,505.2
XS Rating Curve= 0 ,0
Exp/Cntr=0.3,0.1