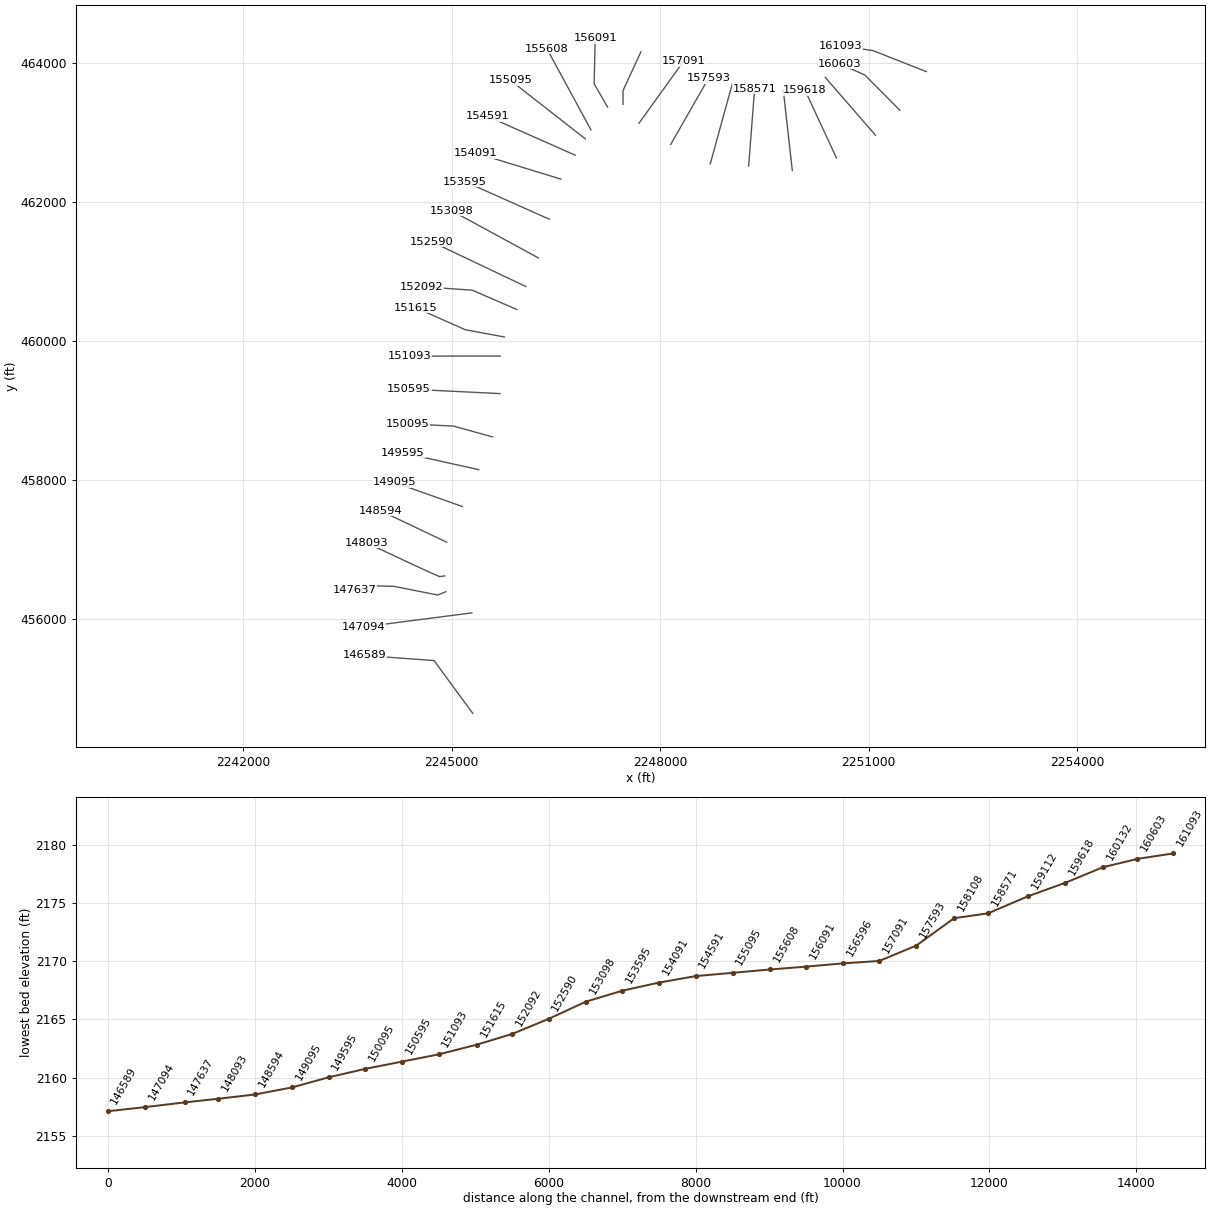
HEC-RAS study GRNBRRRV.prj: GRNBRRRV

--- GRNBRRRV.g01 (geometry) --- (continued)

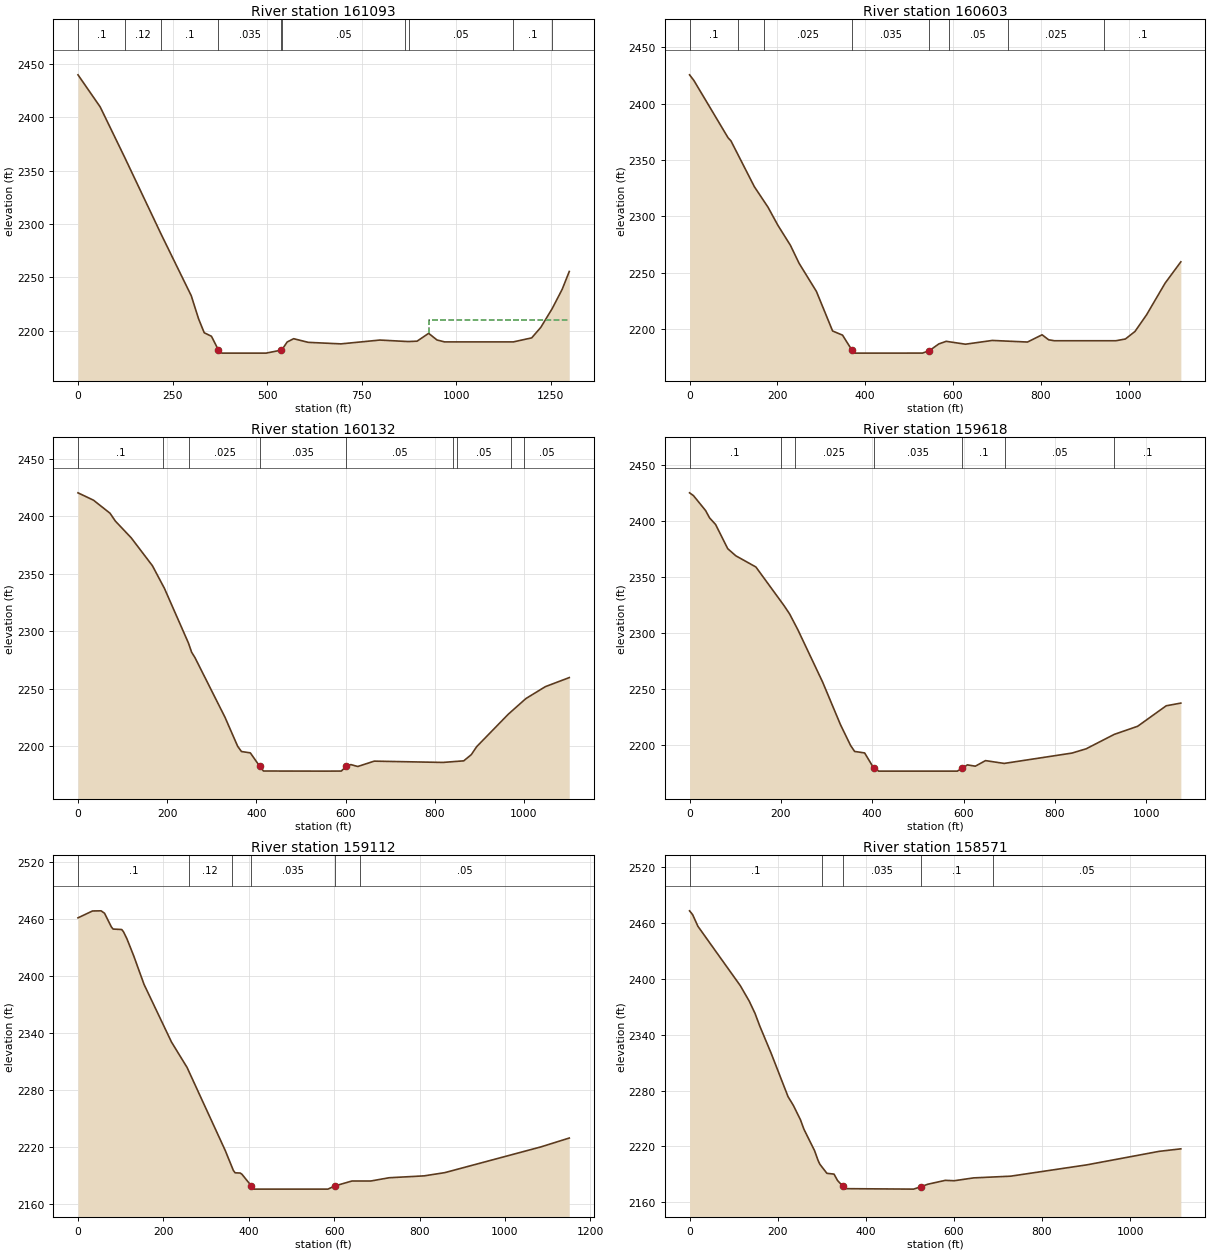
Type RM Length L Ch R = 1 ,161093  ,532.9,490.4,446.4
XS GIS Cut Line= 3
     2251826.822      463878.0012251060.28297425 464180.28440819
 2250589.7212914464247.599186383
#Sta/Elev= 30
       0 2439.46    58.7 2409.48   123.2 2362.52   220.4 2290.09   299.5 2232.97
     319 2211.28   333.9 2198.29     353 2195.02   371.5 2182.12   380.7 2179.25
   497.3 2179.25     536 2181.94   540.3 2182.88   553.2 2189.65   570.4 2192.74
   609.1 2189.32   695.6  2187.9   798.3 2191.47   863.8 2190.24   874.4 2190.09
   896.8 2190.42   927.4 2197.76   949.4 2191.56   969.6 2189.75  1151.4 2189.75
  1199.9 2193.51  1223.9 2203.29    1254  2220.8  1280.7 2239.04  1299.3 2255.58
#Mann= 10 ,-1,0
       0      .1       0   123.2     .12       0   220.4      .1       0
   371.5    .035       0     536    .025       0   540.3     .05       0
   863.8    .025       0   874.4     .05       0  1151.4      .1       0
    1254     .05       0
#XS Ineff= 2 , 0
       0                   927.4       0    2210
Permanent Ineff=
       F       F
Bank Sta=371.5,536
XS Rating Curve= 0 ,0
Exp/Cntr=0.3,0.1

Type RM Length L Ch R = 1 ,160603  ,477.4,470.5,463.4
XS GIS Cut Line= 3
     2251445.941       463322.252250942.47065111463829.524991566
2250572.62667051463992.746739181
#Sta/Elev= 30
       0 2425.42     9.8 2420.46    87.7 2369.66    94.3 2366.87   147.6 2326.27
   178.7  2308.1   201.2 2292.08   229.6 2274.43   249.4 2258.47     289 2233.43
   325.8 2198.41   348.4 2194.72   370.4 2181.13   377.3 2178.78   530.6 2178.81
   546.4 2181.04   567.7 2186.93   584.6 2189.24   628.4 2186.69   689.6 2190.02
   769.7 2188.61     803 2195.04   817.8 2190.61   830.9 2189.75     971 2189.75
   992.7 2191.31  1014.5 2197.97  1040.8 2212.66  1083.2 2240.83    1119  2259.7
#Mann= 8 ,-1,0
       0      .1       0     110     .12       0     170    .025       0
   370.4    .035       0   546.4      .1       0     590     .05       0
  724.71    .025       0  944.71      .1       0
Bank Sta=370.4,546.4
XS Rating Curve= 0 ,0
Exp/Cntr=0.3,0.1

Type RM Length L Ch R = 1 ,160132  ,543.2,514.2,477.5
XS GIS Cut Line= 2
2251095.24374892 462963.023131752250373.07591873463795.086066535
#Sta/Elev= 30
       0 2420.56    34.9 2414.12    71.8  2402.8      84 2395.86   119.4 2381.34
     167 2357.01   193.9 2337.28   247.6 2289.79   254.9 2281.66   262.4 2276.94
   329.8 2224.91   358.1 2199.72   366.6 2195.14   386.5 2193.98   407.4 2182.38
     416 2178.16   553.7 2178.06   590.5 2178.12     602 2182.31   611.9 2183.75
   627.5  2182.1   664.4 2186.76   818.5 2185.64   865.1 2187.01   882.1 2192.44
     894 2199.33   964.9 2227.61  1004.6 2241.31  1048.2 2251.68  1101.8 2259.57
#Mann= 9 ,-1,0
       0      .1       0     190     .12       0     250    .025       0
   407.4    .035       0     602     .05       0     840      .1       0
     850     .05       0     970      .1       0    1000     .05       0
Bank Sta=407.4,602
XS Rating Curve= 0 ,0
Exp/Cntr(USF)=0,0
Exp/Cntr=0.3,0.1

Type RM Length L Ch R = 1 ,159618  ,539.7,505.4,463.9
XS GIS Cut Line= 2
2250535.30202551462633.3378179672250082.63885659463609.311008768
#Sta/Elev= 30
       0 2424.86     8.6 2422.36    35.1 2409.08    43.9 2402.49    57.1 2396.59
    83.6 2375.05   101.2 2368.74   145.3 2358.72   207.1 2324.19   219.1 2316.87
   237.2 2302.75   291.4 2256.12   330.5 2218.11   352.6 2199.62   361.4 2194.28
   383.4 2192.93   402.9 2179.68   414.3 2176.72   586.3 2176.72   596.9 2179.26
   608.3 2182.28   625.8 2181.13     648 2186.09     689 2183.59   837.6 2192.83
   868.5 2196.63     930 2209.49   981.2 2216.72  1043.7 2234.97  1075.8 2237.39
#Mann= 7 ,-1,0
       0      .1       0     200     .12       0     230    .025       0
   402.9    .035       0   596.9      .1       0     690     .05       0
     930      .1       0
Bank Sta=402.9,596.9
XS Rating Curve= 0 ,0
Exp/Cntr(USF)=0,0
Exp/Cntr=0.3,0.1

Type RM Length L Ch R = 1 ,159112  ,560,541.1,516.9
XS GIS Cut Line= 2
2249899.48034893462455.4124105292249771.26939357463598.844808331
#Sta/Elev= 30
       0 2461.16      34 2468.37    54.1 2468.54    62.2 2465.98    78.3 2451.51
    82.3 2449.35   102.4 2448.85   106.4 2446.63   114.5 2439.25   130.6 2421.07
   154.7 2391.12   219.1 2330.33   255.4 2303.74   344.8 2216.34     364 2195.15
   368.1 2192.75   380.1 2192.48   384.2 2191.13   406.3 2178.84   406.3  2178.8
   412.3 2175.57   585.4 2175.58   601.5 2178.92   641.8 2184.13     686 2184.13
   728.4 2187.53   810.8 2189.54   859.1 2192.93  1084.5 2220.07  1150.6 2229.36
#Mann= 6 ,-1,0
       0      .1       0     260     .12       0     360    .025       0
   406.3    .035       0   601.5      .1       0     660     .05       0
Bank Sta=406.3,601.5
XS Rating Curve= 0 ,0
Exp/Cntr(USF)=0,0
Exp/Cntr=0.3,0.1

Type RM Length L Ch R = 1 ,158571  ,481.3,462.8,439.3
XS GIS Cut Line= 2
2249271.50832268462518.2096131542249357.85447629463630.243409643
#Sta/Elev= 30
       0 2472.91       7 2468.79      19  2456.3   115.1 2392.64   135.4 2376.02
   148.6 2362.82   159.4 2349.24   185.2 2320.02   223.6 2273.43   235.7 2263.97
   251.7 2248.67   259.7 2238.41   283.8  2215.4   291.8 2204.93   295.9 2200.76
   311.9 2191.07     328 2190.22     336 2183.36   348.22177.107     356  2174.6
   508.5 2174.11   525.32176.661   540.6 2179.34   580.7 2183.54   600.8 2183.12
   644.9 2186.17   728.9 2188.01   901.7 2200.15  1066.2 2214.68  1115.4 2217.36
#Mann= 5 ,-1,0
       0      .1       0     300    .025       0   348.2    .035       0
   525.3      .1       0     690     .05       0
Bank Sta=348.2,525.3
XS Rating Curve= 0 ,0
Exp/Cntr(USF)=0,0
Exp/Cntr=0.3,0.1

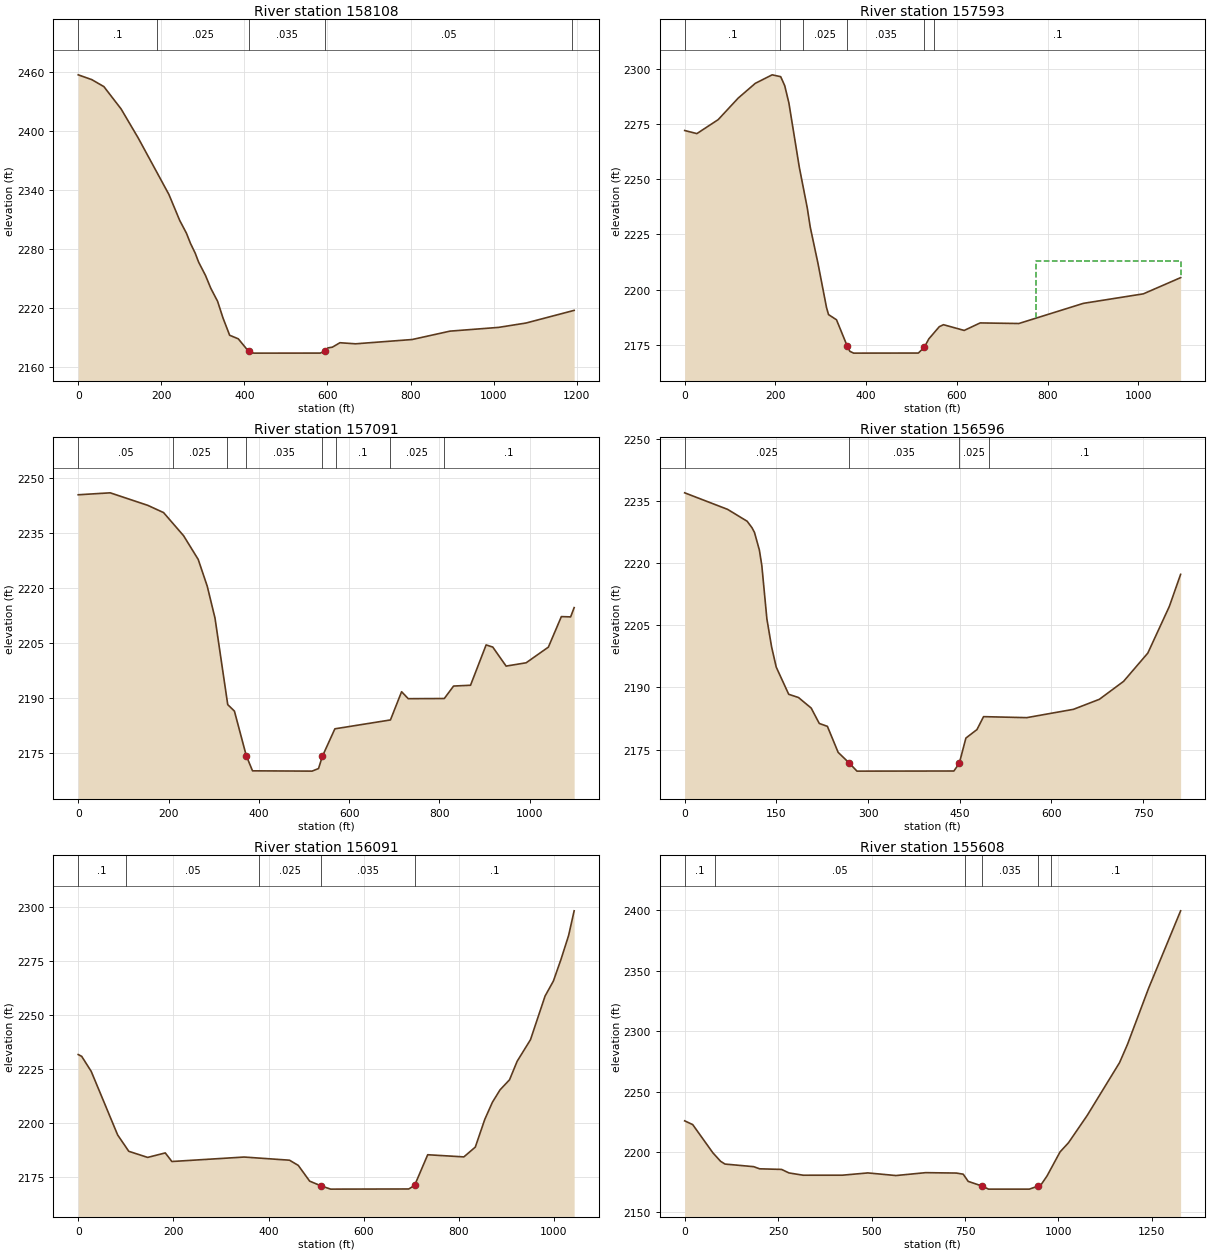
Type RM Length L Ch R = 1 ,158108  ,542.4,515.4,488.7
XS GIS Cut Line= 2
 2248719.4162496462549.6082144662249036.01881283463700.890262597
#Sta/Elev= 30
       0 2457.42    32.7 2452.52    61.8 2445.41   103.3 2422.61   144.8 2392.78
   218.3  2335.5   244.3 2309.03   260.6 2295.92   270.3 2285.56   281.7 2275.58
   289.9 2266.47   306.5 2252.83   319.1  2239.9   335.6 2226.48   348.4 2209.74
   364.6 2191.91   385.4 2188.27   410.2 2175.51   422.7 2173.69   582.7 2173.72
  593.982175.765   601.1 2179.02     612 2179.78   630.1 2184.29   667.5 2183.19
   803.9 2187.55     895  2196.1  1011.8 2199.92  1078.2 2204.38    1194 2217.28
#Mann= 5 ,-1,0
       0      .1       0     190    .025       0   410.2    .035       0
  593.98     .05       0    1190      .1       0
Bank Sta=410.2,593.98
XS Rating Curve= 0 ,0
Exp/Cntr(USF)=0,0
Exp/Cntr=0.3,0.1

Type RM Length L Ch R = 1 ,157593  ,514.3,502.3,492.3
XS GIS Cut Line= 2
     2248151.012        462829.62248692.89661488463779.445284462
#Sta/Elev= 30
       0 2271.97    26.9 2270.57    73.9 2276.89   117.8 2286.58   155.7 2293.29
   192.9 2297.14   211.7  2296.3   220.6 2292.24   229.8 2284.41   252.7 2255.43
   270.3 2236.99   276.8 2228.37   293.8 2212.01   312.7 2191.99   317.2 2188.76
   334.8  2186.4   358.7 2174.37   364.1 2172.17   372.5 2171.34   515.3 2171.38
   528.4 2174.01   538.3 2177.77   561.3 2183.27   570.6 2184.19   616.3  2181.6
   651.5 2184.99   736.9 2184.73   879.1 2193.84  1011.4 2198.14  1093.5 2205.46
#Mann= 6 ,-1,0
       0      .1       0     210     .12       0     260    .025       0
   358.7    .035       0   528.4     .05       0     550      .1       0
#XS Ineff= 2 , 0
                          774.19         2212.85
Permanent Ineff=
       F       F
Bank Sta=358.7,528.4
XS Rating Curve= 0 ,0
Exp/Cntr=0.3,0.1

Type RM Length L Ch R = 1 ,157091  ,474.7,494.8,515.4
XS GIS Cut Line= 2
     2247694.808      463135.6342248336.06264566464027.509606345
#Sta/Elev= 30
       0 2245.35    70.9 2245.88     154 2242.47   189.1 2240.49   233.5 2234.17
   265.8 2227.73   285.8 2220.43     303 2211.73   331.2 2188.15     346 2186.38
   372.4 2174.17   386.1  2170.1     518 2170.02   532.3 2170.73   540.9 2174.07
   568.5 2181.55   691.6 2183.97   716.3 2191.67     731 2189.77   810.9 2189.81
   831.4 2193.21     869 2193.43   903.5 2204.42   918.2 2203.84   947.8 2198.65
   992.1 2199.55  1041.4 2203.82  1070.2 2212.14  1090.7 2212.06  1098.5 2214.59
#Mann= 8 ,-1,0
       0     .05       0     210    .025       0     330      .1       0
   372.4    .035       0   540.9    .025       0     570      .1       0
     690    .025       0     810      .1       0
Bank Sta=372.4,540.9
XS Rating Curve= 0 ,0
Exp/Cntr=0.3,0.1

Type RM Length L Ch R = 1 ,156596  ,463.6,505.1,558.8
XS GIS Cut Line= 3
2247464.97553434463407.0293727652247464.32956565463604.610556478
     2247721.692      464161.868
#Sta/Elev= 30
       0 2236.99    70.2    2233   102.2 2230.13   110.2 2228.55   114.2 2227.43
   122.2 2223.19   126.2 2219.46   134.5 2206.56   142.2 2199.81   149.8 2194.92
   170.2 2188.36   186.2 2187.58     207 2185.03   220.2 2181.32   233.5 2180.62
   251.1 2174.34   268.7 2171.84   281.9 2169.81   440.5 2169.84   449.3 2171.71
   460.1 2177.79   478.2 2179.84     489 2182.96   559.7 2182.72   636.1 2184.73
   678.5 2187.15   718.1 2191.48   757.8 2198.32     793 2209.59   811.4 2217.31
#Mann= 4 ,-1,0
       0    .025       0   268.7    .035       0   449.3    .025       0
  497.58      .1       0
Bank Sta=268.7,449.3
XS Rating Curve= 0 ,0
Exp/Cntr=0.3,0.1

Type RM Length L Ch R = 1 ,156091  ,431.4,482.8,543.6
XS GIS Cut Line= 3
 2247243.2154599 463366.869416042247049.30888186 463701.00245723
     2247064.211      464356.958
#Sta/Elev= 30
       0 2231.87     7.3 2231.04    27.3 2224.09    82.9 2194.63   106.3 2187.05
     146 2184.22     183  2186.3   196.9 2182.32   348.7 2184.39   444.1 2182.93
   462.5 2180.53   486.5 2173.23   510.6 2171.03   530.5 2169.53   694.7  2169.6
     707 2171.23   734.6 2185.46   810.6 2184.46   834.6 2188.99   854.6 2201.86
   870.6 2209.78   886.6  2215.5   906.6 2220.19   922.6 2228.76   950.6 2238.74
   981.3 2258.97   998.7 2265.89  1014.7 2275.92  1030.7 2286.98  1042.4 2298.44
#Mann= 5 ,-1,0
       0      .1       0     100     .05       0     380    .025       0
   510.6    .035       0     707      .1       0
Bank Sta=510.6,707
XS Rating Curve= 0 ,0
Exp/Cntr=0.3,0.1

Type RM Length L Ch R = 1 ,155608  ,472.4,512.9,550.4
XS GIS Cut Line= 2
 2247003.7200127463038.3218193832246371.11118638464204.882869591
#Sta/Elev= 30
       0 2225.75    21.5 2222.64    75.5  2199.3    96.2 2192.27     108 2190.01
   184.7 2187.86   200.4 2186.09   259.2 2185.59   279.1 2182.68   317.2 2180.79
   421.9 2180.81   490.1 2182.69   565.3 2180.52   644.9 2182.91   726.7 2182.58
   745.3 2181.64   758.6 2175.71   795.4 2171.86     813 2169.29   922.4 2169.29
   945.9 2171.86   954.3 2173.26   969.5 2180.14  1004.3 2200.01  1027.1 2207.69
  1077.1 2230.25  1163.6 2273.88  1184.9 2289.03  1240.9 2335.04    1327  2399.4
#Mann= 6 ,-1,0
       0      .1       0      80     .05       0     750    .025       0
   795.4    .035       0   945.9    .025       0     980      .1       0
Bank Sta=795.4,945.9
XS Rating Curve= 0 ,0
Exp/Cntr=0.3,0.1

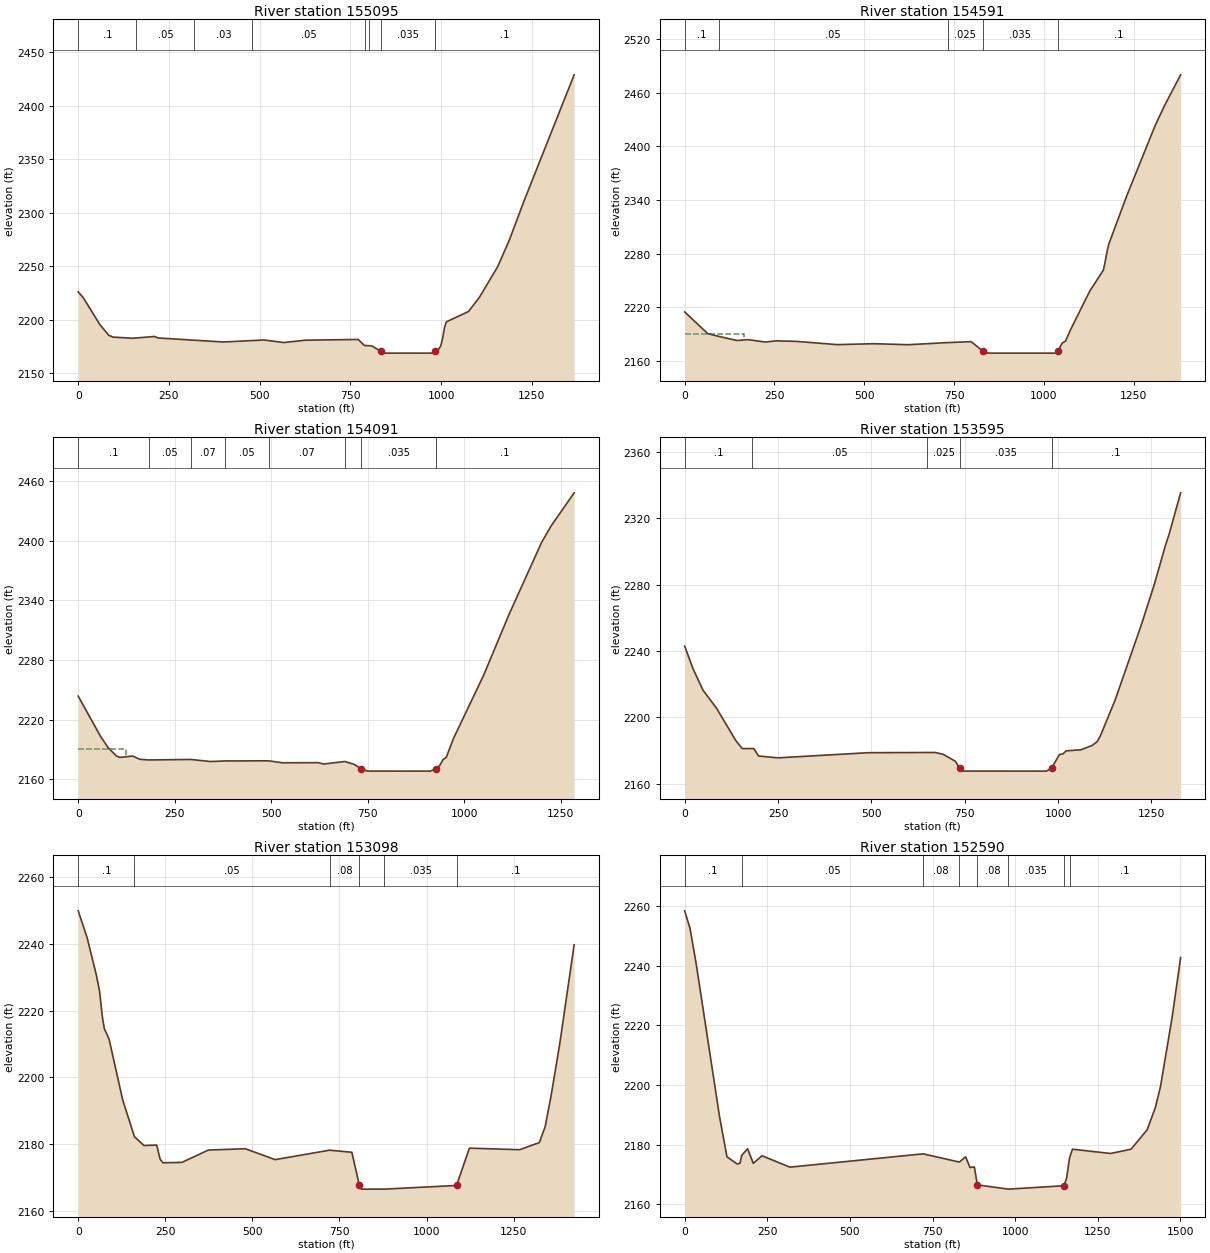
Type RM Length L Ch R = 1 ,155095  ,477.2,504.1,534.4
XS GIS Cut Line= 2
2246923.04562782 462909.24450894     2245846.799       463750.91
#Sta/Elev= 30
       0 2226.18    13.8 2220.84    59.5 2195.75    84.3 2185.64      96 2183.96
   150.2 2182.88     210 2184.53   220.7 2183.12   399.7  2179.4   512.1 2181.27
   566.2 2178.86     626 2181.08   771.4 2181.75   788.5 2176.11   808.4 2175.82
   834.1 2170.67   846.6    2169   973.7 2169.01   983.7 2170.75   993.4 2172.83
   998.9 2175.79    1004 2183.02  1009.1 2192.81  1014.2 2198.17  1075.1 2207.85
  1104.8 2220.82  1155.7 2249.77  1187.4 2274.21  1227.4 2310.35  1366.3 2428.81
#Mann= 8 ,-1,0
       0      .1       0     160     .05       0     320     .03       0
     480     .05       0     790    .025       0     800      .1       0
   834.1    .035       0   983.7      .1       0
Bank Sta=834.1,983.7
XS Rating Curve= 0 ,0
Exp/Cntr=0.3,0.1

Type RM Length L Ch R = 1 ,154591  ,486.4,500.3,516.2
XS GIS Cut Line= 2
2246777.54544779462673.762645698     2245515.502      463234.123
#Sta/Elev= 30
       0  2214.8    64.2  2190.5    94.6 2187.48   145.9 2182.81   176.6 2183.81
   224.7 2181.12   255.3 2182.46   312.2 2181.82   424.9 2178.21   526.7 2179.26
   621.9 2178.12   732.4  2180.5   797.7 2181.55   830.4 2171.01   846.2 2168.72
    1030 2168.72  1034.4 2168.91  1038.7 2171.18  1051.9 2180.17  1060.6 2182.15
  1073.5 2194.16  1128.1 2238.15  1165.7 2261.47    1170 2269.08  1176.7 2283.69
  1181.4 2291.12  1231.1 2344.77  1310.5 2423.66  1337.2 2446.29  1380.9 2479.87
#Mann= 5 ,-1,0
       0      .1       0    94.6     .05       0   732.4    .025       0
   830.4    .035       0  1038.7      .1       0
#XS Ineff= 2 , 0
       0   164.3    2190               0
Permanent Ineff=
       F       F
Bank Sta=830.4,1038.7
XS Rating Curve= 0 ,0
Exp/Cntr=0.3,0.1

Type RM Length L Ch R = 1 ,154091  ,514.5,496.3,481.2
XS GIS Cut Line= 2
2246571.27652222462329.738229658     2245343.706      462706.912
#Sta/Elev= 30
       0  2243.7    57.6 2203.31    78.6 2191.25    99.5 2183.28   107.9 2181.97
   141.3 2183.37   158.9 2180.11   183.2 2179.41     292 2179.91   342.2 2177.82
     380 2178.41   492.8 2178.53   529.2 2176.55   622.6 2176.69   635.1 2175.27
   690.3 2177.86   714.6 2174.97   731.4 2170.79   748.1 2168.19   911.6 2168.16
   927.1 2170.55   936.4 2173.97   944.8  2179.8   953.1 2182.07   971.9 2201.19
  1049.4 2264.31  1116.3 2326.55    1200  2398.5  1225.1 2415.36  1284.2 2448.37
#Mann= 8 ,-1,0
       0      .1       0   183.2     .05       0     292     .07       0
     380     .05       0   492.8     .07       0   690.3    .025       0
   731.4    .035       0   927.1      .1       0
#XS Ineff= 2 , 0
       0   124.6    2190               0
Permanent Ineff=
       F       F
Bank Sta=731.4,927.1
XS Rating Curve= 0 ,0
Exp/Cntr=0.3,0.1

Type RM Length L Ch R = 1 ,153595  ,511,496.8,486
XS GIS Cut Line= 2
2246405.00505021461752.319173685       2245191.9      462293.622
#Sta/Elev= 30
       0 2242.87    22.5 2229.17    49.1  2216.3    86.1 2205.17   136.7 2185.98
   154.2 2181.05   184.9  2181.1     198 2176.61   249.6 2175.48   491.5 2178.58
   671.1 2178.72     693 2177.57   725.1  2173.4   736.8 2169.13   745.5 2167.49
   968.9 2167.47   982.6  2169.3    1004 2177.55  1012.9  2177.8    1022 2179.72
  1060.9 2180.32  1091.6 2182.99  1104.7 2185.24  1113.5 2188.76  1152.9  2210.3
    1223 2255.59  1258.2 2280.27    1288 2303.86  1297.9 2310.64  1328.4 2335.37
#Mann= 5 ,-1,0
       0      .1       0     180     .05       0     650    .025       0
   736.8    .035       0   982.6      .1       0
Bank Sta=736.8,982.6
XS Rating Curve= 0 ,0
Exp/Cntr=0.3,0.1

Type RM Length L Ch R = 1 ,153098  ,496.8,507.3,512.4
XS GIS Cut Line= 2
2246245.97497577461196.031800919     2244995.722      461877.014
#Sta/Elev= 30
       0 2249.86    25.8 2241.74    52.2 2230.57    61.3 2225.78    69.3 2218.13
    74.9 2214.59    88.6 2211.43   127.8  2193.2   161.5 2182.22   188.8 2179.58
   225.2 2179.73   235.1 2175.51   243.5 2174.41   298.1 2174.55   373.7 2178.23
   479.9 2178.62   565.4 2175.36   721.6 2178.19   785.5 2177.56   807.2 2167.67
   812.8 2166.53   879.1 2166.53  1086.1 2167.63    1123  2178.8  1267.2 2178.33
  1323.7 2180.46  1340.4 2185.18  1357.1 2194.25  1382.2 2209.93  1423.7  2239.7
#Mann= 6 ,-1,0
       0      .1       0   161.5     .05       0   721.6     .08       0
   807.2     .07       0   879.1    .035       0  1086.1      .1       0
Bank Sta=807.2,1086.1
XS Rating Curve= 0 ,0
Exp/Cntr=0.3,0.1

Type RM Length L Ch R = 1 ,152590  ,431.6,498.4,544
XS GIS Cut Line= 2
2246067.65000693460783.043484128     2244712.765      461427.744
#Sta/Elev= 30
       0 2258.36    16.2 2252.47    34.9 2240.54   105.7  2189.2   127.9 2175.89
   158.9 2173.47   167.7 2173.78   172.5 2176.35   190.3  2178.6   207.6 2173.71
   234.2 2176.23   318.4 2172.42   721.5 2176.88     831 2174.12   849.9 2175.88
   863.2 2172.33   876.5 2172.48   885.4 2166.48   979.5 2165.05  1147.8 2166.19
  1155.6 2168.78  1164.4 2175.54  1173.3 2178.44  1288.5    2177  1350.5 2178.43
  1399.2 2184.93  1423.9 2192.34  1439.5 2199.37    1475 2222.78  1500.5 2242.69
#Mann= 8 ,-1,0
       0      .1       0   172.5     .05       0   721.5     .08       0
     831    .025       0   885.4     .08       0   979.5    .035       0
  1147.8    .025       0  1164.4      .1       0
Bank Sta=885.4,1147.8
XS Rating Curve= 0 ,0
Exp/Cntr=0.3,0.1

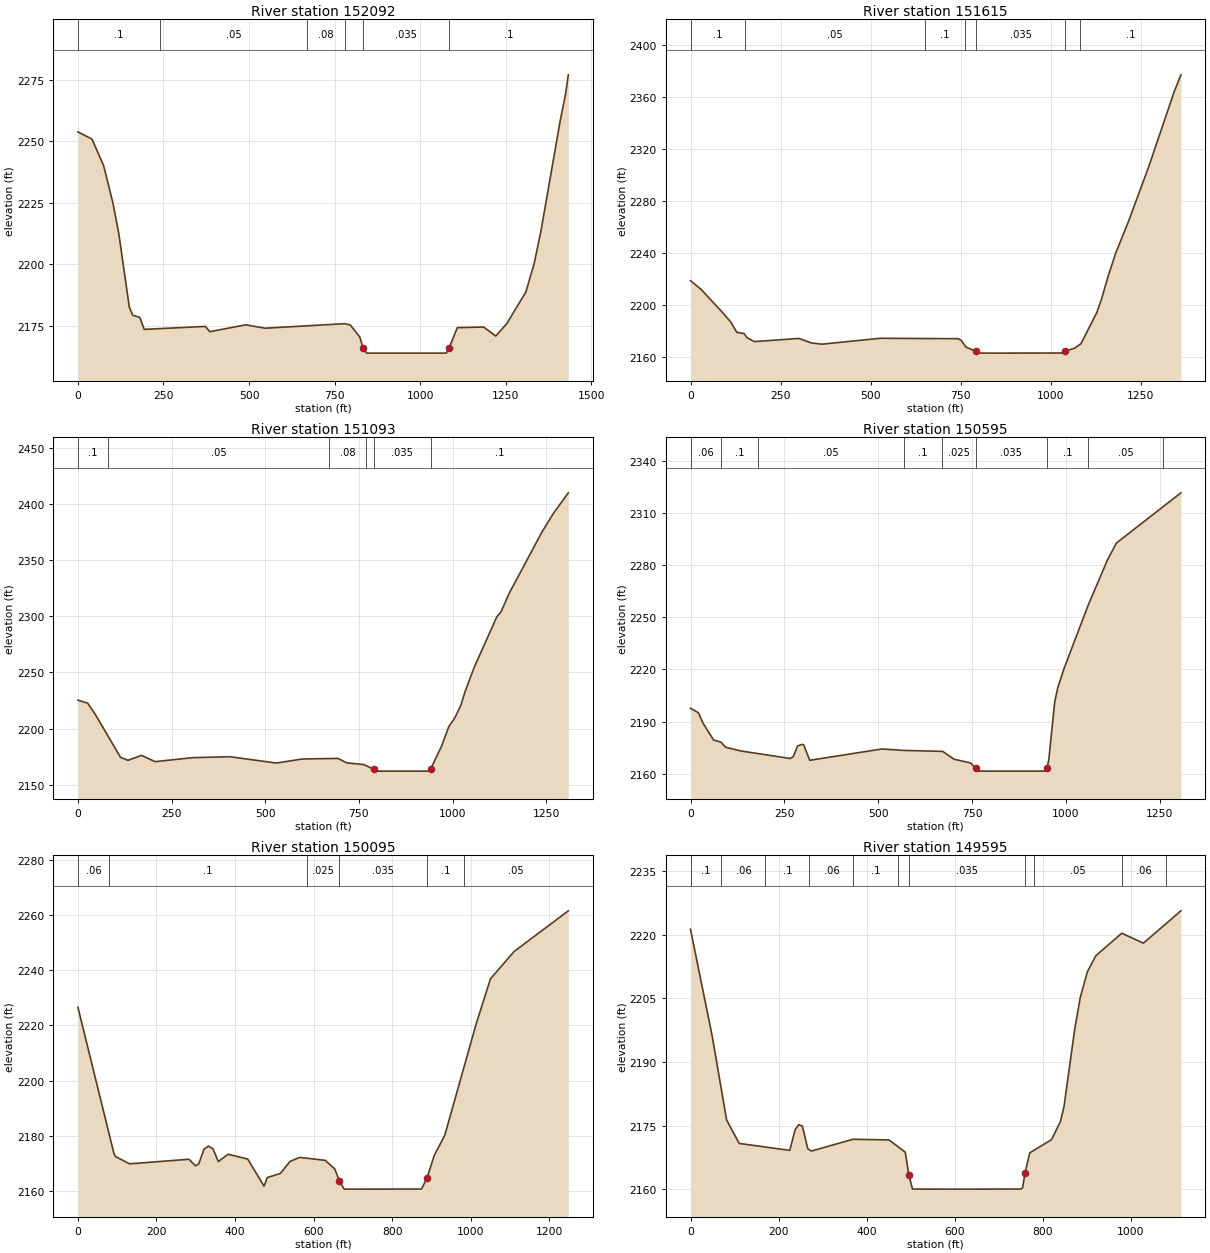
Type RM Length L Ch R = 1 ,152092  ,529.5,476.7,428.4
XS GIS Cut Line= 3
2245937.90190621460452.2808545612245295.99366633460730.782212933
      2244564.56      460781.526
#Sta/Elev= 30
       0 2253.89    41.1 2250.93      75 2240.16   102.2 2224.98   119.6 2212.27
   150.1  2182.5   160.1 2179.21   180.7 2178.29   193.7 2173.43   372.5 2174.63
   385.2 2172.48   490.2 2175.28   546.9 2173.91   779.7 2175.75   795.8 2175.22
   823.8 2170.26     833 2165.85   843.9 2163.75  1076.4 2163.75  1084.7 2165.93
  1108.5 2174.12  1185.5 2174.39  1220.8  2170.7  1252.9 2175.73  1308.8 2188.65
  1333.1 2200.25  1353.1 2213.65  1409.2 2258.48  1425.3 2269.62  1432.9 2277.13
#Mann= 6 ,-1,0
       0      .1       0     240     .05       0     670     .08       0
  779.72    .025       0     833    .035       0  1084.7      .1       0
Bank Sta=833,1084.7
XS Rating Curve= 0 ,0
Exp/Cntr=0.3,0.1

Type RM Length L Ch R = 1 ,151615  ,470.5,522,583.7
XS GIS Cut Line= 3
2245758.50831738460056.8272856312245196.44234519460161.277657404
     2244474.972       460481.55
#Sta/Elev= 30
       0 2218.63    29.8 2211.85    88.1 2194.37   111.4 2186.95   128.5 2178.84
   148.8 2177.93     157 2174.72   177.3 2171.72   300.8 2174.16     336 2170.66
   364.5 2169.74   527.2 2174.28   742.7 2173.96   750.6 2172.88   764.5 2167.53
   792.8 2164.15   799.6 2162.87   847.7 2162.84  1028.9 2162.93  1040.3  2164.5
  1066.5 2166.63    1084 2170.23  1127.8 2194.16  1140.9 2204.51  1158.4 2221.42
  1180.3 2239.99  1215.3 2263.99    1272 2306.54  1342.2 2363.93  1361.1 2377.19
#Mann= 7 ,-1,0
       0      .1       0     150     .05       0  651.69      .1       0
  761.69    .025       0   792.8    .035       0  1040.3    .025       0
 1081.69      .1       0
Bank Sta=792.8,1040.3
XS Rating Curve= 0 ,0
Exp/Cntr=0.3,0.1

Type RM Length L Ch R = 1 ,151093  ,504.4,498.1,492.3
XS GIS Cut Line= 2
  2245698.058367      459782.503     2244389.104      459781.519
#Sta/Elev= 30
       0 2225.32    25.9 2222.61    45.9 2212.83   113.9 2174.23   133.9 2171.69
   169.9 2176.05   205.9 2170.47   305.9 2174.01   404.9 2174.86   529.9 2169.21
   598.8 2172.82   693.9 2173.36   717.9 2169.34   762.6  2167.9   789.2 2163.83
   801.9    2162   933.9    2162   941.9 2164.12   970.5 2184.17   989.9 2201.68
  1005.9 2209.43  1021.9 2220.46  1033.9 2233.44  1057.9 2254.73  1117.9 2299.55
  1129.4 2304.09  1150.3 2320.14  1237.9 2374.94  1269.5 2392.13    1309  2410.3
#Mann= 6 ,-1,0
       0      .1       0      80     .05       0     670     .08       0
     770    .025       0   789.2    .035       0   941.9      .1       0
Bank Sta=789.2,941.9
XS Rating Curve= 0 ,0
Exp/Cntr=0.3,0.1

Type RM Length L Ch R = 1 ,150595  ,501.2,499.9,500
XS GIS Cut Line= 2
 2245693.4958142459241.901683208     2244388.495      459306.149
#Sta/Elev= 30
       0 2197.62    21.3 2195.02    33.4 2189.04    61.4 2179.35    81.4 2178.07
    93.4 2175.19   133.5 2173.03   265.6 2168.66   273.7 2169.75   285.7 2175.97
   297.7 2176.81   301.7 2176.45   317.7 2167.62   509.9 2174.16     570 2173.32
   671.9 2172.76   702.2 2168.24   746.2  2166.1   760.1 2163.05   766.2 2161.38
   942.5 2161.38   949.9  2163.2   954.5 2167.69   970.5 2201.41   978.5 2209.48
   994.5 2220.11  1059.4 2256.98  1111.3 2283.36  1134.7  2292.9  1306.6 2321.89
#Mann= 9 ,-1,0
       0     .06       0      80      .1       0     180     .05       0
     570      .1       0     670    .025       0   760.1    .035       0
   949.9      .1       0    1060     .05       0    1260      .1       0
Bank Sta=760.1,949.9
XS Rating Curve= 0 ,0
Exp/Cntr=0.3,0.1

Type RM Length L Ch R = 1 ,150095  ,528.8,500.3,480.3
XS GIS Cut Line= 3
2245588.53969857458617.9539344652245026.87800909458774.200122393
     2244362.021       458806.85
#Sta/Elev= 30
       0 2226.58    91.7 2173.65    95.9 2172.54   131.4 2169.92   282.7 2171.57
   299.3 2169.17   307.6 2169.88   321.2  2175.3   332.5 2176.34     344 2175.34
   357.4 2170.74   382.4 2173.39   432.2 2171.65   473.9 2161.84     482 2164.96
   515.2 2166.42   540.1  2170.8     565 2172.25   629.7 2171.18   653.8 2168.07
   665.8 2163.77   677.8 2160.76   874.7 2160.79   888.4 2164.61     907 2172.86
   934.1 2180.29  1014.2 2220.68  1050.3 2236.86  1110.3 2246.75  1248.6  2261.5
#Mann= 6 ,-1,0
       0     .06       0      80      .1       0  582.99    .025       0
   665.8    .035       0   888.4      .1       0  982.99     .05       0
Bank Sta=665.8,888.4
XS Rating Curve= 0 ,0
Exp/Cntr=0.3,0.1

Type RM Length L Ch R = 1 ,149595  ,522.1,500,485.2
XS GIS Cut Line= 2
2245388.19258716458147.261228046     2244301.196      458388.227
#Sta/Elev= 30
       0 2221.32    49.2 2196.16      82 2176.33   110.6 2170.81   225.4 2169.17
   237.7 2174.09   245.8 2175.22     254 2174.89   266.3 2169.55   274.5 2169.01
   368.8 2171.79   450.7 2171.63   487.6 2168.75   495.8 2163.41     504 2160.04
   632.1 2160.03   749.8 2160.06   753.9 2160.29   759.6 2163.89   770.3 2168.59
   819.9 2171.71   839.9 2175.98   848.1 2179.53   872.7 2198.01     885 2205.26
   901.4 2211.36   920.5 2215.09   979.2 2220.38  1028.4 2218.04  1113.4 2225.66
#Mann= 11 ,-1,0
       0      .1       0      70     .06       0     170      .1       0
     270     .06       0     370      .1       0     470    .025       0
   495.8    .035       0   759.6    .025       0     780     .05       0
     980     .06       0    1080     .05       0
Bank Sta=495.8,759.6
XS Rating Curve= 0 ,0
Exp/Cntr=0.3,0.1

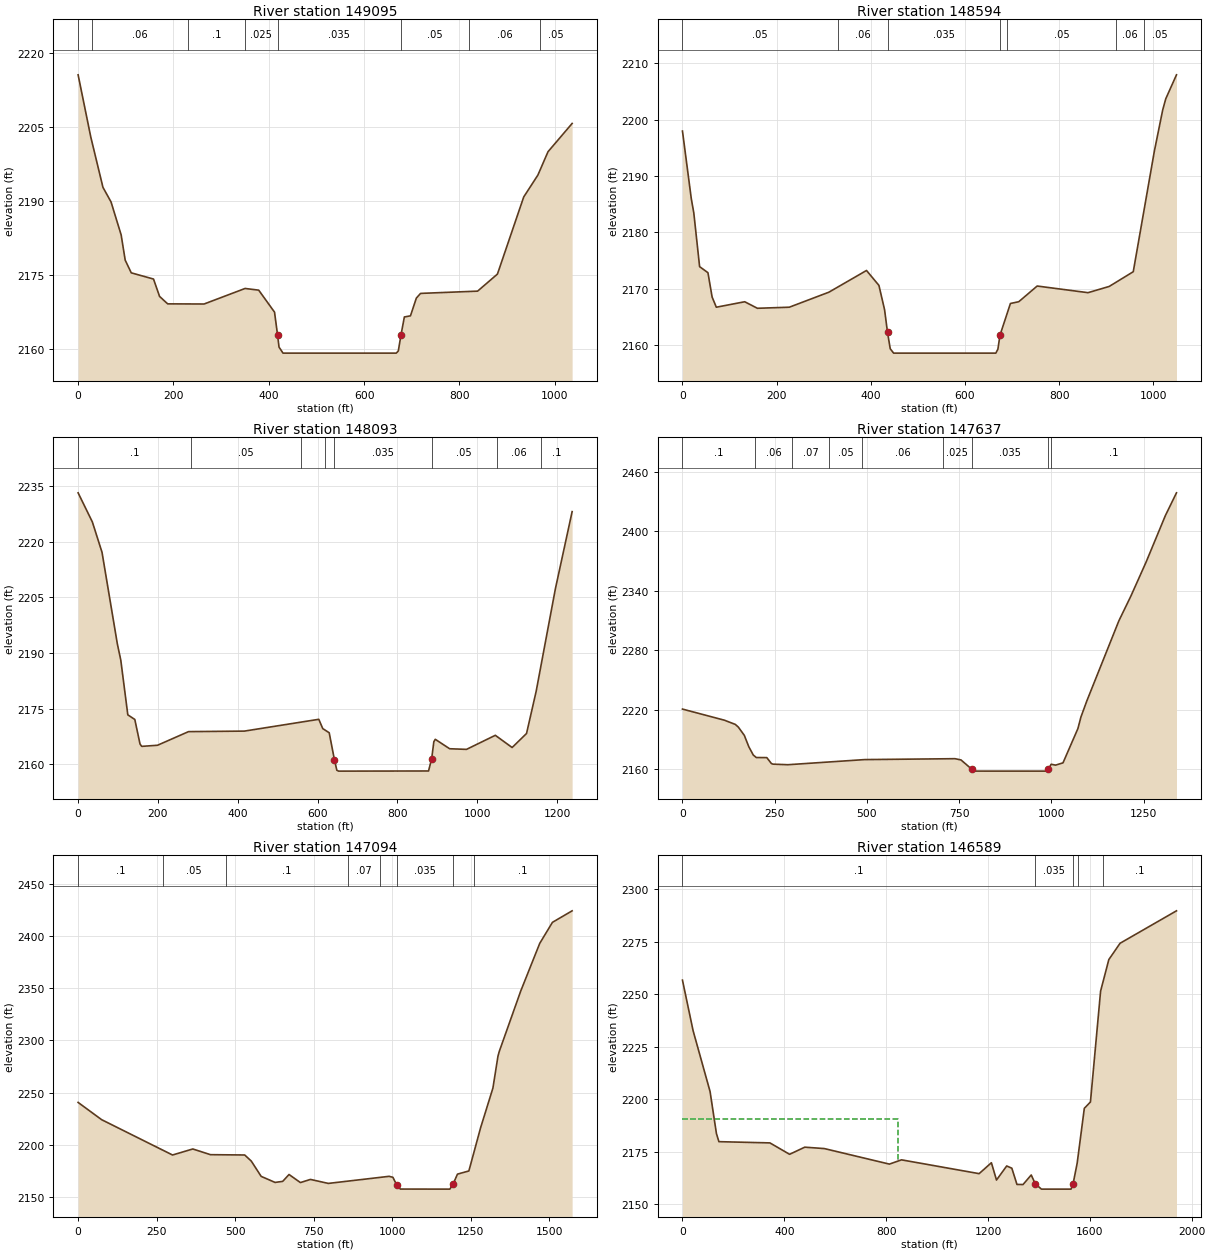
Type RM Length L Ch R = 1 ,149095  ,519.5,500.7,488.9
XS GIS Cut Line= 2
2245153.26517956457616.011296198     2244176.516      457962.714
#Sta/Elev= 30
       0 2215.59    26.6 2202.97    52.1 2192.78    69.1 2189.81    90.3 2183.13
    98.8 2178.01   111.5 2175.44   158.2 2174.18   170.9 2170.66   187.9 2169.15
   264.3 2169.12   350.3 2172.27   378.9 2171.93   412.1 2167.47   418.4 2162.89
   421.5 2160.39   429.9 2159.16   667.5 2159.16   671.8  2159.6   677.6 2162.93
   684.5 2166.49   697.3 2166.72   709.7 2170.33   718.5 2171.27   838.2 2171.73
   879.8 2175.19   934.9 2190.82   964.7 2195.27   985.9    2200  1036.5 2205.73
#Mann= 8 ,-1,0
       0      .1       0      30     .06       0     230      .1       0
     350    .025       0   418.4    .035       0   677.6     .05       0
     820     .06       0     970     .05       0
Bank Sta=418.4,677.6
XS Rating Curve= 0 ,0
Exp/Cntr=0.3,0.1

Type RM Length L Ch R = 1 ,148594  ,500.4,501.3,502.3
XS GIS Cut Line= 2
2244929.06745217457101.913478373     2243981.699      457553.162
#Sta/Elev= 30
       0 2197.98    18.7    2186    24.1 2183.44    36.4 2173.91    54.1 2172.84
      63 2168.51    71.9 2166.71   132.2 2167.68   159.2 2166.52   226.9 2166.71
   311.1 2169.38   390.9 2173.23   417.3 2170.58   429.3 2166.26   435.5 2162.25
   441.3 2159.34   448.5 2158.56   665.6 2158.56     670 2159.27   674.4 2161.74
   696.6 2167.37   714.4 2167.69   753.4 2170.47   861.4 2169.29   906.5  2170.4
   957.5 2173.01  1002.3 2194.41    1020 2201.71  1026.5  2203.7  1049.3 2207.96
#Mann= 7 ,-1,0
       0     .05       0     330     .06       0   435.5    .035       0
   674.4    .025       0     690     .05       0     920     .06       0
     980     .05       0
Bank Sta=435.5,674.4
XS Rating Curve= 0 ,0
Exp/Cntr=0.3,0.1

Type RM Length L Ch R = 1 ,148093  ,402.9,455.8,508
XS GIS Cut Line= 4
2244899.48424848456616.9477682922244826.28799951456606.441542057
2244557.30076792 456726.71686545      2243770.49      457095.332
#Sta/Elev= 30
       0 2233.16    35.7 2225.31    59.9 2217.13    98.2 2192.51   106.9 2188.09
   124.5 2173.35     142 2172.11   155.1 2165.49   159.4 2164.86   198.9 2165.16
   276.6 2168.83   416.4 2168.97   602.9 2172.15   612.8 2169.65     629 2168.52
     642 2161.28   648.1 2158.43   652.5 2158.19   877.8 2158.23   885.7 2161.55
   891.1 2166.12   894.7 2166.76   930.7 2164.22   972.9 2164.05  1045.1 2167.84
  1087.2 2164.55  1123.3 2168.33  1147.4 2179.69  1195.5 2207.28  1237.5  2228.1
#Mann= 8 ,-1,0
       0      .1       0  283.95     .05       0   558.6     .06       0
   618.6    .025       0     642    .035       0   885.7     .05       0
  1048.6     .06       0  1158.6      .1       0
Bank Sta=642,885.7
XS Rating Curve= 0 ,0
Exp/Cntr=0.3,0.1

Type RM Length L Ch R = 1 ,147637  ,525.3,543.4,568.8
XS GIS Cut Line= 5
2244917.37490187 456389.87955835  2244800.409603456341.568542504
2244171.71679371 456466.393749192243883.76573514456473.745961117
     2243608.129      456408.958
#Sta/Elev= 30
       0 2220.54   113.8 2209.29   143.1 2205.08   151.3 2202.38   167.6 2194.02
   179.8 2182.49     192 2174.07   200.2 2171.61   228.5 2171.53     241 2165.56
   245.1 2164.93   285.8 2164.35   493.9 2169.53   738.5 2170.44   754.8 2169.17
783.64242159.927   795.1 2157.91   987.1 2157.88991.53082159.821   999.1  2164.8
  1011.1 2163.94  1031.2 2166.24  1071.6 2200.87  1079.8 2212.56  1095.6 2228.62
  1182.5  2309.6  1215.4 2334.86  1256.5 2369.11  1308.5 2415.87  1338.7 2438.93
#Mann= 9 ,-1,0
       0      .1       0  196.55     .06       0  296.55     .07       0
  396.55     .05       0  486.55     .06       0  706.55    .025       0
783.6424    .035       0991.5308     .06       0  997.51      .1       0
Bank Sta=783.6424,991.5308
XS Rating Curve= 0 ,0
Exp/Cntr=0.3,0.1

Type RM Length L Ch R = 1 ,147094  ,528.6,504.4,488.7
XS GIS Cut Line= 2
2245290.42444705456084.726253969     2243729.956       455882.59
#Sta/Elev= 30
       0  2240.6    74.9 2224.06   300.7 2190.19   365.3 2195.97   421.7  2190.5
   530.6 2190.21   551.5 2184.39   583.1 2169.68   627.4  2163.9   651.6  2164.9
   671.8 2171.49   708.1 2163.75   739.9 2166.78   796.9 2162.95   990.5 2169.74
  1002.6 2168.82  1014.7 2161.49  1026.4 2157.53  1184.1 2157.47  1194.3 2162.22
  1208.3 2171.86  1244.6 2174.89    1282 2216.36  1321.2 2254.37  1337.3 2284.98
  1341.4 2289.47  1409.9 2347.52  1470.4 2393.18  1510.8 2413.29  1573.5 2424.33
#Mann= 8 ,-1,0
       0      .1       0     270     .05       0     470      .1       0
     860     .07       0     960    .025       0  1014.7    .035       0
  1194.3     .06       0    1260      .1       0
Bank Sta=1014.7,1194.3
XS Rating Curve= 0 ,0
Exp/Cntr=0.3,0.1

Type RM Length L Ch R = 1 ,146589  ,533.3,495.2,469.8
XS GIS Cut Line= 3
2245303.26071733454637.7945144952244745.71692706455398.312841575
     2243751.172      455471.109
#Sta/Elev= 30
       0 2256.76    41.8 2232.64   108.4 2203.66   133.4 2183.61   143.1 2179.75
   343.5 2179.16   420.8 2173.72   480.3 2177.12     557 2176.46   812.6 2169.05
   860.3 2171.08  1165.1  2164.5  1213.3 2169.71  1233.3 2161.45  1273.4 2168.16
  1293.5  2167.1  1313.7 2159.36  1337.6 2159.31  1369.7 2163.87  1385.7 2159.64
  1409.8 2157.12  1526.1 2157.12  1534.1 2159.65  1550.2  2169.5  1578.2 2195.63
  1602.3 2198.68  1642.2 2251.54  1674.5 2266.56  1718.6 2274.34  1940.2 2289.81
#Mann= 5 ,-1,0
       0      .1       0  1385.7    .035       0  1534.1      .1       0
    1553     .06       0    1653      .1       0
#XS Ineff= 2 , 0
          845.07 2190.45
Permanent Ineff=
       F       F
Bank Sta=1385.7,1534.1
XS Rating Curve= 0 ,0
Exp/Cntr=0.3,0.1