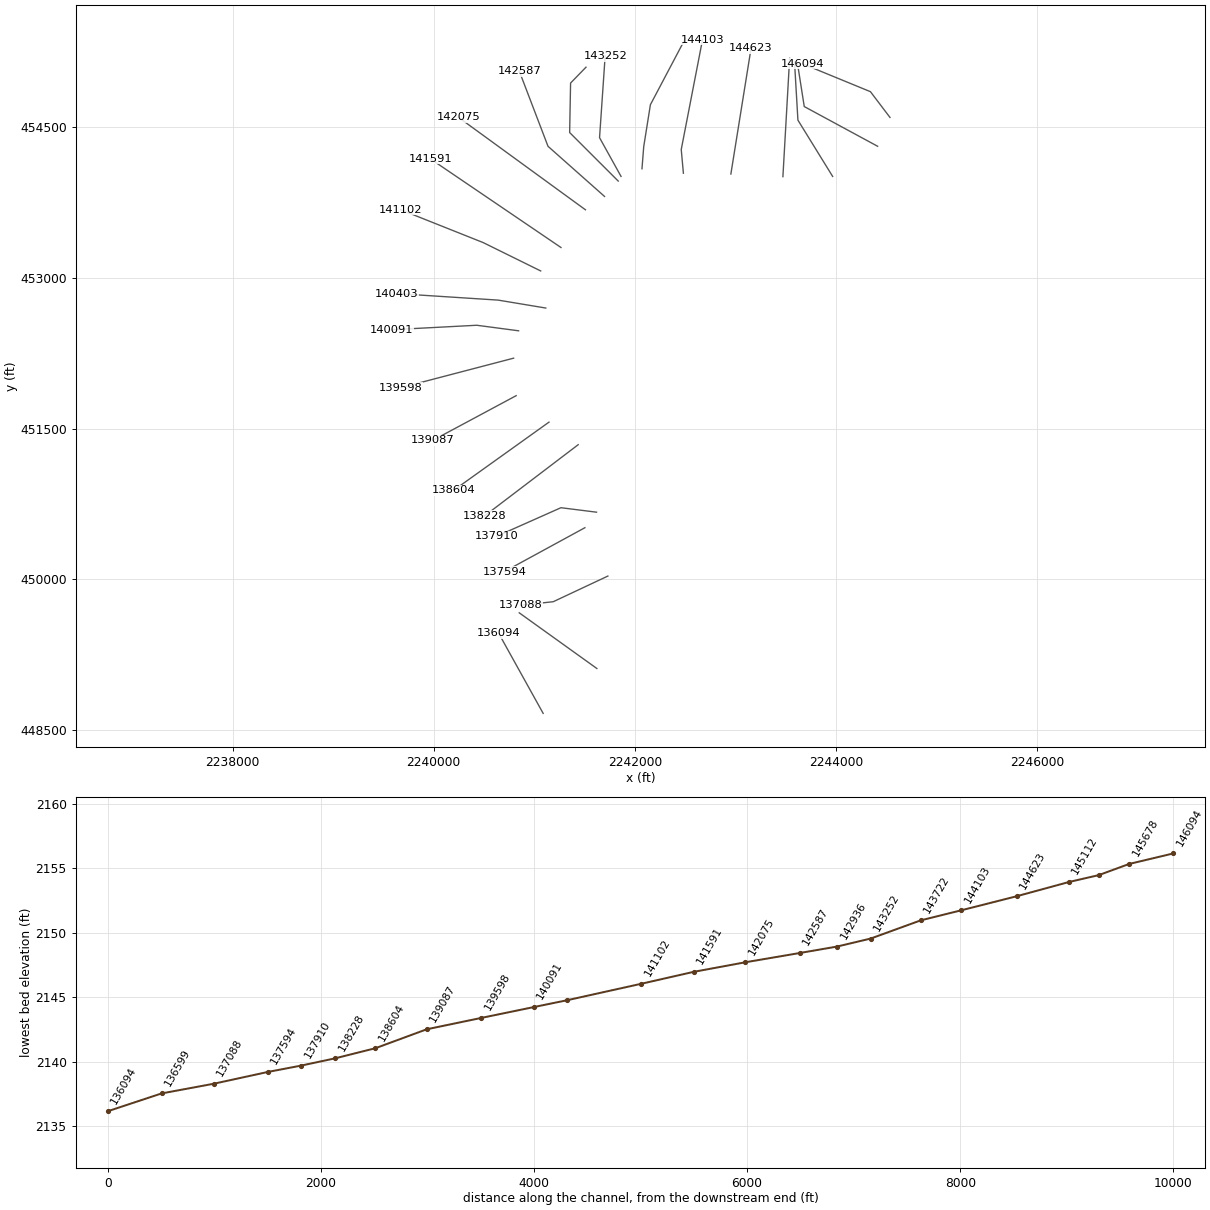
HEC-RAS study GRNBRRRV.prj: GRNBRRRV

--- GRNBRRRV.g01 (geometry) --- (continued)

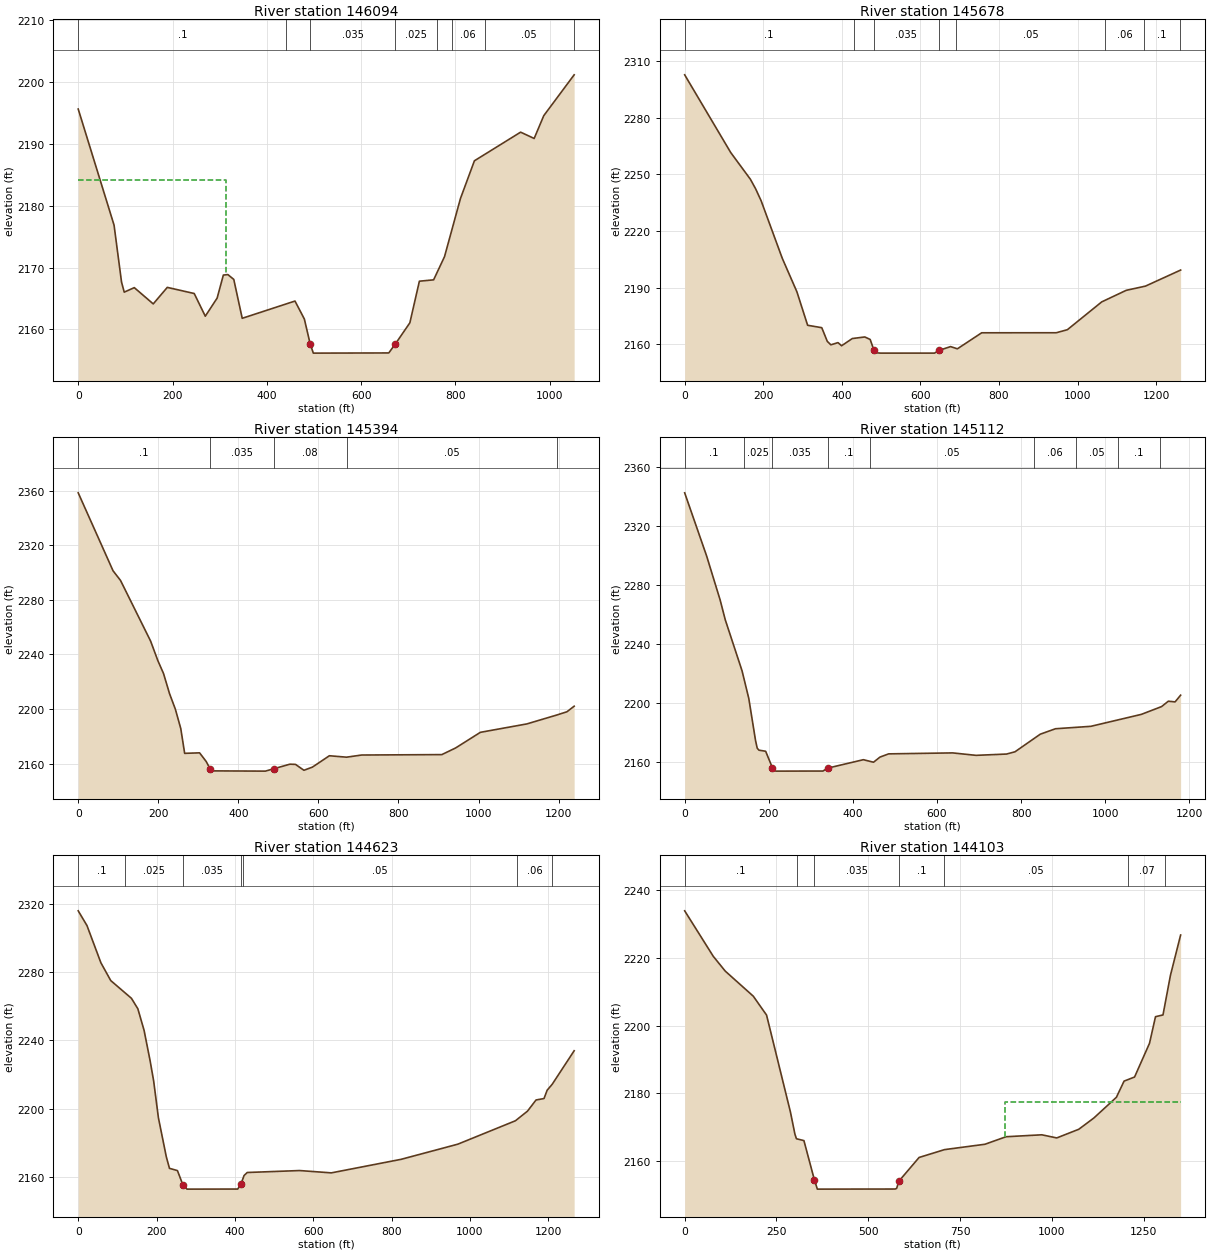
Type RM Length L Ch R = 1 ,146094  ,428,416.7,405
XS GIS Cut Line= 3
2244538.10722674454598.4109580552244343.85656739454854.732173388
     2243668.555      455132.343
#Sta/Elev= 30
       0 2195.63      76 2176.86    91.9 2167.64    97.6 2166.02   118.9 2166.75
   159.1 2164.12   188.9 2166.79     246  2165.8   269.5 2162.13   294.6 2165.06
   307.8 2168.78   317.4 2168.86   329.9 2168.08   347.8 2161.79   459.7 2164.58
   479.6 2161.67   491.8 2157.68   498.6 2156.16   658.6 2156.19   672.6 2157.65
   703.3 2161.06   723.5 2167.79   753.7 2168.01   776.8 2171.76   810.6 2181.16
   840.2 2187.26   938.2 2191.89   966.9 2190.87   987.3 2194.56  1051.7 2201.16
#Mann= 8 ,-1,0
       0      .1       0  441.61    .025       0   491.8    .035       0
   672.6    .025       0  761.61      .1       0  791.61     .06       0
  861.61     .05       0 1051.61     .06       0
#XS Ineff= 2 , 0
          312.87 2184.22
Permanent Ineff=
       F       F
Bank Sta=491.8,672.6
XS Rating Curve= 0 ,0
Exp/Cntr=0.3,0.1

Type RM Length L Ch R = 1 ,145678  ,330.8,283.1,226.1
XS GIS Cut Line= 3
2244415.33379936454311.2867353852243685.60704663454706.676529692
2243618.73965494455134.046380892
#Sta/Elev= 30
       0  2302.7   117.3 2261.53   167.4 2247.37   180.8 2242.27   194.7 2235.98
   248.6 2205.47   285.7 2187.82     313 2170.09     349 2168.81     363 2161.59
   372.1 2159.74   390.3 2160.91   399.4 2159.24   426.7 2163.06   458.5  2163.9
   472.2 2162.58   481.7 2156.97   485.8 2155.53   499.4 2155.34     636 2155.35
     647 2156.75   676.9  2158.8   694.2 2157.62   756.1 2166.11   945.9 2166.13
   974.2 2167.74  1061.6 2182.46    1124 2188.59    1173 2190.82  1262.5 2199.32
#Mann= 8 ,-1,0
       0      .1       0     430    .025       0   481.7    .035       0
     647      .1       0     690     .05       0 1069.96     .06       0
 1169.96      .1       0 1259.96     .06       0
Bank Sta=481.7,647
XS Rating Curve= 0 ,0
Exp/Cntr(USF)=0,0
Exp/Cntr=0.3,0.1

Type RM Length L Ch R = 1 ,145394  ,336.2,282.7,224
XS GIS Cut Line= 3
2243967.98977381454011.1029485252243622.62419746454571.416331134
2243588.81218299455151.050864868
#Sta/Elev= 30
       0 2358.44      87 2301.32   105.8 2294.18     181 2249.68     199 2235.41
   213.1 2226.03   228.1 2211.29   242.7 2199.85   256.2 2185.66   265.9 2167.52
   303.2 2167.88   319.8 2161.48   329.9  2155.9   335.7 2154.66   467.6 2154.48
   487.92156.166   528.7 2159.56   542.8 2159.41   563.8  2155.1   585.1 2157.43
   627.4 2165.75   670.2  2164.7     708 2166.28   908.3 2166.59   942.6 2171.44
  1004.6 2182.91  1120.7 2189.08    1196 2195.65  1220.9    2198  1238.8 2202.07
#Mann= 5 ,-1,0
       0      .1       0   329.9    .035       0   487.9     .08       0
   670.2     .05       0    1196      .1       0
Bank Sta=329.9,487.9
XS Rating Curve= 0 ,0
Exp/Cntr(USF)=0,0
Exp/Cntr=0.3,0.1

Type RM Length L Ch R = 1 ,145112  ,496.6,488.7,479.8
XS GIS Cut Line= 2
2243473.37575998454008.9298338562243540.24315166 455186.37738308
#Sta/Elev= 30
       0 2342.41    52.3 2299.56    84.4 2269.77    96.4 2256.53   136.5 2221.82
   152.5 2203.09   168.5 2174.68   172.5  2169.5   176.5 2168.15   192.6 2167.38
   208.82156.069   216.6 2153.94   328.8    2154   340.12155.971   424.9 2161.68
     449 2159.97   464.5 2163.46     485 2165.63   637.3 2166.28   692.9 2164.62
   765.5 2165.51   785.5 2167.04   845.6 2178.96   881.7 2182.64   965.8 2184.28
    1086 2192.38  1134.1 2197.66  1150.1 2201.29  1166.1 2200.82  1179.3 2205.38
#Mann= 9 ,-1,0
       0      .1       0     140    .025       0   208.8    .035       0
   340.1      .1       0     440     .05       0     830     .06       0
     930     .05       0    1030      .1       0    1130     .06       0
Bank Sta=208.8,340.1
XS Rating Curve= 0 ,0
Exp/Cntr(USF)=0,0
Exp/Cntr=0.3,0.1

Type RM Length L Ch R = 1 ,144623  ,523,520.3,523
XS GIS Cut Line= 2
 2242955.8802939 454035.095334952243156.48246895455285.224831656
#Sta/Elev= 30
       0    2316    22.4 2307.35    57.9 2285.55    83.1  2275.1   135.8 2264.73
   152.2 2258.61   168.2  2245.9   183.6 2228.05   192.5 2216.41   204.8 2194.62
   224.9 2171.81     233 2165.02   253.3 2163.71   267.4 2155.26   277.6 2152.84
   407.2 2152.88   415.3  2155.7   423.4  2160.8   431.5 2162.59   565.2 2163.73
   646.2 2162.37   824.5 2170.32   969.1 2179.19  1116.2 2192.92  1147.1 2198.59
  1168.8  2205.1  1189.1 2205.94  1197.2 2210.83    1210 2214.29  1266.1 2233.96
#Mann= 7 ,-1,0
       0      .1       0     120    .025       0   267.4    .035       0
   415.3      .1       0     420     .05       0    1120     .06       0
    1210      .1       0
Bank Sta=267.4,415.3
XS Rating Curve= 0 ,0
Exp/Cntr(USF)=0,0
Exp/Cntr=0.3,0.1

Type RM Length L Ch R = 1 ,144103  ,376.7,380.6,385.3
XS GIS Cut Line= 3
2242483.72238532454043.0862726082242462.38546642454279.223366031
2242673.95733985455372.300662663
#Sta/Elev= 30
       0 2233.82    77.9  2220.4   110.5 2216.04   186.9 2208.64     223 2203.07
     288 2174.49   300.2 2167.96   304.3 2166.61   324.7 2166.06   353.5 2154.38
   361.3 2151.75   573.2 2151.78   577.3 2151.98   583.3 2154.09   638.4 2161.09
   707.6  2163.4   817.6 2164.98   875.2  2167.2   972.5 2167.77  1013.2 2166.85
  1073.2  2169.4  1114.2 2172.72  1175.6 2178.83  1196.5  2183.6  1225.1 2184.81
  1265.8 2194.76  1282.1  2202.6  1302.5 2203.12  1322.8  2214.8  1350.5 2226.68
#Mann= 7 ,-1,0
       0      .1       0   307.1    .025       0   353.5    .035       0
   583.3      .1       0   707.1     .05       0  1207.1     .07       0
  1307.1     .06       0
#XS Ineff= 2 , 0
                          873.13         2177.56
Permanent Ineff=
       F       F
Bank Sta=353.5,583.3
XS Rating Curve= 0 ,0
Exp/Cntr=0.3,0.1

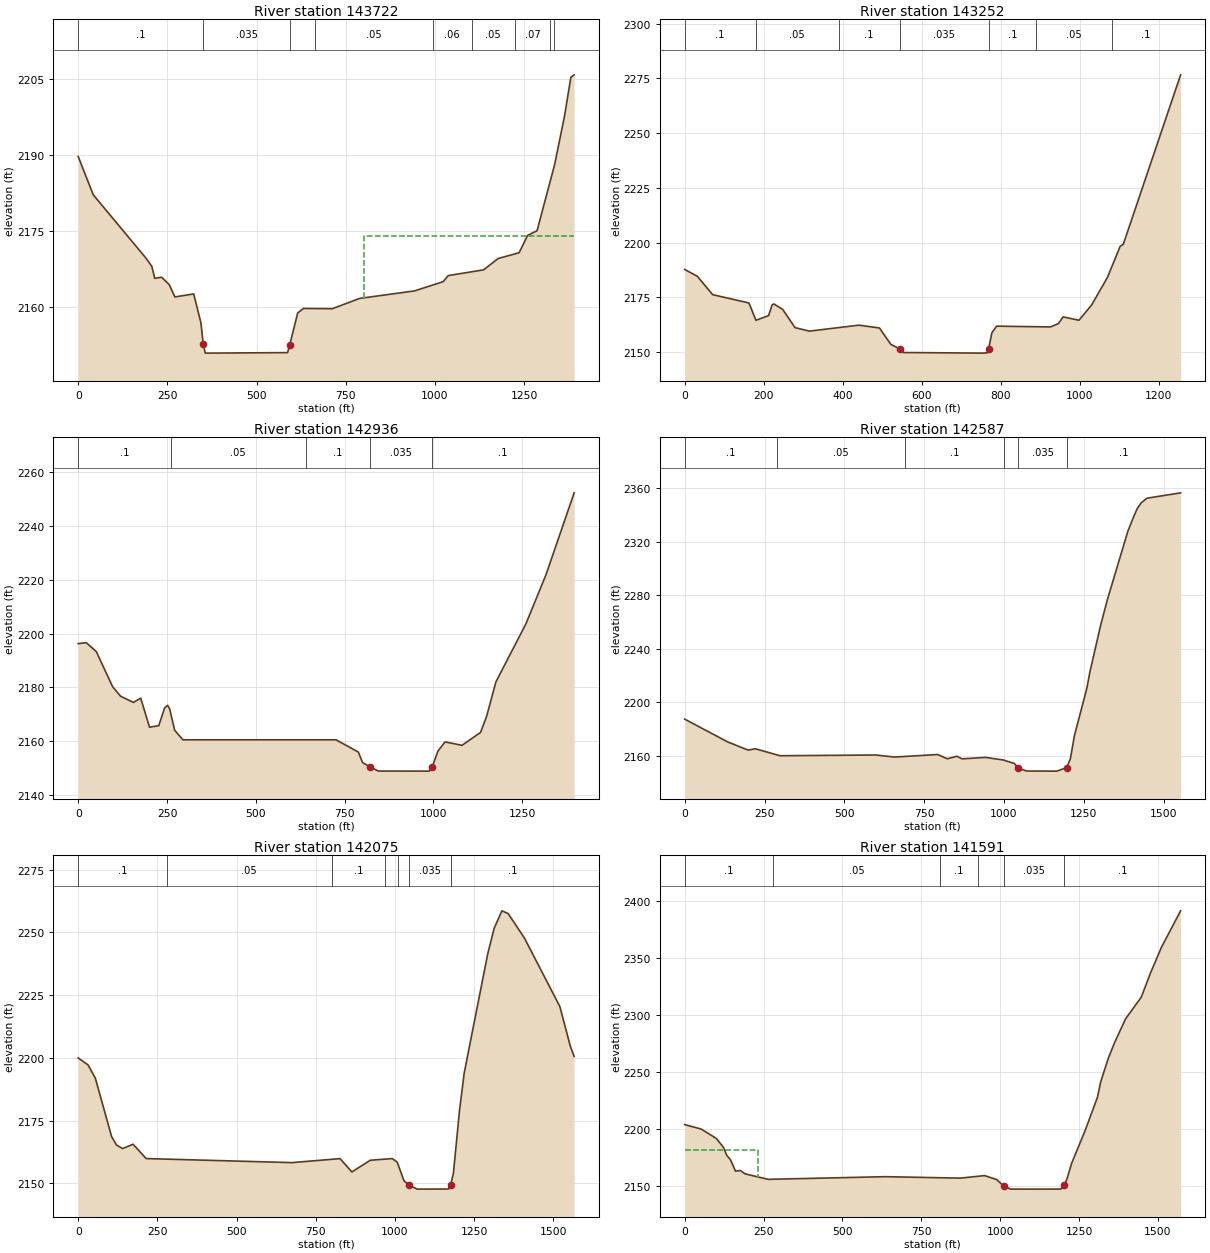
Type RM Length L Ch R = 1 ,143722  ,456.4,469.7,480.9
XS GIS Cut Line= 4
2242071.85913369454087.3017955442242089.25338253454307.682592768
2242155.65824491454725.0845849172242504.13619239455385.701864632
#Sta/Elev= 30
       0 2189.71      42 2182.18   190.5 2169.64   206.5 2168.06   214.5 2165.72
   233.8 2165.92     255 2164.49   271.2 2162.04   323.8 2162.64   344.1 2156.94
   350.72152.686   356.2 2150.97   587.1 2151.07  593.072152.587   615.5  2158.9
   631.7 2159.77   712.3 2159.72   789.2 2161.75   943.2 2163.23  1023.7 2165.06
  1037.3 2166.24  1136.8 2167.38  1177.5 2169.61  1236.3 2170.75    1260 2174.16
  1286.6 2175.09  1335.8 2188.09  1363.6 2197.68  1381.4 2205.31  1390.6  2205.8
#Mann= 9 ,-1,0
       0      .1       0   350.7    .035       0  593.07    .025       0
  663.72     .05       0  993.72     .06       0 1103.72     .05       0
 1223.72     .07       0 1323.72     .05       0 1333.72     .06       0
#XS Ineff= 2 , 0
                          802.14         2174.05
Permanent Ineff=
       F       F
Bank Sta=350.7,593.07
XS Rating Curve= 0 ,0
Exp/Cntr=0.3,0.1

Type RM Length L Ch R = 1 ,143252  ,313.1,316,318
XS GIS Cut Line= 3
2241863.63087239454011.2616894152241649.90539273454396.896794008
2241705.65986569455209.982857908
#Sta/Elev= 30
       0 2187.77    31.9 2184.67    70.8 2176.26   162.8 2172.46   180.5 2164.56
   212.6  2166.7   221.7 2171.69   226.3 2171.98   248.2 2169.53   279.4 2161.21
   315.9 2159.61   441.2 2162.33   493.3 2161.03   522.1 2153.56   544.6 2151.47
   553.4 2149.84     751 2149.56     766 2149.67   769.7 2151.48     778 2158.89
     790 2161.87   926.3 2161.52   946.4 2163.04   958.4 2166.11   998.5 2164.57
  1030.6 2171.55  1070.7 2184.16  1102.7 2198.29  1110.8 2199.28  1255.9 2276.62
#Mann= 7 ,-1,0
       0      .1       0     180     .05       0     390      .1       0
   544.6    .035       0   769.7      .1       0   890.9     .05       0
  1080.9      .1       0
Bank Sta=544.6,769.7
XS Rating Curve= 0 ,0
Exp/Cntr(USF)=0,0
Exp/Cntr=0.3,0.1

Type RM Length L Ch R = 1 ,142936  ,316.7,349.9,391.3
XS GIS Cut Line= 4
2241835.75363591453964.7996286212241352.54820365454448.005060881
2241361.84061581454940.5029053012241515.16541643455098.473912001
#Sta/Elev= 30
       0 2196.27    22.6 2196.64    50.9 2193.33    96.7 2180.31   119.3 2176.75
   155.5 2174.44   175.9 2176.04   200.8 2165.25   226.8 2165.82   243.2 2172.41
   251.7 2173.36   257.4 2172.09   271.5 2164.14   294.7 2160.57   725.7 2160.57
   788.5 2156.03   800.6 2152.11   820.6 2150.58   844.6 2148.97   988.6 2148.94
   996.72150.574  1012.6 2156.36  1032.6 2159.79  1080.5 2158.53  1132.6 2163.31
  1149.8 2169.34  1175.9 2182.07  1260.1 2203.57  1316.7  2221.8  1396.1 2252.26
#Mann= 5 ,-1,0
       0      .1       0     260     .05       0     640      .1       0
   820.6    .035       0   996.7      .1       0
Bank Sta=820.6,996.7
XS Rating Curve= 0 ,0
Exp/Cntr(USF)=0,0
Exp/Cntr=0.3,0.1

Type RM Length L Ch R = 1 ,142587  ,465.8,512,570.7
XS GIS Cut Line= 3
2241699.54101815453811.9467265722241137.45035498454310.844729072
      2240851.42      455059.787
#Sta/Elev= 30
       0 2187.34   134.4 2170.33   198.8 2164.16   221.4 2165.17   298.7 2159.95
   598.4  2160.5     657 2158.97   792.6 2160.86   822.5 2157.69   852.5 2159.57
     869 2157.61   942.5 2158.71   998.1 2156.76  1032.4 2154.191045.199 2150.72
  1070.9 2148.52  1165.1 2148.441196.7992151.068  1207.9 2157.58  1220.8 2175.09
  1259.7 2210.54  1268.7 2222.14  1302.1 2256.85  1323.5 2276.42  1387.8 2327.71
    1405 2338.06  1417.4 2344.84  1429.8 2349.17  1447.7 2352.61  1553.3 2356.65
#Mann= 6 ,-1,0
       0      .1       0     290     .05       0     690      .1       0
 1001.56    .025       01045.199    .035       01196.799      .1       0
Bank Sta=1045.199,1196.799
XS Rating Curve= 0 ,0
Exp/Cntr=0.3,0.1

Type RM Length L Ch R = 1 ,142075  ,483.2,483.8,486.9
XS GIS Cut Line= 2
2241509.62780155453679.087932005     2240243.748      454601.625
#Sta/Elev= 30
       0 2199.99    31.2  2197.2    54.1 2191.92   105.4 2168.69   120.6 2165.35
     140 2163.87   173.3 2165.61   214.6  2159.9   674.9 2158.28   827.1 2159.87
   864.3 2154.57   922.4 2159.22   991.7 2159.89  1007.5 2158.49  1029.1 2150.99
  1046.1 2149.25  1070.4 2147.72  1169.9 2147.76  1176.4 2149.34    1185 2154.02
  1204.5 2179.26  1219.2 2194.02  1293.6 2241.55  1313.8 2251.66  1338.2 2258.61
    1358 2257.51  1409.4 2247.75  1521.3 2220.46  1554.3 2204.69  1566.4 2200.58
#Mann= 7 ,-1,0
       0      .1       0     280     .05       0     800      .1       0
     970    .025       0    1010      .1       0  1046.1    .035       0
  1176.4      .1       0
Bank Sta=1046.1,1176.4
XS Rating Curve= 0 ,0
Exp/Cntr=0.3,0.1

Type RM Length L Ch R = 1 ,141591  ,464.5,489,513.8
XS GIS Cut Line= 2
2241266.30270382453303.641273467     2239966.273      454187.254
#Sta/Elev= 30
       0 2203.66    52.5 2199.71   100.5 2191.45   123.6 2183.37   133.2 2176.75
   145.1  2172.8     161 2162.83   176.7 2163.32   191.2 2160.42   264.7 2155.58
   636.2 2157.91   873.1 2156.64   950.5 2158.87   989.2 2155.311010.5742149.793
  1033.5 2146.98  1192.3 2147.031203.4742150.333    1212 2156.25  1226.6 2169.76
  1269.6 2198.65  1308.4 2227.72  1318.5 2241.11  1342.3  2261.6  1361.8 2275.14
  1397.4 2296.51  1447.2 2315.56  1476.9  2337.1  1511.4  2359.5  1571.9 2391.37
#Mann= 6 ,-1,0
       0      .1       0     280     .05       0     810      .1       0
     930    .025       01010.574    .035       01203.474      .1       0
#XS Ineff= 2 , 0
          231.33 2181.22
Permanent Ineff=
       F       F
Bank Sta=1010.574,1203.474
XS Rating Curve= 0 ,0
Exp/Cntr=0.3,0.1

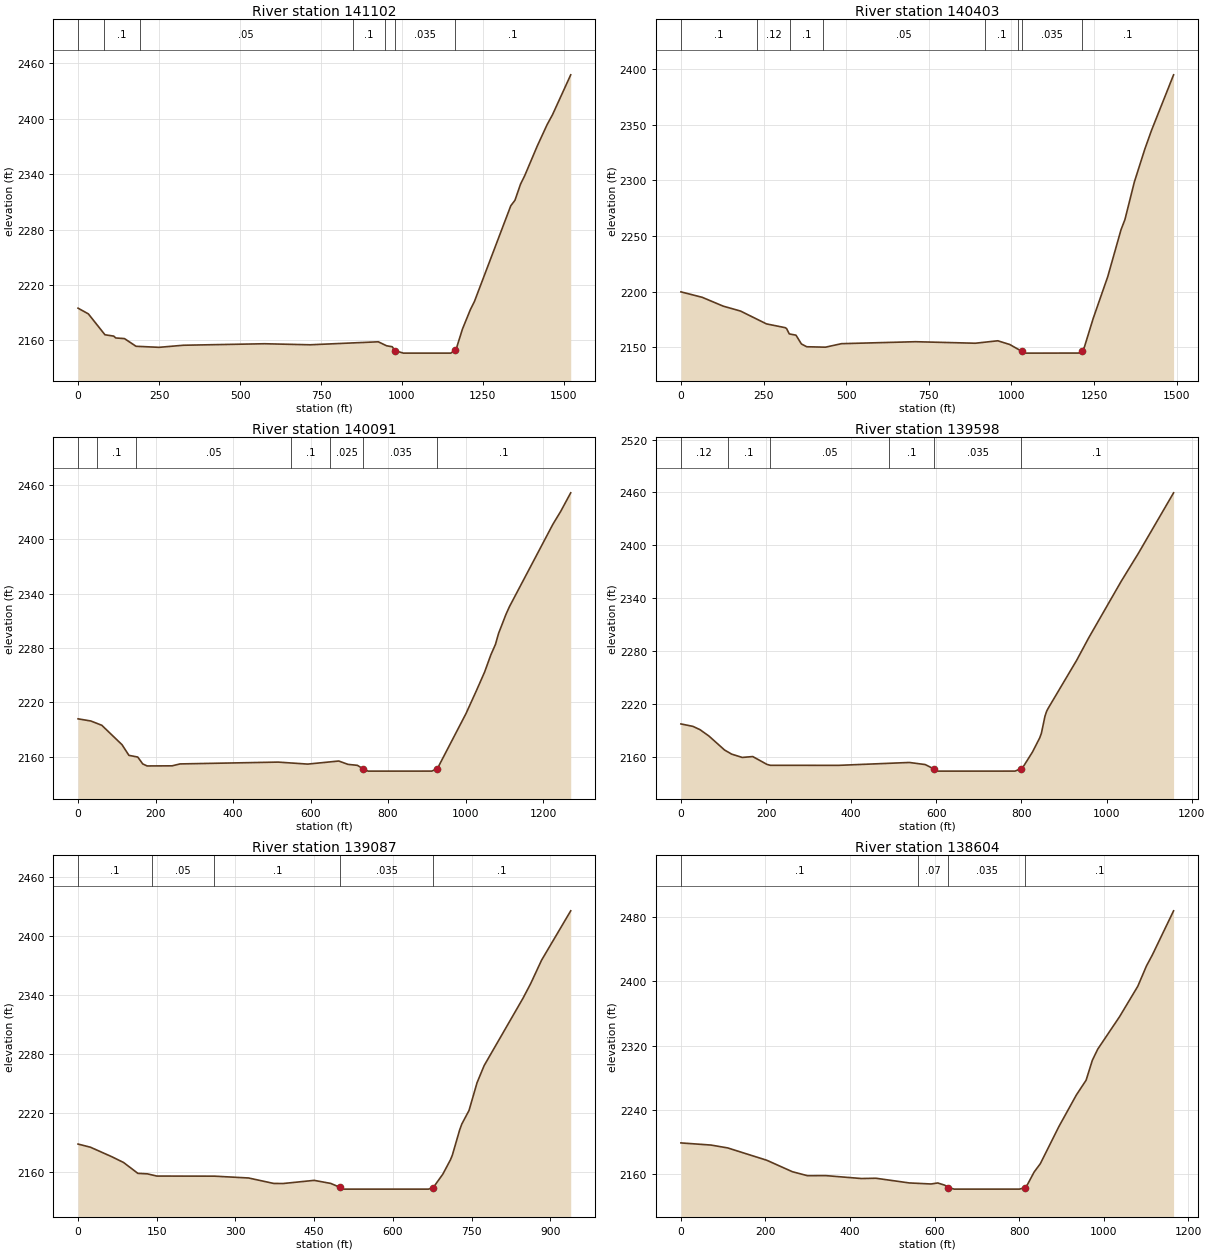
Type RM Length L Ch R = 1 ,141102  ,665.1,699.1,735.5
XS GIS Cut Line= 3
2241064.67482309453070.3511413762240492.37454893453352.717428912
     2239672.281      453679.586
#Sta/Elev= 30
       0 2194.77    31.8  2188.6    83.1 2165.95     110 2164.51   116.5 2162.49
   143.3  2161.8     179 2153.48   250.3 2152.34   325.1  2154.6   575.9 2156.22
   716.5  2155.1   926.9 2158.34   952.7    2154   969.9 2152.98   978.6  2148.8
  1004.4 2146.06  1150.8 2146.071163.7622149.039  1168.8 2152.01  1186.7 2172.08
  1211.3 2193.27  1223.7 2201.98    1336 2305.73  1348.9 2311.72  1366.1  2329.2
    1379 2338.36  1417.6 2370.39  1447.9 2393.48  1465.1 2404.62    1521 2447.61
#Mann= 7 ,-1,0
       0     .12       0      80      .1       0     190     .05       0
  848.17      .1       0  948.17    .025       0   978.6    .035       0
1163.762      .1       0
Bank Sta=978.6,1163.762
XS Rating Curve= 0 ,0
Exp/Cntr=0.3,0.1

Type RM Length L Ch R = 1 ,140403  ,300.9,312.1,326.6
XS GIS Cut Line= 3
 2241115.5916936452701.031575017 2240641.6786735452780.017078367
2239633.45195426452845.063963479
#Sta/Elev= 30
       0  2199.8    64.3 2194.92   128.2 2186.95   180.4 2182.56   258.9 2171.03
   315.7 2167.64   319.8  2166.8   327.9 2162.05   348.2 2160.89   364.6 2153.02
   380.6 2150.51   437.4 2150.12     486 2153.27   710.4 2155.03   890.8 2153.67
   958.9 2155.86   995.1 2152.52  1032.42146.252  1039.1 2144.78  1203.5 2144.84
  1213.4 2146.25    1221 2150.31  1247.5  2175.9  1291.6 2213.48  1331.7 2255.57
  1343.7 2264.86    1372 2298.39  1403.9 2328.12  1423.9 2344.75  1490.8  2394.7
#Mann= 8 ,-1,0
       0      .1       0     230     .12       0     330      .1       0
     430     .05       0  920.45      .1       0 1020.45    .025       0
  1032.4    .035       0  1213.4      .1       0
Bank Sta=1032.4,1213.4
XS Rating Curve= 0 ,0
Exp/Cntr(USF)=0,0
Exp/Cntr=0.3,0.1

Type RM Length L Ch R = 1 ,140091  ,470.7,492.7,518.1
XS GIS Cut Line= 3
2240844.97673075452474.5209684922240428.77060938452529.688248655
     2239578.306       452485.08
#Sta/Elev= 30
       0 2201.91    33.1 2199.52    61.3 2194.81   113.5 2173.39   131.3 2161.66
   154.1 2159.77     167 2152.16   178.3 2149.96   242.9 2150.09   263.1 2152.19
   516.6  2154.2   592.7    2152   672.8 2155.39   696.8 2151.69   720.9 2150.64
736.6763 2146.57   748.9 2144.25   913.1 2144.28927.47352147.088  1001.2  2207.7
  1028.7 2233.55  1049.3 2253.56  1065.3  2272.4  1077.3 2284.05  1085.4 2296.25
  1104.7 2317.43  1113.4 2325.65  1225.5 2416.46  1245.6 2430.64  1271.5 2451.13
#Mann= 7 ,-1,0
       0     .12       0      50      .1       0     150     .05       0
  549.85      .1       0  649.85    .025       0736.6763    .035       0
927.4735      .1       0
Bank Sta=736.6763,927.4735
XS Rating Curve= 0 ,0
Exp/Cntr=0.3,0.1

Type RM Length L Ch R = 1 ,139598  ,481.9,511.3,536.5
XS GIS Cut Line= 2
2240795.45922281452202.080066844     2239675.798      451908.917
#Sta/Elev= 30
       0 2197.02    28.2 2194.24    44.7 2190.54    65.7 2183.32   102.6 2167.37
   119.2 2162.72     144 2158.95   168.8 2159.95   201.9 2151.11   210.1 2150.01
   370.4 2149.97   536.8 2153.24     574 2150.85   594.7 2145.82   598.8 2143.65
   602.9 2143.41   784.9 2143.44   798.7 2146.03   805.6 2149.46   825.9  2165.1
   842.8 2181.09   846.9 2186.45   855.2 2205.69   859.3 2211.59   863.4 2215.28
   929.6 2269.21   958.5 2295.22    1034 2358.73    1075 2391.05  1157.4 2459.49
#Mann= 6 ,-1,0
       0     .12       0     110      .1       0     210     .05       0
     490      .1       0   594.7    .035       0   798.7      .1       0
Bank Sta=594.7,798.7
XS Rating Curve= 0 ,0
Exp/Cntr=0.3,0.1

Type RM Length L Ch R = 1 ,139087  ,467.3,482.8,495.5
XS GIS Cut Line= 2
2240820.63258847451828.7895897792239993.36742989451384.732112715
#Sta/Elev= 30
       0 2188.31    23.7 2185.08    64.1  2175.5    86.8 2169.57     114 2158.55
   132.2 2158.03   150.3  2155.8     260  2155.7     325 2153.84   372.8 2148.31
   390.9 2148.23     450 2151.43   481.6 2148.32   499.3 2144.29   504.4 2142.55
     509 2142.53   667.9 2142.53     677 2144.18   695.1 2157.68   709.6 2172.19
   713.3 2177.01   727.3 2202.73   731.4 2208.69   745.1 2222.44   760.4 2250.63
     774 2268.09   847.9 2336.36   862.7 2351.38   883.3    2375   938.9 2425.18
#Mann= 5 ,-1,0
       0      .1       0     140     .05       0     260      .1       0
   499.3    .035       0     677      .1       0
Bank Sta=499.3,677
XS Rating Curve= 0 ,0
Exp/Cntr=0.3,0.1

Type RM Length L Ch R = 1 ,138604  ,372.7,376.2,379.3
XS GIS Cut Line= 2
2241147.30863916451565.5148189982240199.93434105450887.305030645
#Sta/Elev= 30
       0 2198.69    71.3    2196   110.5 2192.46   203.2 2177.04   263.4 2162.81
     299 2157.84   343.3 2157.88   426.6 2154.29   461.2 2154.62   540.1 2148.78
   591.5 2147.47   607.4 2148.72   623.7 2146.03     6322143.013   646.5 2141.06
   800.8 2141.08   813.8 2143.01   819.6 2146.81   835.2 2162.28     850 2172.85
   893.9 2219.11   935.1 2258.42   958.2 2276.87     973 2301.76   985.8 2315.67
  1037.5 2356.23  1080.5 2394.06  1100.9 2419.32  1114.9 2433.14  1165.1 2488.11
#Mann= 4 ,-1,0
       0      .1       0     560     .07       0     632    .035       0
   813.8      .1       0
Bank Sta=632,813.8
XS Rating Curve= 0 ,0
Exp/Cntr(USF)=0,0
Exp/Cntr=0.3,0.1

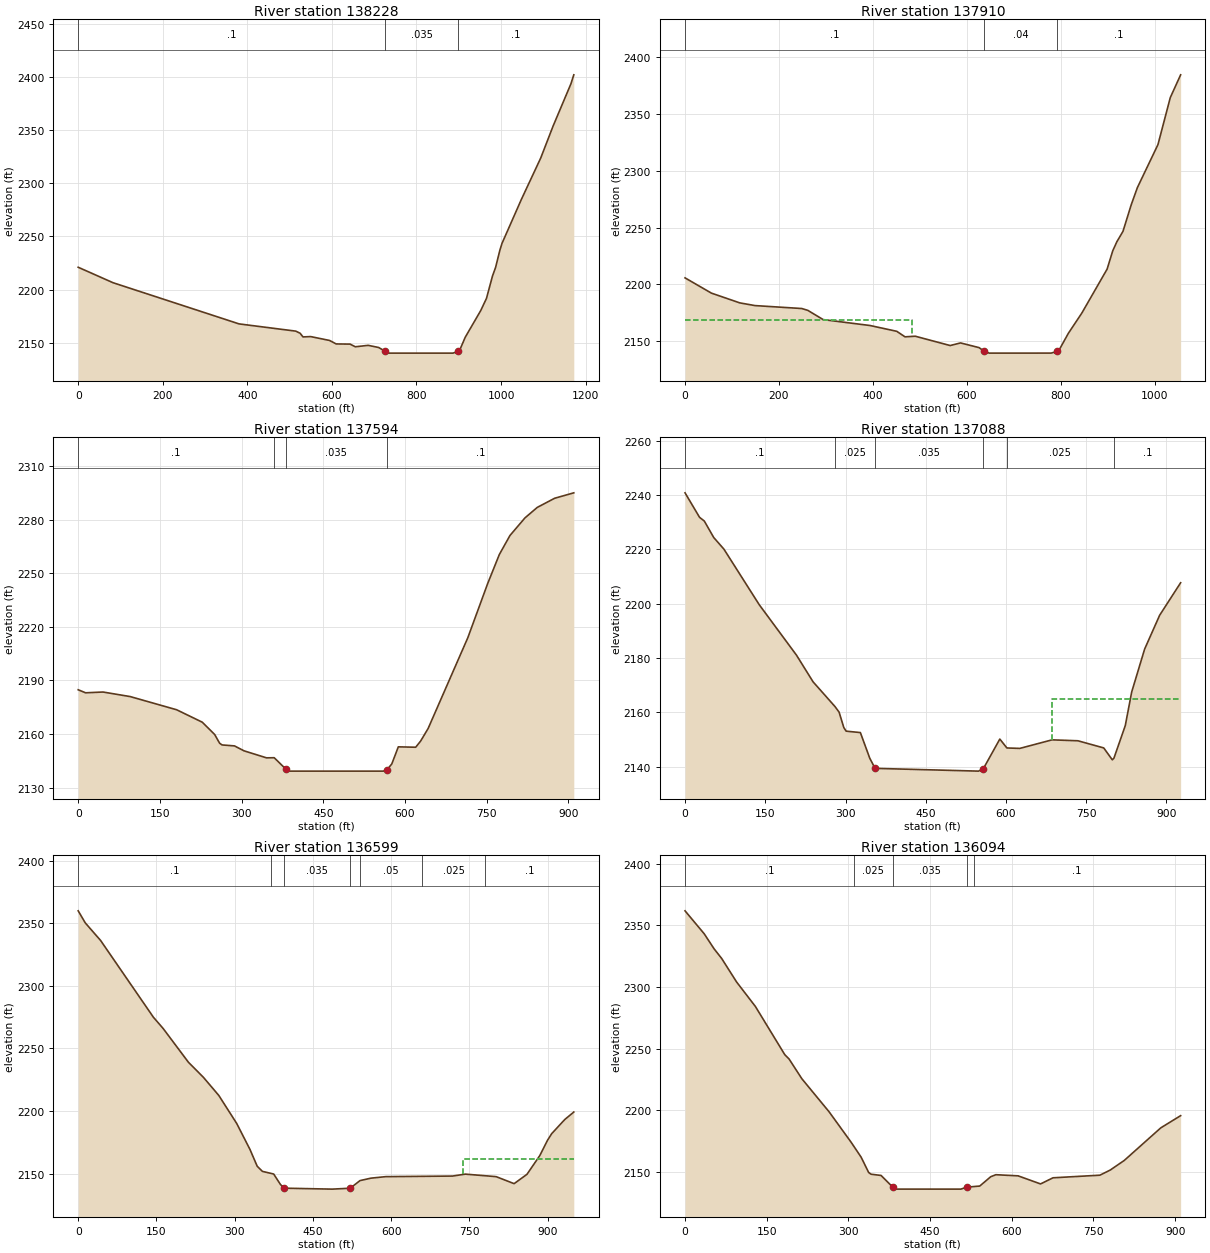
Type RM Length L Ch R = 1 ,138228  ,341.6,317.7,293.3
XS GIS Cut Line= 2
 2241437.6672048451340.8578266062240505.12874581450630.856954424
#Sta/Elev= 30
       0 2221.05    82.3 2206.53   380.5 2167.77   514.6 2160.97   524.7 2159.02
   531.7 2155.54   549.9 2155.83   594.5  2152.2   610.2 2148.91     643 2148.76
   655.4 2146.25   685.9  2147.6   710.7 2145.56   725.8 2142.09   735.9 2140.28
   886.7 2140.28   899.22142.152   904.1 2144.79   915.4 2155.27   952.1 2180.38
   965.6 2191.78   979.8 2212.82   987.2 2220.97   997.3 2237.14  1002.3  2243.5
  1047.6 2284.41    1094 2323.92    1123 2353.74  1165.4 2393.71  1172.1 2402.06
#Mann= 3 ,-1,0
       0      .1       0   725.8    .035       0   899.2      .1       0
Bank Sta=725.8,899.2
XS Rating Curve= 0 ,0
Exp/Cntr(USF)=0,0
Exp/Cntr=0.3,0.1

Type RM Length L Ch R = 1 ,137910  ,309.9,316.4,326.1
BEGIN DESCRIPTION:
mannings n increased in this area to correct drawdown and is more representative of imagery
END DESCRIPTION:
XS GIS Cut Line= 3
2241619.93608542450669.0062550192241265.99535212 450713.51377238
2240628.05426995450429.513423507
#Sta/Elev= 30
       0  2205.8    56.2 2192.39   116.7 2183.82   148.9 2181.46   248.5 2178.88
   261.4 2177.26   294.1 2169.15   393.7 2163.97   450.7 2158.88   468.2 2154.03
   490.1 2154.56   564.5 2146.37   586.4 2148.68   625.8 2144.56   635.9 2141.66
   647.7 2139.72   779.5 2139.75   792.2 2141.27   797.7 2143.48   815.8 2156.97
   844.7  2174.9   898.5 2213.49   910.4 2229.44   919.2 2237.46   932.3 2246.66
   949.8 2269.94   962.9 2285.01  1006.7 2322.76    1033 2364.08    1055 2384.05
#Mann= 3 ,-1,0
       0      .1       0   635.9     .04       0   792.2      .1       0
#XS Ineff= 2 , 0
          484.06 2168.59
Permanent Ineff=
       F       F
Bank Sta=635.9,792.2
XS Rating Curve= 0 ,0
Exp/Cntr(USF)=0,0
Exp/Cntr=0.3,0.1

Type RM Length L Ch R = 1 ,137594  ,511.9,505.7,497.8
XS GIS Cut Line= 2
     2241504.135      450514.409     2240705.316      450078.532
#Sta/Elev= 30
       0 2184.78    13.6 2183.08    45.5 2183.52    95.6 2180.96   180.7 2173.59
   227.8 2166.63   250.6 2159.73   259.7 2154.84   264.2 2153.89     287 2153.34
   304.5 2150.58   345.8 2146.66   359.9 2146.73   381.2 2140.38   387.3 2139.22
   560.4 2139.22   566.9 2139.97   575.8 2143.24   587.8 2152.82   619.7  2152.6
   628.7 2156.03   642.5 2163.08   715.4 2213.92   751.8 2244.21   773.3 2260.54
   792.8 2271.18   820.4 2281.05   842.9  2286.9   874.8 2292.02     910 2295.07
#Mann= 4 ,-1,0
       0      .1       0     360    .025       0   381.2    .035       0
   566.9      .1       0
Bank Sta=381.2,566.9
XS Rating Curve= 0 ,0
Exp/Cntr=0.3,0.1

Type RM Length L Ch R = 1 ,137088  ,594.2,489.1,371.8
XS GIS Cut Line= 3
     2241732.795      450033.2142241189.27034338449777.728069461
     2240865.269       449742.72
#Sta/Elev= 30
       0 2240.81    27.2 2231.77      36 2230.43    53.7 2224.34    72.7 2220.07
   138.8 2199.58   208.4 2181.01   239.4 2171.19   280.1 2162.15     288 2160.04
   296.8 2154.38   301.2 2153.03   327.8 2152.51   345.4 2143.04   355.3 2139.33
   548.7 2138.31   557.6 2139.18   588.5 2150.12   601.7 2146.84   625.8 2146.68
   686.2 2149.83   734.4 2149.49   782.7 2146.86   798.8 2142.47   801.8 2143.08
     823 2155.06     835 2167.45   859.2 2183.26   887.3 2195.73   926.5 2207.69
#Mann= 6 ,-1,0
       0      .1       0   280.1    .025       0   355.3    .035       0
   557.6     .05       0   601.7    .025       0   801.8      .1       0
#XS Ineff= 2 , 0
                           686.2         2165.03
Permanent Ineff=
       F       F
Bank Sta=355.3,557.6
XS Rating Curve= 0 ,0
Exp/Cntr=0.3,0.1

Type RM Length L Ch R = 1 ,136599  ,541.5,505.2,466.2
XS GIS Cut Line= 2
     2241623.106      449113.1022240851.21827261449667.260794235
#Sta/Elev= 30
       0 2359.82    13.6 2350.17      43 2336.13   144.2 2274.84   162.7 2265.94
   211.4 2238.86     240 2226.88   269.5 2212.43     304 2189.94   329.4  2169.2
   343.2 2155.85   353.2 2151.74   374.8 2149.62   387.7 2141.32   394.8 2138.32
   486.6 2137.56   521.4 2138.27   540.3 2144.36   561.1 2146.31   589.6 2147.53
   717.6 2147.99   742.2 2149.54   801.3 2147.52   835.8 2141.93   860.4 2149.38
     885 2164.34   899.8 2176.57   907.9 2181.89   932.9 2193.16   950.2 2199.12
#Mann= 7 ,-1,0
       0      .1       0     370    .025       0   394.8    .035       0
   521.4      .1       0     540     .05       0     660    .025       0
     780      .1       0
#XS Ineff= 2 , 0
                          738.02         2161.39
Permanent Ineff=
       F       F
Bank Sta=394.8,521.4
XS Rating Curve= 0 ,0
Exp/Cntr=0.3,0.1

Type RM Length L Ch R = 1 ,136094  ,511.9,500,489.9
XS GIS Cut Line= 2
     2241089.045      448666.354      2240647.57      449462.093
#Sta/Elev= 30
       0 2361.69    35.1 2343.15    53.5 2330.83    67.4 2323.01    94.7 2304.02
   129.2  2284.2   183.2 2245.11     191 2241.65   214.5 2225.64   264.6  2198.8
   305.1 2174.09   323.4 2162.04   337.2 2149.63   341.7 2148.26     360 2147.26
   381.1 2137.96   387.5  2136.2   506.4 2136.18   517.6 2137.81   541.1 2138.66
   561.3 2146.22   570.7 2147.86   611.6 2146.94   652.8 2140.39   675.7 2145.36
   761.8 2147.48   780.9 2151.68   806.5 2159.43   873.6 2185.84     910 2195.71
#Mann= 5 ,-1,0
       0      .1       0     310    .025       0   381.1    .035       0
   517.6    .025       0     530      .1       0
Bank Sta=381.1,517.6
XS Rating Curve= 0 ,0
Exp/Cntr=0.3,0.1