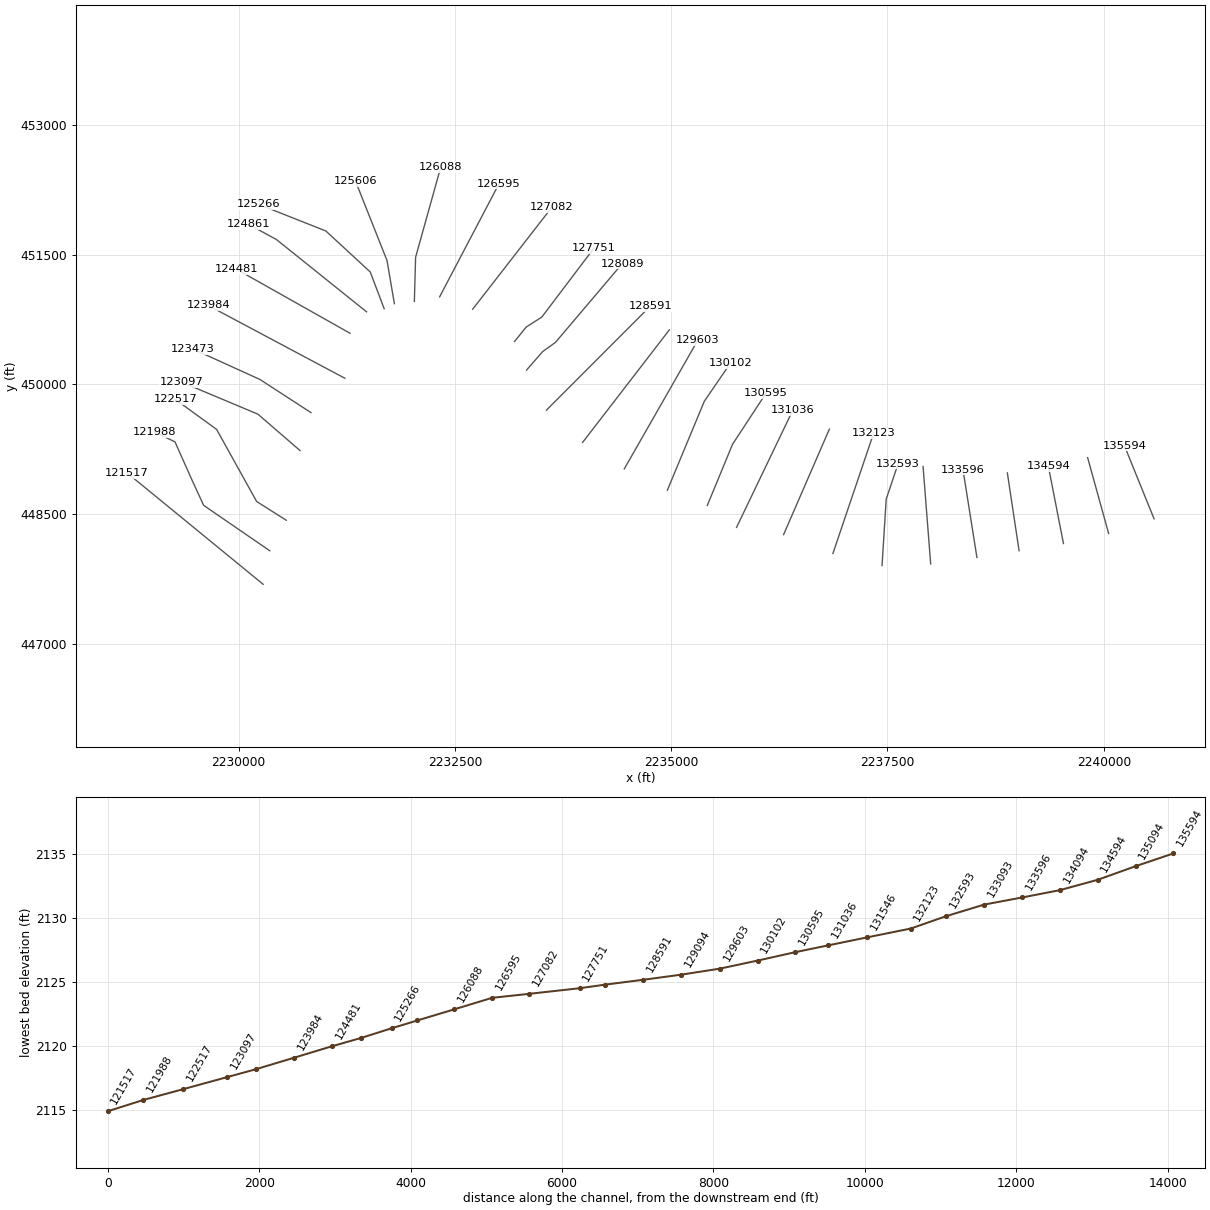
HEC-RAS study GRNBRRRV.prj: GRNBRRRV

--- GRNBRRRV.g01 (geometry) --- (continued)

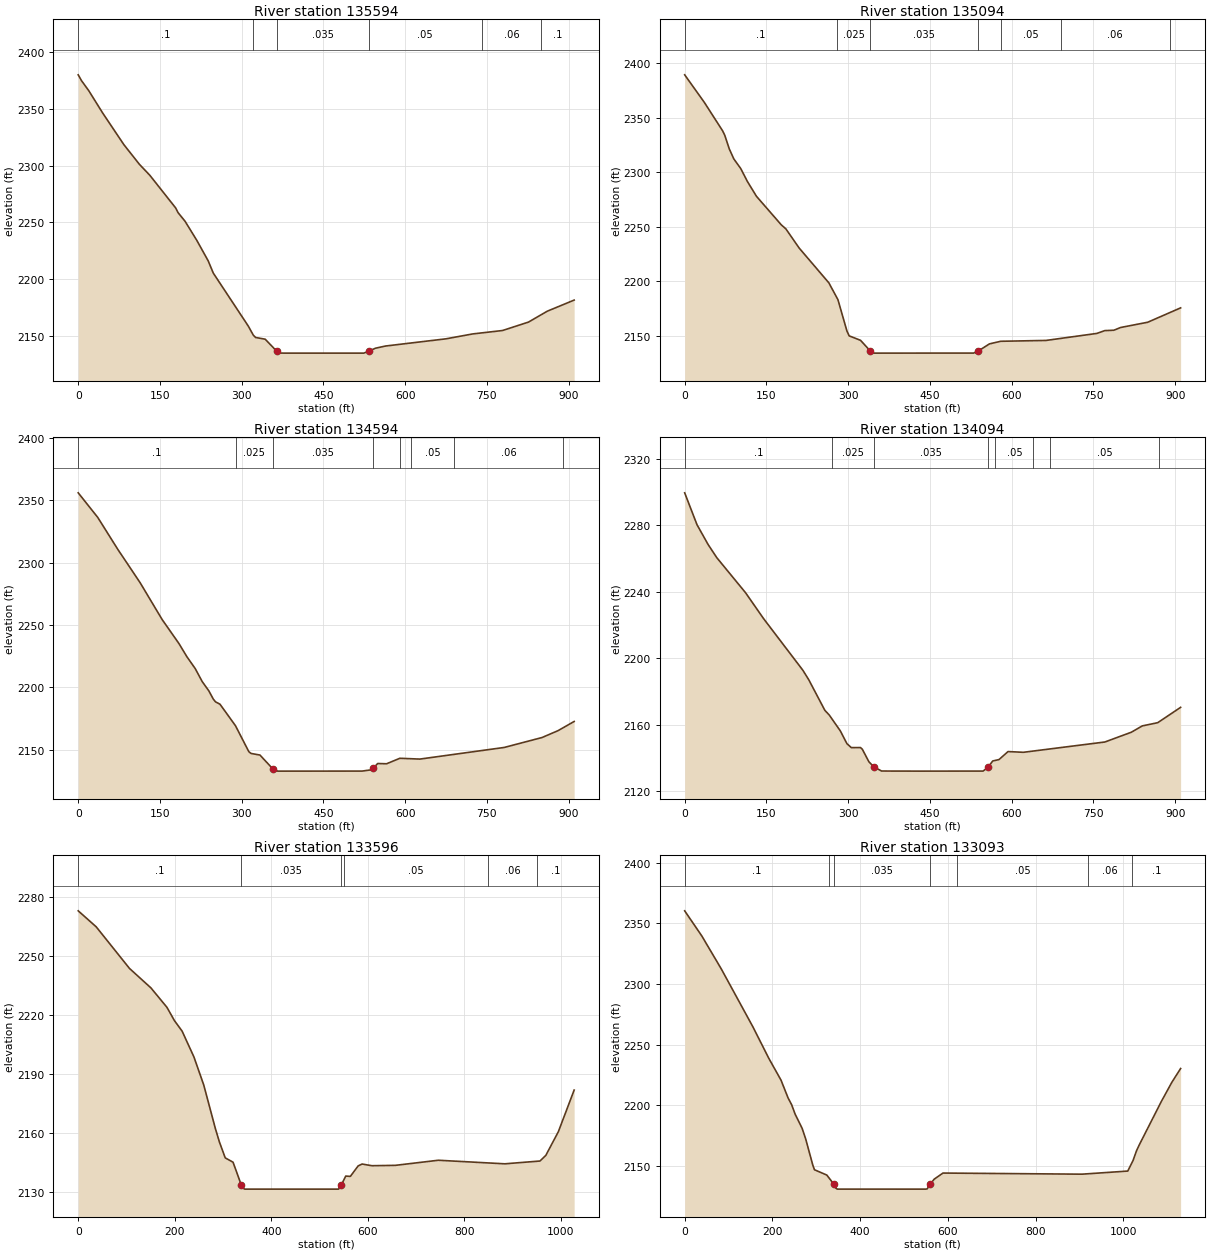
Type RM Length L Ch R = 1 ,135594  ,514.1,500,488.5
XS GIS Cut Line= 2
     2240580.999      448443.454     2240239.297      449286.864
#Sta/Elev= 30
       0 2379.75     6.2 2374.51    19.1    2366      45  2346.1    83.9 2318.29
   112.5 2300.96   131.3  2291.5   178.8 2262.73   183.2 2258.58   196.1 2250.97
   217.7 2234.15   238.5 2216.18   247.9 2205.39   312.2 2158.76   321.2 2150.94
   325.5 2148.82   343.1  2147.3   364.4 2136.69   368.7 2135.17   377.3 2135.06
   524.1 2135.06   532.7 2136.73   545.6  2139.4     564 2141.31   674.6 2147.62
   723.7 2151.93   778.7 2154.95   826.2 2162.35   860.7 2171.92     910  2181.7
#Mann= 6 ,-1,0
       0      .1       0     320    .025       0   364.4    .035       0
   532.7     .05       0     740     .06       0     850      .1       0
Bank Sta=364.4,532.7
XS Rating Curve= 0 ,0
Exp/Cntr=0.3,0.1

Type RM Length L Ch R = 1 ,135094  ,510.2,500,491.9
XS GIS Cut Line= 2
     2240055.767      448274.209     2239813.067      449151.248
#Sta/Elev= 30
       0 2389.36    36.3 2363.92    69.5 2338.08    73.5 2334.01    81.9 2321.32
    90.2  2312.2   102.9 2303.36   115.1 2291.51   131.7 2277.94   177.4 2251.67
   185.7 2248.05   210.1 2230.44   264.6 2198.51   281.2 2183.11   297.8 2154.21
   301.9 2149.89   322.7  2145.8   340.2 2136.26   347.6 2134.06   530.2 2134.11
   538.4 2135.91   559.2 2142.53     580 2144.93     663  2145.7   756.3 2152.14
   770.9 2154.72   787.5 2155.06   799.9 2157.57   849.7  2162.4     910 2175.57
#Mann= 7 ,-1,0
       0      .1       0     280    .025       0   340.2    .035       0
   538.4      .1       0     580     .05       0     690     .06       0
     890      .1       0
Bank Sta=340.2,538.4
XS Rating Curve= 0 ,0
Exp/Cntr=0.3,0.1

Type RM Length L Ch R = 1 ,134594  ,505.3,500,495.5
XS GIS Cut Line= 2
     2239533.913      448157.916     2239359.315       449051.01
#Sta/Elev= 30
       0 2355.87    35.9 2336.15    72.4 2310.77   113.4 2284.03   154.1 2254.35
     185 2235.07   199.5 2224.58   214.7 2215.12   227.5 2204.73   239.7 2197.27
   247.9 2190.67   251.9  2188.5   260.1 2186.61   288.6 2169.36   313.1 2148.55
   317.2 2147.14   333.5 2145.88   356.6 2135.02   366.1    2133   520.9 2133.03
   537.2    2134   541.3  2135.3   549.5  2139.1   565.8 2138.89   590.2 2143.29
   626.9 2142.64   781.8 2151.97   851.1 2159.91   880.4  2165.4     910 2172.76
#Mann= 8 ,-1,0
       0      .1       0     290    .025       0   356.6    .035       0
   541.3    .025       0     590      .1       0     610     .05       0
     690     .06       0     890      .1       0
Bank Sta=356.6,541.3
XS Rating Curve= 0 ,0
Exp/Cntr=0.3,0.1

Type RM Length L Ch R = 1 ,134094  ,496.2,497.1,498.2
XS GIS Cut Line= 2
     2239020.792      448074.794     2238885.413      448974.668
#Sta/Elev= 30
       0 2299.38    22.6 2280.25    42.9 2268.38      59 2260.39   111.7 2239.37
   144.9 2223.75   216.8 2192.82   227.7 2187.08   257.2 2168.72   265.3 2165.89
   285.6 2156.36   297.7 2148.71   305.8 2146.31   322.6 2146.35     326 2145.33
   338.1 2137.77   347.2 2134.76   361.3 2132.25   431.2 2132.19   547.6 2132.22
   556.6  2134.5   565.2 2138.28   576.8 2139.14   593.3 2143.94   621.5  2143.5
     771 2149.69   819.5 2155.55   839.7 2159.36     868 2161.29     910 2170.51
#Mann= 8 ,-1,0
       0      .1       0     270    .025       0   347.2    .035       0
   556.6      .1       0     570     .05       0     640      .1       0
     670     .05       0     870     .06       0
Bank Sta=347.2,556.6
XS Rating Curve= 0 ,0
Exp/Cntr=0.3,0.1

Type RM Length L Ch R = 1 ,133596  ,514.4,503.8,494.2
XS GIS Cut Line= 2
     2238533.678      447996.3062238372.62645478449011.122043254
#Sta/Elev= 30
       0 2272.92    37.3 2264.79   106.2 2243.68   150.7 2233.78   183.8 2223.94
   199.3  2217.2   215.3 2211.83   239.8  2198.7   260.1 2184.48   284.4 2162.18
   292.5 2155.61   304.6 2147.49   320.8 2145.29   337.6 2133.91     341 2132.15
   345.1 2131.62   539.5 2131.62  545.282133.831   554.3 2138.25   563.8 2138.08
     580 2143.41   588.1 2144.36   608.4 2143.51     657 2143.69   746.1 2146.28
   883.8 2144.47   956.7 2145.89   968.8 2148.75   994.8 2160.79  1027.5 2181.91
#Mann= 6 ,-1,0
       0      .1       0   337.6    .035       0  545.28    .025       0
     550     .05       0     850     .06       0     950      .1       0
Bank Sta=337.6,545.28
XS Rating Curve= 0 ,0
Exp/Cntr=0.3,0.1

Type RM Length L Ch R = 1 ,133093  ,516.1,499.6,482.2
XS GIS Cut Line= 2
     2237999.134      447922.1442237911.19018218449049.295473139
#Sta/Elev= 30
       0 2360.37    39.2 2339.58    83.3  2312.6   155.5  2264.8   191.6 2238.97
   219.7 2220.81   235.7 2206.22   243.8 2200.63   251.8 2192.86   267.8 2181.12
   275.9 2172.38   291.9  2151.1   295.9 2147.01     324 2142.65   340.5 2134.93
   344.1 2131.96     348 2131.07   548.7 2131.06   552.7 2131.19   560.1  2135.3
   568.8 2139.25   588.8  2144.3   905.8 2143.38  1010.1 2145.94  1022.1 2154.61
  1030.2  2162.8  1036.5 2167.63  1086.3 2203.04  1110.4 2218.95  1130.6 2230.44
#Mann= 7 ,-1,0
       0      .1       0     330    .025       0   340.5    .035       0
   560.1      .1       0     620     .05       0     920     .06       0
    1020      .1       0
Bank Sta=340.5,560.1
XS Rating Curve= 0 ,0
Exp/Cntr=0.3,0.1

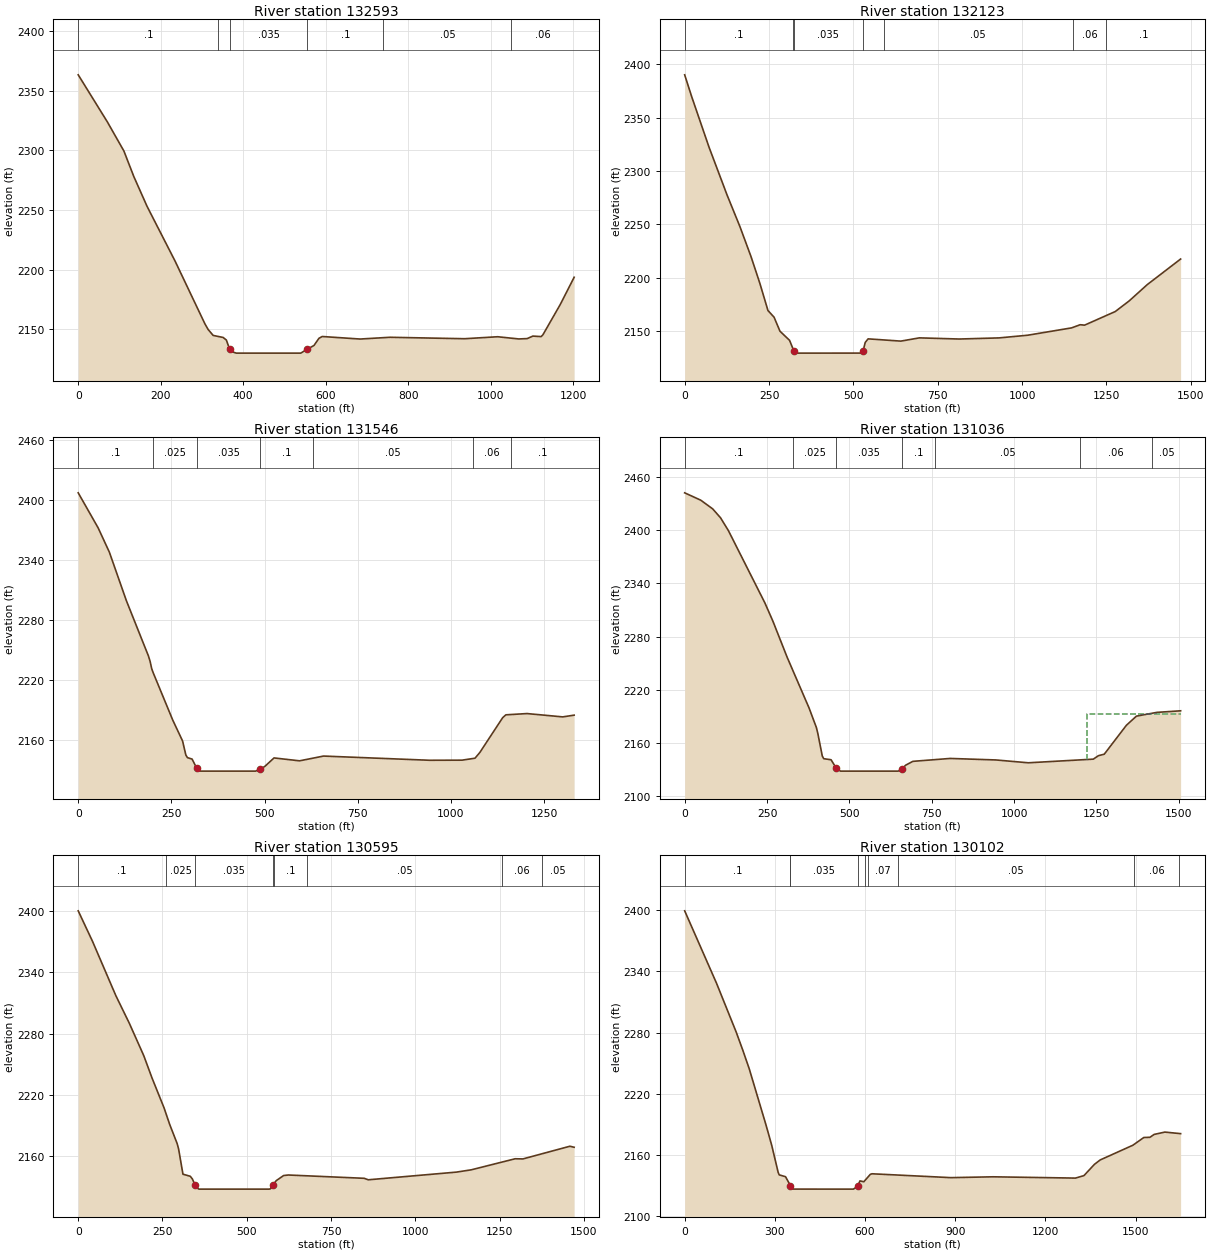
Type RM Length L Ch R = 1 ,132593  ,499.6,469.8,437
XS GIS Cut Line= 3
     2237437.027      447902.5652237485.18292367448671.174630604
2237622.98452032449081.084654006
#Sta/Elev= 30
       0 2363.39    70.8 2323.87   110.8 2299.54   134.9  2278.1   166.9 2253.21
   235.1 2207.14   307.2 2154.74   315.2 2149.89   327.3 2144.99   351.3  2143.3
   359.3 2141.11   367.3 2133.27   371.3  2131.5   383.4 2130.16   539.7 2130.16
   555.7 2133.55   571.7 2136.56   583.8 2142.59   591.8 2144.09   683.5 2141.97
     756 2143.44   936.8 2142.23  1017.2 2143.89  1068.2 2142.04  1088.7 2142.34
  1102.5 2144.44  1122.5    2144  1126.7 2145.45  1168.9  2170.9  1202.6 2193.75
#Mann= 6 ,-1,0
       0      .1       0     340    .025       0   367.3    .035       0
   555.7      .1       0     740     .05       0 1050.12     .06       0
Bank Sta=367.3,555.7
XS Rating Curve= 0 ,0
Exp/Cntr=0.3,0.1

Type RM Length L Ch R = 1 ,132123  ,586.2,576.8,568.7
XS GIS Cut Line= 2
2236869.07108121448042.154362312 2237340.0501009449434.740476085
#Sta/Elev= 30
       0 2390.15    20.6 2369.86    72.1 2322.38   125.6 2277.51   163.7 2247.89
     197  2219.4   222.8 2194.71   246.9 2169.13     265 2162.87   282.5 2149.75
   310.9 2141.18   323.5  2131.4   332.6 2129.19   522.6 2129.22   526.8 2129.44
   528.6 2131.04   535.2 2139.18   543.7 2142.57   640.8 2140.45   695.7  2143.5
   813.9 2142.41   932.2 2143.47  1016.6 2145.97  1147.1 2152.87  1172.3 2155.81
  1185.5 2155.43  1276.5 2168.21  1317.5 2178.12  1371.3 2193.45  1470.1 2217.42
#Mann= 7 ,-1,0
       0      .1       0     320    .025       0   323.5    .035       0
   528.6      .1       0     590     .05       0    1150     .06       0
    1250      .1       0
Bank Sta=323.5,528.6
XS Rating Curve= 0 ,0
Exp/Cntr(USF)=0,0
Exp/Cntr=0.3,0.1

Type RM Length L Ch R = 1 ,131546  ,515.5,510.9,507.4
XS GIS Cut Line= 2
2236299.24461294448260.2002047612236828.36919062449481.256922474
#Sta/Elev= 30
       0 2407.09    53.4 2372.06    83.6  2347.7   129.2 2299.17   188.5 2243.74
   192.9  2238.4   197.2 2231.05   201.6 2226.63   253.8 2179.49   280.1 2158.64
   288.8 2144.65   293.1 2142.01   305.6 2140.56   318.32131.177     328  2128.5
   476.2 2128.51   488.1 2130.63   500.2 2133.04   525.5 2141.71   593.9 2138.81
   658.4 2143.58   942.7 2139.37  1029.9 2139.47  1064.8 2141.44  1077.8 2147.22
  1139.1 2182.05  1147.6 2184.86  1204.3 2186.12  1300.1 2182.79  1330.8 2184.54
#Mann= 7 ,-1,0
       0      .1       0     200    .025       0   318.3    .035       0
   488.1      .1       0     630     .05       0    1060     .06       0
    1160      .1       0
Bank Sta=318.3,488.1
XS Rating Curve= 0 ,0
Exp/Cntr(USF)=0,0
Exp/Cntr=0.3,0.1

Type RM Length L Ch R = 1 ,131036  ,434.1,440.8,448.1
XS GIS Cut Line= 2
2235755.58364577448344.5112638412236406.81389522449702.210042822
#Sta/Elev= 30
       0 2442.48    48.9 2434.14      85 2424.36   108.9 2414.25   132.9 2399.68
   243.8 2317.84   267.8 2297.46   311.3 2256.47   377.8 2199.16     400 2177.07
   404.4 2170.28   417.8 2144.96   422.2 2141.92   444.4 2140.75   460.6 2131.05
   473.1 2127.88   648.4 2127.88   660.92130.459   670.6 2134.52   692.8 2138.93
     806 2142.22   945.4  2140.5  1043.3  2137.3  1240.7 2141.42  1256.2 2145.32
    1274 2147.04  1341.1 2179.68  1371.6 2190.05  1433.7 2194.29  1505.8 2196.07
#Mann= 7 ,-1,0
       0      .1       0     330    .025       0   460.6    .035       0
   660.9      .1       0     760     .05       0    1200     .06       0
    1420     .05       0
#XS Ineff= 2 , 0
                         1221.51         2192.82
Permanent Ineff=
       F       F
Bank Sta=460.6,660.9
XS Rating Curve= 0 ,0
Exp/Cntr(USF)=0,0
Exp/Cntr=0.3,0.1

Type RM Length L Ch R = 1 ,130595  ,493.1,492.8,492.6
XS GIS Cut Line= 3
     2235417.329      448597.9262235709.64338889 449306.76402774
2236095.90094574449895.713864347
#Sta/Elev= 30
       0 2400.51    42.5 2370.51   111.7 2317.21   151.7 2290.09   194.6 2258.24
   219.1 2236.31   254.5 2207.23   271.2    2191   293.4 2172.12   297.7 2166.95
   310.7 2141.99   332.4 2139.95   338.6 2137.37   346.8 2131.22   350.8 2128.69
   358.3 2127.34     566 2127.34   570.3  2127.6   577.5 2131.49   587.6 2135.72
   609.3 2140.68   623.5  2141.2   848.3 2137.96   860.5  2136.5  1121.5 2144.03
  1166.1  2146.3  1296.1 2157.14  1319.2 2156.99  1458.5 2169.44  1471.1 2168.43
#Mann= 8 ,-1,0
       0      .1       0     260    .025       0   346.8    .035       0
   577.5    .025       0     580      .1       0     680     .05       0
 1256.75     .06       0 1376.75     .05       0
Bank Sta=346.8,577.5
XS Rating Curve= 0 ,0
Exp/Cntr=0.3,0.1

Type RM Length L Ch R = 1 ,130102  ,513.8,498.7,482.1
XS GIS Cut Line= 3
2234956.08222346 448774.788392942235383.45207466449803.964769298
2235685.80897619450245.871009994
#Sta/Elev= 30
       0 2399.36     106 2328.37   171.5 2280.48   193.2 2262.94   214.8 2244.57
   271.1    2189   289.6  2169.6     311  2143.1   314.4 2140.68   335.5 2138.85
     3522130.016   362.1 2126.72   561.3 2126.69   575.72129.542     583 2134.75
     596 2133.94   617.6 2141.17   623.1 2141.72   885.7 2137.94  1026.4 2138.76
    1300  2137.5  1328.2 2139.93    1363 2150.93  1382.4  2155.3  1491.1 2169.72
  1527.3 2177.26  1547.8 2177.48  1561.7 2180.29  1597.3 2182.58  1649.8 2181.05
#Mann= 9 ,-1,0
       0      .1       0     350    .025       0     352    .035       0
   575.7      .1       0     600     .06       0     610     .07       0
     710     .05       0 1494.38     .06       0 1644.38     .05       0
Bank Sta=352,575.7
XS Rating Curve= 0 ,0
Exp/Cntr(USF)=0,0
Exp/Cntr=0.3,0.1

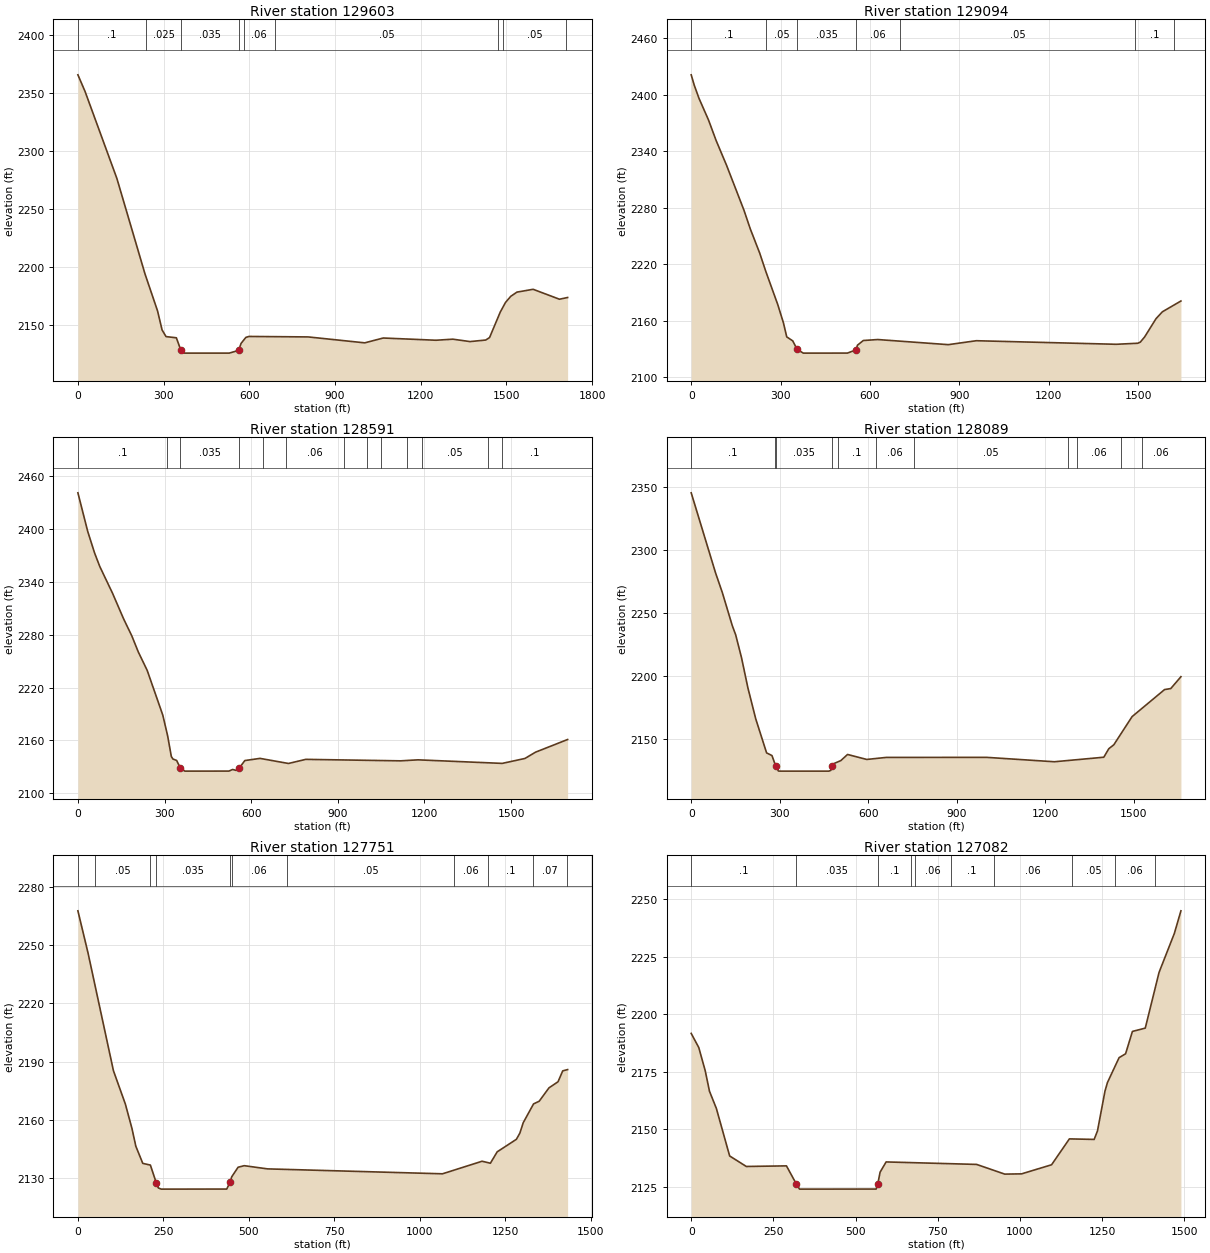
Type RM Length L Ch R = 1 ,129603  ,524.8,508.7,491.9
XS GIS Cut Line= 2
     2234457.944      449021.1882235308.15172765450510.034832219
#Sta/Elev= 30
       0 2365.53    25.1 2351.18   136.5 2276.34   234.9 2194.23   278.8 2162.43
   294.8 2145.95   308.6 2140.28   344.7 2139.26359.59852129.144   373.1 2126.06
   529.7 2126.07562.91772128.442   571.2  2134.4     588 2139.59   598.8 2140.41
   806.1    2140  1004.2 2134.91  1068.9 2139.06  1253.6 2137.15  1312.8 2138.06
  1372.7 2135.99  1427.9 2137.33  1441.2 2139.45  1478.6 2161.34    1497 2169.66
  1515.4 2174.93  1537.1 2178.56  1593.8 2180.98  1685.9 2172.44  1714.5 2173.93
#Mann= 9 ,-1,0
       0      .1       0     240    .025       0359.5985    .035       0
562.9177      .1       0     580     .06       0     690     .05       0
    1470      .1       0    1490     .05       0    1710     .06       0
Bank Sta=359.5985,562.9177
XS Rating Curve= 0 ,0
Exp/Cntr=0.3,0.1

Type RM Length L Ch R = 1 ,129094  ,518.5,503.3,487.7
XS GIS Cut Line= 2
     2233976.226      449327.0682234979.08835519450629.375011813
#Sta/Elev= 30
       0 2420.93      10 2410.11    26.1 2395.99    58.5 2372.69    83.4 2351.39
   118.8  2324.8   176.9 2277.41   198.3 2257.43   229.4 2232.17     250 2212.63
   290.4  2177.2   309.5 2157.78   320.7 2142.81   340.9 2138.56   355.1  2129.7
   376.3 2125.59   524.4 2125.64     553 2129.06     558 2133.99   577.6 2138.97
   626.1 2140.01   862.8 2134.58   956.8 2138.75  1426.4 2134.97  1498.9 2136.08
  1507.4 2137.29  1521.7 2142.69  1560.2  2162.2  1581.6 2169.49  1643.7  2180.9
#Mann= 7 ,-1,0
       0      .1       0     250     .05       0   355.1    .035       0
     553     .06       0     700     .05       0    1490      .1       0
    1620     .05       0
Bank Sta=355.1,553
XS Rating Curve= 0 ,0
Exp/Cntr=0.3,0.1

Type RM Length L Ch R = 1 ,128591  ,518.2,502.6,490.2
XS GIS Cut Line= 2
     2233558.671      449701.1062234756.68178508450901.509125836
#Sta/Elev= 30
       0  2441.4      34 2397.58    57.7 2373.13    75.7 2357.75   119.9 2327.34
   158.3 2298.18   186.6 2278.94   209.2 2260.59     240 2239.64     294  2188.8
   310.9 2165.11   323.6 2141.72   329.2 2138.93   341.9 2137.33   354.7 2128.81
   370.2 2125.19   523.1 2125.24   535.7 2127.06   548.3 2126.01   559.6 2129.05
   578.1  2137.2   630.7 2139.66   729.1 2133.89   789.2 2138.56  1117.6 2136.87
  1177.7 2138.01  1469.4 2133.98    1548 2139.57    1585 2146.76  1695.9 2161.12
#Mann= 13 ,-1,0
       0      .1       0     310     .05       0   354.7    .035       0
   559.6     .06       0     640     .05       0     720     .06       0
     920     .05       0    1000      .1       0    1050     .05       0
    1140      .1       0    1190     .05       0    1420     .06       0
    1470      .1       0
Bank Sta=354.7,559.6
XS Rating Curve= 0 ,0
Exp/Cntr=0.3,0.1

Type RM Length L Ch R = 1 ,128089  ,344.5,337.5,335.2
XS GIS Cut Line= 4
2233328.55030448450164.2030556492233514.39854766450377.928535302
 2233663.0771422450484.7912751292234434.34735138451395.447666697
#Sta/Elev= 30
       0 2345.17    82.6  2281.7   105.3 2266.32   139.1  2240.1   150.7 2232.76
   170.5 2214.63   192.1 2190.78   218.7  2166.2   255.5 2139.24   273.7 2137.14
   286.8 2128.59   295.3  2124.9   301.2 2124.81   466.3 2124.81   473.1 2125.36
   478.7 2128.79   484.4 2130.88   507.1 2133.15   529.8    2138   595.1 2134.05
   660.4 2135.66  1001.5 2135.71  1230.8 2132.23  1398.3 2135.82  1415.3 2142.56
  1432.3 2145.68  1494.2 2167.98  1604.3 2189.39  1625.4  2190.2  1659.7 2199.58
#Mann= 11 ,-1,0
       0      .1       0  283.23     .05       0   286.8    .035       0
   478.7    .025       0  496.33      .1       0  626.33     .06       0
  756.33     .05       0 1276.33     .07       0 1306.33     .06       0
 1456.33      .1       0 1526.33     .06       0
Bank Sta=286.8,478.7
XS Rating Curve= 0 ,0
Exp/Cntr(USF)=0,0
Exp/Cntr=0.3,0.1

Type RM Length L Ch R = 1 ,127751  ,624.1,668.8,702
XS GIS Cut Line= 4
 2233189.1641221450494.083687288 2233323.9040984450661.347106148
 2233505.1061355450777.5022581332234109.11292582451576.649703795
#Sta/Elev= 30
       0 2267.66    29.7 2245.92   103.9 2185.42   138.7 2168.31     158 2155.77
   169.3 2146.63   189.7 2137.77   211.9  2136.9   229.3 2127.68   235.1 2125.17
   243.6 2124.53   435.1 2124.57   444.7 2128.02   449.7 2130.87   468.3 2135.78
   486.2 2136.59   554.5 2134.94  1065.9 2132.41  1181.7 2138.88  1205.9 2137.85
  1225.8 2143.71    1282 2150.16    1292 2153.31    1302 2158.72  1332.1 2168.36
  1348.6 2169.74  1377.2 2176.61  1403.7 2179.76  1417.4 2185.35  1431.7 2186.01
#Mann= 11 ,-1,0
       0      .1       0      50     .05       0     210    .025       0
   229.3    .035       0   444.7    .025       0  450.02     .06       0
  610.02     .05       0 1100.02     .06       0 1200.02      .1       0
 1330.02     .07       0 1430.02     .06       0
Bank Sta=229.3,444.7
XS Rating Curve= 0 ,0
Exp/Cntr(USF)=0,0
Exp/Cntr=0.3,0.1

Type RM Length L Ch R = 1 ,127082  ,459.1,487.6,510
XS GIS Cut Line= 2
     2232706.049      450868.7352233619.84510428 452045.72293357
#Sta/Elev= 30
       0 2191.72      23 2185.59    42.6 2175.53    55.6 2166.61    76.5 2159.15
     117 2138.49   167.7 2133.93   289.8 2134.19  319.12 2126.53   329.6 2124.09
   562.7 2124.12   567.7 2126.35   574.8 2131.48   593.1  2135.9   868.5 2134.82
     954 2130.61  1005.3 2130.72  1096.5 2134.67  1150.7 2145.91  1226.1 2145.68
  1236.2 2149.37    1259 2166.65  1266.6 2170.41    1302  2181.2  1321.7 2182.87
  1342.5 2192.58  1381.6 2194.02  1423.6 2218.24    1470 2235.11  1490.1 2244.96
#Mann= 10 ,-1,0
       0      .1       0  319.12    .035       0   567.7      .1       0
     670     .07       0     680     .06       0     790      .1       0
     920     .06       0    1160     .05       0    1290     .06       0
    1410      .1       0
Bank Sta=319.12,567.7
XS Rating Curve= 0 ,0
Exp/Cntr=0.3,0.1

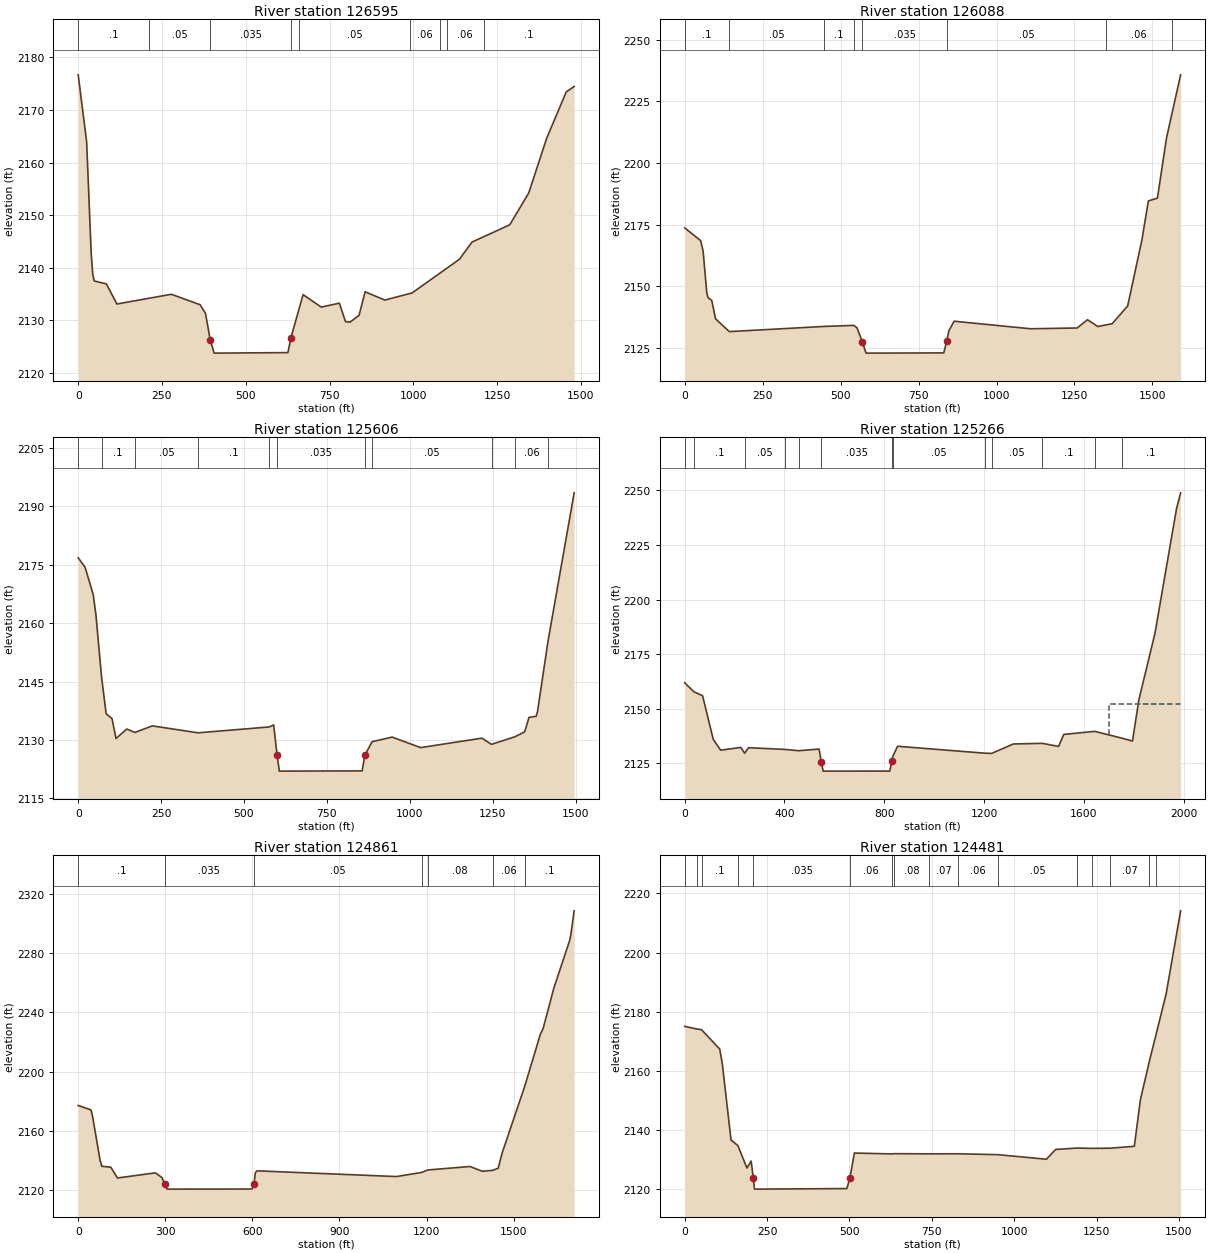
Type RM Length L Ch R = 1 ,126595  ,471.5,506.3,534.3
XS GIS Cut Line= 2
 2232323.7562962451010.8688650042233011.11330881452321.667430106
#Sta/Elev= 30
       0  2176.7    25.2 2163.92    38.7 2142.82    43.3 2138.81    47.8  2137.5
    83.9 2136.95   115.5 2133.12   278.1 2134.97   363.9 2132.98   379.9 2131.33
   393.8 2126.36   405.7 2123.78   625.9 2123.88   634.9 2126.71   671.1  2134.9
   725.3 2132.53   779.5 2133.28   797.5 2129.78   811.1 2129.66   838.2 2130.97
   856.2 2135.45     915 2133.87   996.3 2135.22  1137.8 2141.63  1175.3  2144.9
  1287.9 2148.18  1344.6 2154.24  1398.2 2164.65  1456.5 2173.45  1480.1 2174.48
#Mann= 9 ,-1,0
       0      .1       0     210     .05       0   393.8    .035       0
   634.9    .025       0     660     .05       0     990     .06       0
    1080     .07       0    1100     .06       0    1210      .1       0
Bank Sta=393.8,634.9
XS Rating Curve= 0 ,0
Exp/Cntr=0.3,0.1

Type RM Length L Ch R = 1 ,126088  ,373.5,482.2,574.4
BEGIN DESCRIPTION:
channel burned 0.60' to transition from approximate to detailed reach:
lidar = 2123.47
interpolated = 2122.87
END DESCRIPTION:
XS GIS Cut Line= 3
2232031.93290826450958.2327549072232046.30848052451469.665259785
2232336.11109374452508.825851578
#Sta/Elev= 30
       0  2173.7      51 2168.57      59 2164.39      71 2147.29      75  2145.4
      87  2144.2      99 2136.78   143.2  2131.6   447.1  2133.7     542 2134.13
   552.7 2133.14   569.3 2127.55   581.7 2122.87   830.9 2122.96   840.7 2127.95
   847.5 2132.03   864.1 2135.82  1109.1 2132.76  1258.6 2133.07  1291.8 2136.42
    1325 2133.66  1352.4 2134.37  1370.7 2134.78  1420.6 2142.01  1466.2 2168.77
    1487 2184.62  1516.1 2185.78  1545.1 2210.12  1561.7 2219.56  1590.4 2235.81
#Mann= 8 ,-1,0
       0      .1       0   143.2     .05       0   447.1      .1       0
     542    .025       0   569.3    .035       0   840.7     .05       0
  1352.4     .06       0  1561.7      .1       0
Bank Sta=569.3,840.7
XS Rating Curve= 0 ,0
Exp/Cntr=0.3,0.1

Type RM Length L Ch R = 1 ,125606  ,268.2,339.7,408.7
BEGIN DESCRIPTION:
channel burned 1.21' to transition from approximate to detailed reach:
lidar = 2123.47
interpolated = 2122.01
END DESCRIPTION:
XS GIS Cut Line= 3
 2231801.0041363450932.7224600172231715.86523674451431.719624135
2231351.11936566452351.777994766
#Sta/Elev= 30
       0 2176.74    20.8 2174.32    45.1 2167.36    53.2 2162.35    70.4 2146.16
    84.3 2136.71   101.9 2135.51   114.1 2130.38   146.5 2132.81   170.9 2131.94
   223.6 2133.62   361.6 2131.84   576.6 2133.35   589.5 2133.88  599.91 2126.13
   606.7 2122.01   856.3 2122.07   864.9 2126.13   886.4 2129.55   946.7 2130.75
  1032.7 2128.04  1217.8 2130.47  1246.6 2128.88  1316.7 2130.81  1346.8  2132.1
  1359.7  2135.8  1381.3 2136.08  1385.6 2137.38  1417.1 2155.37  1495.9 2193.43
#Mann= 11 ,-1,0
       0     .05       0    70.4      .1       0   170.9     .05       0
   361.6      .1       0   576.6    .025       0  599.91    .035       0
   864.9      .1       0   886.4     .05       0  1246.6     .08       0
  1316.7     .06       0  1417.1      .1       0
Bank Sta=599.91,864.9
XS Rating Curve= 0 ,0
Exp/Cntr=0.3,0.1

Type RM Length L Ch R = 1 ,125266  ,394.9,405.3,413.8
BEGIN DESCRIPTION:
channel burned 1.63' to transition from approximate to detailed reach:
lidar = 2123.03
interpolated = 2121.40
END DESCRIPTION:
XS GIS Cut Line= 4
2231683.14945968450874.0700363652231522.16932687451299.009423998
2231009.21235665451773.211307584 2230232.7250924452081.005650681
#Sta/Elev= 30
       0 2161.87    37.5 2157.69    71.8 2155.96   114.5 2135.93   144.3 2130.99
     225 2132.25   240.5  2129.6     256 2132.12   401.1 2131.35   457.4 2130.75
   538.8  2131.5   547.9 2125.45   555.2  2121.4   822.1 2121.42     831 2126.01
   834.7 2128.27   853.6 2132.79  1204.8  2129.6  1230.8 2129.52  1317.6 2133.83
  1433.8 2134.12  1498.9 2132.71  1519.8 2138.21  1643.7 2139.61  1751.5 2136.54
  1795.2 2135.18    1821 2154.11  1885.6 2184.64  1971.6 2241.51  1988.2 2248.86
#Mann= 13 ,-1,0
       0     .06       0    37.5      .1       0   240.5     .05       0
   401.1      .1       0   457.4    .025       0   547.9    .035       0
     831      .1       0   834.7     .05       0  1204.8      .1       0
  1230.8     .05       0  1433.8      .1       0  1643.7     .08       0
  1751.5      .1       0
#XS Ineff= 2 , 0
                            1702         2152.15
Permanent Ineff=
       F       F
Bank Sta=547.9,831
XS Rating Curve= 0 ,0
Exp/Cntr=0.3,0.1

Type RM Length L Ch R = 1 ,124861  ,357,380.2,422.1
BEGIN DESCRIPTION:
channel burned 2.07' to transition from approximate to detailed reach:
lidar = 2122.75
interpolated = 2120.68
END DESCRIPTION:
XS GIS Cut Line= 3
2231479.12287281450838.2098702922230438.09034469451674.409609313
2230110.35788214451852.734625704
#Sta/Elev= 30
       0 2177.12      44 2174.15    49.5 2169.75    75.3 2140.19    81.4 2136.07
   112.3 2135.47   135.1 2128.16     266 2131.64   288.7 2128.38   297.3 2124.29
  306.42 2120.64   598.9 2120.71   605.2 2124.18   610.2 2131.67   615.9    2133
  1096.6 2129.12  1183.8 2131.95  1204.3 2133.58  1349.4 2135.93  1392.1 2132.69
  1427.2 2133.31  1446.8 2134.74  1460.4 2145.07  1537.8 2189.87  1592.5 2225.56
  1601.6 2229.12    1638 2256.09  1692.7 2288.48  1697.2 2292.64  1708.4 2308.62
#Mann= 7 ,-1,0
       0      .1       0   297.3    .035       0   605.2     .05       0
  1183.8     .03       0  1204.3     .08       0  1427.2     .06       0
  1537.8      .1       0
Bank Sta=297.3,605.2
XS Rating Curve= 0 ,0
Exp/Cntr(USF)=0,0
Exp/Cntr=0.3,0.1

Type RM Length L Ch R = 1 ,124481  ,493.9,497.3,513.4
BEGIN DESCRIPTION:
channel burned 1.93' to transition from approximate to detailed reach:
lidar = 2121.93
interpolated = 2120.0
END DESCRIPTION:
XS GIS Cut Line= 2
2231288.74886883450590.000725857 2229977.8190186451329.808564126
#Sta/Elev= 30
       0 2175.03      38 2174.12    51.2 2173.91   106.3 2167.37   114.3 2162.34
   140.7  2136.6   161.4 2134.74     189 2127.14   201.8 2129.49   208.3 2123.73
   211.9    2120   492.1 2120.19   501.3 2123.63   515.1  2132.2   628.1  2131.9
   636.2 2131.99   740.1 2131.93   830.7 2131.95   950.6 2131.65  1097.9 2130.11
  1125.9 2133.41  1191.9 2133.89  1235.9 2133.78  1291.7 2133.84  1364.8 2134.49
  1383.2 2150.22  1410.7 2163.35  1430.7 2172.24  1461.2 2185.92  1505.3  2214.1
#Mann= 16 ,-1,0
       0     .07       0      38     .06       0    51.2      .1       0
   161.4    .025       0   208.3    .035       0   501.3     .06       0
   628.1     .05       0   636.2     .08       0   740.1     .07       0
   830.7     .06       0   950.6     .05       0  1191.9      .1       0
  1235.9     .05       0  1291.7     .07       0  1410.7     .06       0
  1430.7      .1       0
Bank Sta=208.3,501.3
XS Rating Curve= 0 ,0
Exp/Cntr(USF)=0,0
Exp/Cntr=0.3,0.1

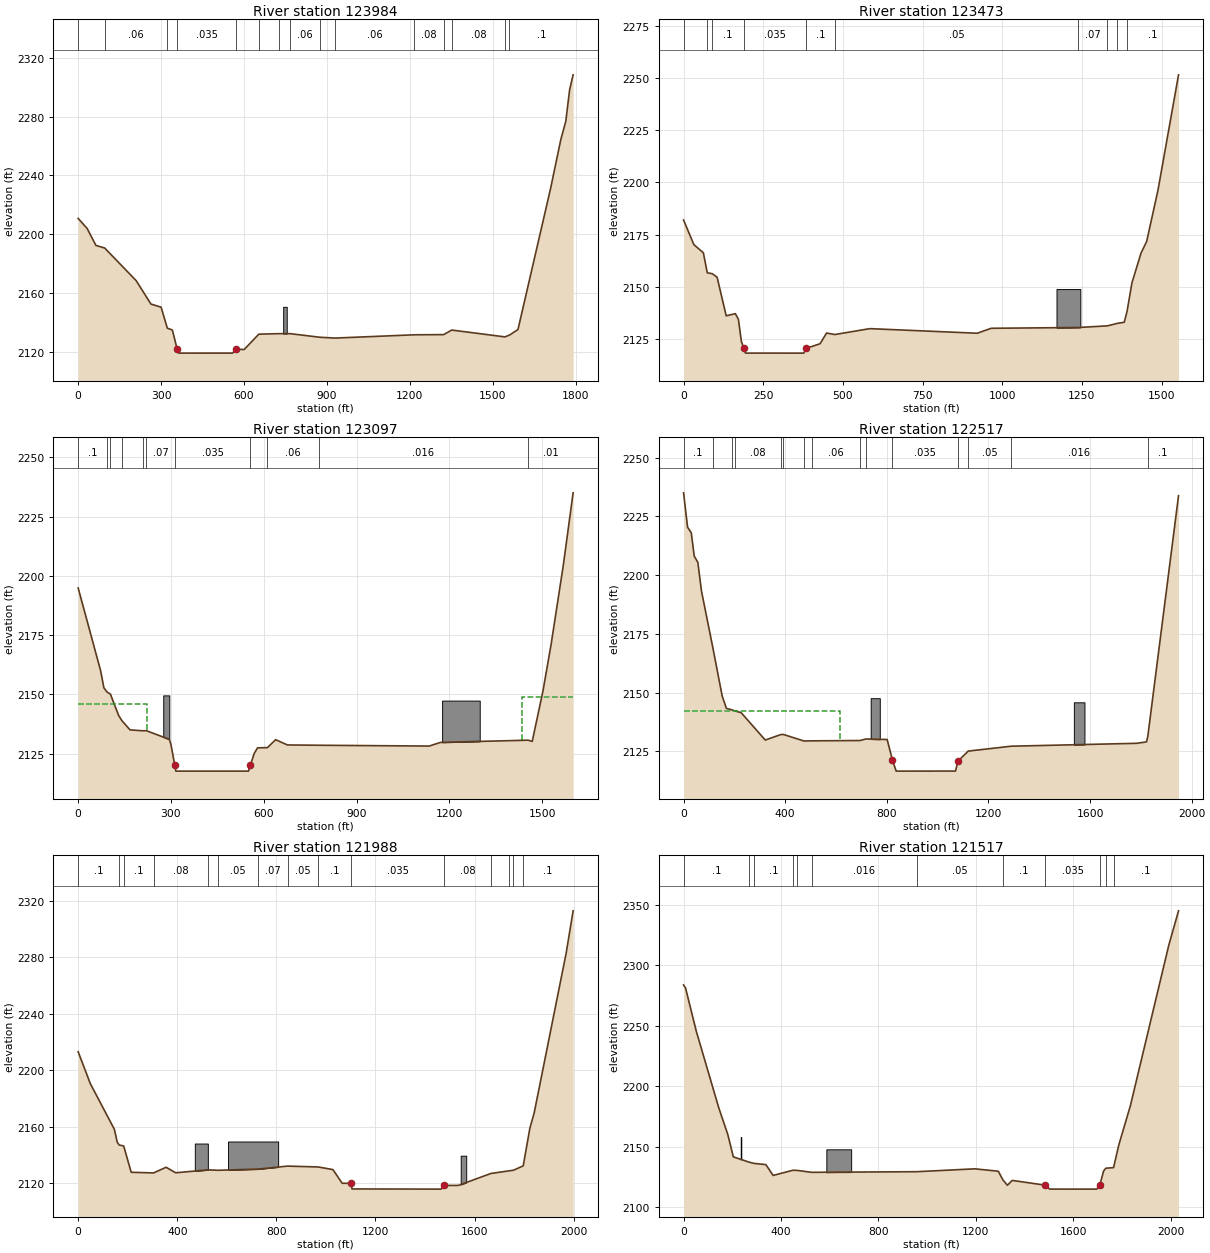
Type RM Length L Ch R = 1 ,123984  ,519.8,510.3,496.2
BEGIN DESCRIPTION:
channel burned 1.75' to transition from approximate to detailed reach:
lidar = 2120.86
interpolated = 2119.11
END DESCRIPTION:
XS GIS Cut Line= 2
2231228.88083474450069.6177563162229648.91719895450911.758855112
#Sta/Elev= 30
       0 2210.76    32.5  2203.9    64.3 2192.36      96 2190.61   210.1 2168.35
   263.3 2152.48     300 2150.39   322.6 2136.08   340.8 2134.83  357.71 2122.07
   363.4 2119.11     559 2119.13  570.28 2121.77   600.4 2121.57   653.5    2132
     726 2132.36     766 2132.38   875.4 2129.88     930 2129.36  1216.1 2131.58
  1321.9  2131.7  1351.4 2134.81  1543.6 2130.16  1560.1 2131.38  1590.9 2135.18
  1708.4 2230.75  1745.9 2264.42    1764 2276.97  1777.6 2298.16  1790.4 2308.43
#Mann= 15 ,-1,0
       0      .1       0      96     .06       0   322.6    .025       0
  357.71    .035       0  570.28    .025       0   653.5     .06       0
     726     .07       0     766     .06       0   875.4     .05       0
     930     .06       0  1216.1     .08       0  1321.9     .07       0
  1351.4     .08       0  1543.6     .07       0  1560.1      .1       0
#Block Obstruct= 1 ,-1
  741.59  754.41 2150.63
Bank Sta=357.71,570.28
XS Rating Curve= 0 ,0
Exp/Cntr=0.3,0.1

Type RM Length L Ch R = 1 ,123473  ,397.2,376.2,401.6
BEGIN DESCRIPTION:
start GRL detailed reach - channel burned 2.08':
lidar invert = 2120.28
effective invert = 2118.20
END DESCRIPTION:
XS GIS Cut Line= 3
2230836.33611434449672.6223597132230247.38332597450055.629840518
2229473.14840302450407.758978043
#Sta/Elev= 30
       0 2181.96    32.3 2170.19    62.2 2166.25    74.4 2156.68    90.1 2156.24
   105.2 2154.57   133.8 2136.07   162.4 2137.12     172 2134.45   181.5 2123.76
  189.33 2120.44   194.2 2118.22   377.1  2118.2  384.33 2120.46   428.4  2122.7
   448.7 2127.82   474.7 2127.11   584.5 2129.93   921.4 2127.73   965.3  2130.1
  1237.7 2130.47    1330 2131.27  1360.8 2132.44  1382.8    2133  1391.6 2138.24
  1406.9 2151.88  1435.5 2166.16  1453.1 2171.69  1488.9 2196.51  1553.1 2251.52
#Mann= 10 ,-1,0
       0      .1       0    74.4    .016       0    90.1      .1       0
  189.33    .035       0  384.33      .1       0   474.7     .05       0
  1237.7     .07       0    1330     .06       0  1360.8    .016       0
  1391.6      .1       0
#Block Obstruct= 1 ,-1
 1170.13 1244.98 2148.89
Bank Sta=189.33,384.33
XS Rating Curve= 0 ,0
Exp/Cntr(USF)=0,0
Exp/Cntr=0.3,0.1

Type RM Length L Ch R = 1 ,123097  ,708,580.1,320.7
BEGIN DESCRIPTION:
channel burned 2.29':
lidar invert = 2119.88
interpolated invert = 2117.59
END DESCRIPTION:
Node Name=T
XS GIS Cut Line= 3
     2230711.076      449232.9692230224.07711222  449654.0219267
2229342.18120445450024.676156277
#Sta/Elev= 30
       0 2194.91    72.6 2159.98    83.2 2152.75    93.7 2150.92   104.4 2150.08
   130.7 2141.14   141.3 2138.92   167.8 2134.99   210.1 2134.61   220.6 2134.66
   294.7    2131     300 2128.87  312.55 2119.99   315.8 2117.59   550.8 2117.59
  556.57 2120.04   569.6 2125.17   580.2 2127.42   611.9  2127.5   638.4 2130.86
   676.7 2128.64   777.5 2128.51  1134.9 2128.17  1171.6 2129.72  1455.1 2130.65
  1468.1 2130.14  1502.8 2151.36    1529 2170.93  1567.9 2203.83  1600.4 2235.05
#Mann= 11 ,-1,0
       0      .1       0    93.7    .016       0   104.4     .08       0
   141.3     .06       0   210.1    .016       0   220.6     .07       0
  312.55    .035       0  556.57      .1       0   611.9     .06       0
   777.5    .016       0  1455.1     .01       0
#XS Ineff= 2 , 0
          221.07  2145.9 1435.22         2148.83
Permanent Ineff=
       F       F
#Block Obstruct= 2 ,-1
  275.08  294.66 2149.56 1176.78 1298.36 2147.36
Bank Sta=312.55,556.57
XS Rating Curve= 0 ,0
Exp/Cntr=0.3,0.1

Type RM Length L Ch R = 1 ,122517  ,478.8,529.1,460.3
BEGIN DESCRIPTION:
channel burned 2.38':
lidar invert = 2119.03
interpolated invert = 2116.65
END DESCRIPTION:
XS GIS Cut Line= 4
2230551.67080971448426.8513351752230209.38546449448643.971145313
2229746.59856102449477.7221539492229270.25862493449824.632715939
#Sta/Elev= 30
       0 2235.01    15.8 2220.37    30.3 2218.01      42  2208.1    56.2 2205.43
    70.5 2193.24   114.4 2169.62     152 2148.58   168.6 2143.33   189.7 2142.73
   201.3 2142.27   226.8  2141.5   321.5 2129.87   383.1 2132.21   392.7 2132.25
   473.8 2129.47   507.4 2129.53   694.9 2129.67   717.8 2130.32   801.3  2130.1
   821.9 2121.46   836.8 2116.65  1070.1 2116.68  1080.8 2120.99  1120.4 2125.17
  1289.6 2127.25  1782.5 2128.48  1822.1 2129.08  1827.1 2131.33  1948.2 2233.81
#Mann= 15 ,-1,0
       0      .1       0   114.4     .08       0   189.7    .016       0
   201.3     .08       0   383.1    .016       0   392.7      .1       0
   473.8    .016       0   507.4     .06       0   694.9    .016       0
   717.8     .06       0   821.9    .035       0  1080.8     .08       0
  1120.4     .05       0  1289.6    .016       0  1827.1      .1       0
#XS Ineff= 2 , 0
          617.46 2142.39
Permanent Ineff=
       F       F
#Block Obstruct= 2 ,-1
  736.51   772.3 2147.67  1536.1 1577.96 2145.92
Bank Sta=821.9,1080.8
XS Rating Curve= 0 ,0
Exp/Cntr=0.3,0.1

Type RM Length L Ch R = 1 ,121988  ,298.1,470.5,574.8
BEGIN DESCRIPTION:
channel burned 2.04':
lidar invert = 2117.84
effective invert = 2115.80
END DESCRIPTION:
XS GIS Cut Line= 5
2230360.64513631448074.2694426242229596.68277897448599.372905041
2229464.89517095448885.5994126882229265.14579271449334.498237478
2229026.27587978449447.750621024
#Sta/Elev= 30
       0 2213.05    49.1 2190.48   146.2 2158.13   157.8 2148.98   165.6 2147.03
   183.7 2146.35   214.1 2127.74   304.5 2127.26   354.9 2131.28   393.6 2127.38
   524.8 2129.45   563.6 2129.13   727.3    2130   845.1  2132.1   968.6  2131.5
  1028.3 2129.64  1065.5 2119.97  1100.8 2119.87  1105.2 2115.93    1465  2115.8
  1478.1 2118.39    1535 2118.45  1665.8 2126.88  1739.7 2128.76  1756.7 2129.16
  1796.3 2132.27  1823.1 2158.85  1840.8 2169.98  1969.2 2282.45  1997.8 2312.84
#Mann= 15 ,-1,0
       0      .1       0   165.6    .016       0   183.7      .1       0
   304.5     .08       0   524.8    .016       0   563.6     .05       0
   727.3     .07       0   845.1     .05       0   968.6      .1       0
  1100.8    .035       0  1478.1     .08       0  1665.8    .016       0
  1739.7     .05       0  1756.7    .016       0  1796.3      .1       0
#Block Obstruct= 3 ,-1
  470.72  523.36 2148.09  604.99  807.19 2149.53 1544.04 1566.32 2139.48
Bank Sta=1100.8,1478.1
XS Rating Curve= 0 ,0
Exp/Cntr(USF)=0,0
Exp/Cntr=0.3,0.1

Type RM Length L Ch R = 1 ,121517  ,485.6,488.3,492.1
BEGIN DESCRIPTION:
channel burned 1.12':
lidar invert = 2116.04
interpolated invert = 2114.92
END DESCRIPTION:
XS GIS Cut Line= 2
2230284.62765637447685.9612300112228712.42605681448974.379849421
#Sta/Elev= 30
       0  2283.8     8.3  2281.2    52.3 2245.51   144.7 2182.11   181.8 2160.01
   204.4 2141.62   269.5 2137.22   289.7  2136.2     338  2135.2   367.8 2126.25
   448.9 2130.53   465.8 2130.43   525.6 2128.82   957.3 2129.34  1196.4 2131.71
  1292.5 2129.74  1311.4 2122.59  1329.7 2118.13  1349.9 2122.13  1486.3 2118.17
  1503.3 2114.94  1696.6 2114.92    1709 2117.97    1725 2129.92  1734.2 2132.22
  1765.8 2132.72  1787.6  2151.6  1835.2 2184.12  1992.9 2316.91  2032.7 2345.16
#Mann= 12 ,-1,0
       0      .1       0   269.5    .016       0   289.7      .1       0
   448.9    .016       0   465.8     .07       0   525.6    .016       0
   957.3     .05       0  1311.4      .1       0  1486.3    .035       0
    1709     .06       0  1734.2    .016       0  1765.8      .1       0
#Block Obstruct= 2 ,-1
  234.76  237.07 2157.94  586.34  688.25 2147.86
Bank Sta=1486.3,1709
XS Rating Curve= 0 ,0
Exp/Cntr=0.3,0.1