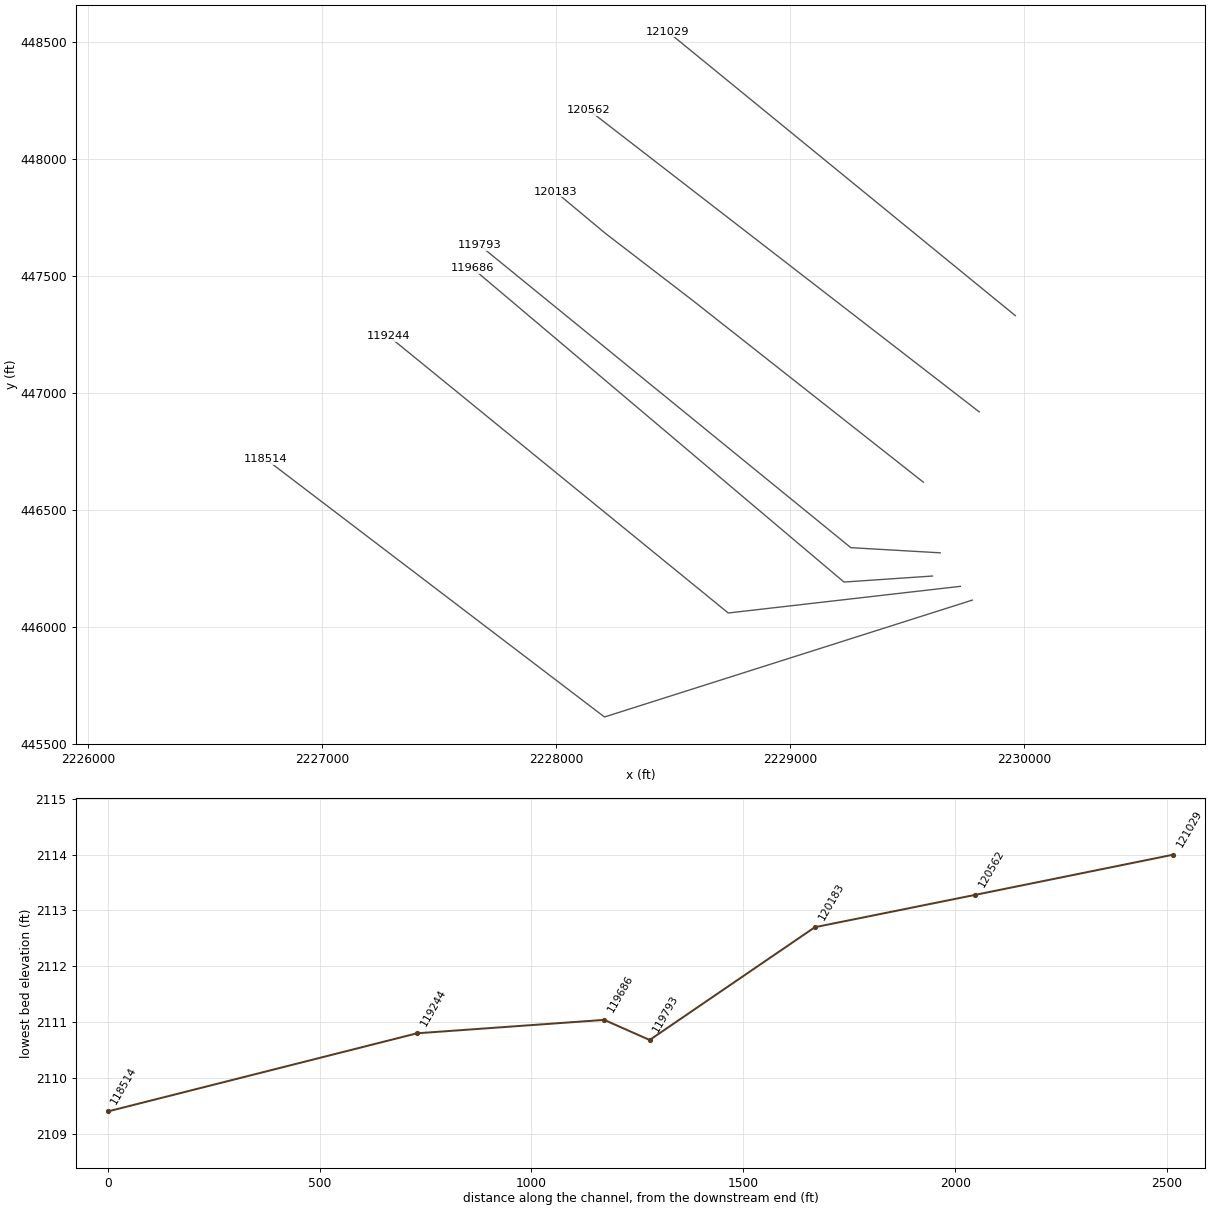
HEC-RAS study GRNBRRRV.prj: GRNBRRRV

--- GRNBRRRV.g01 (geometry) --- (continued)

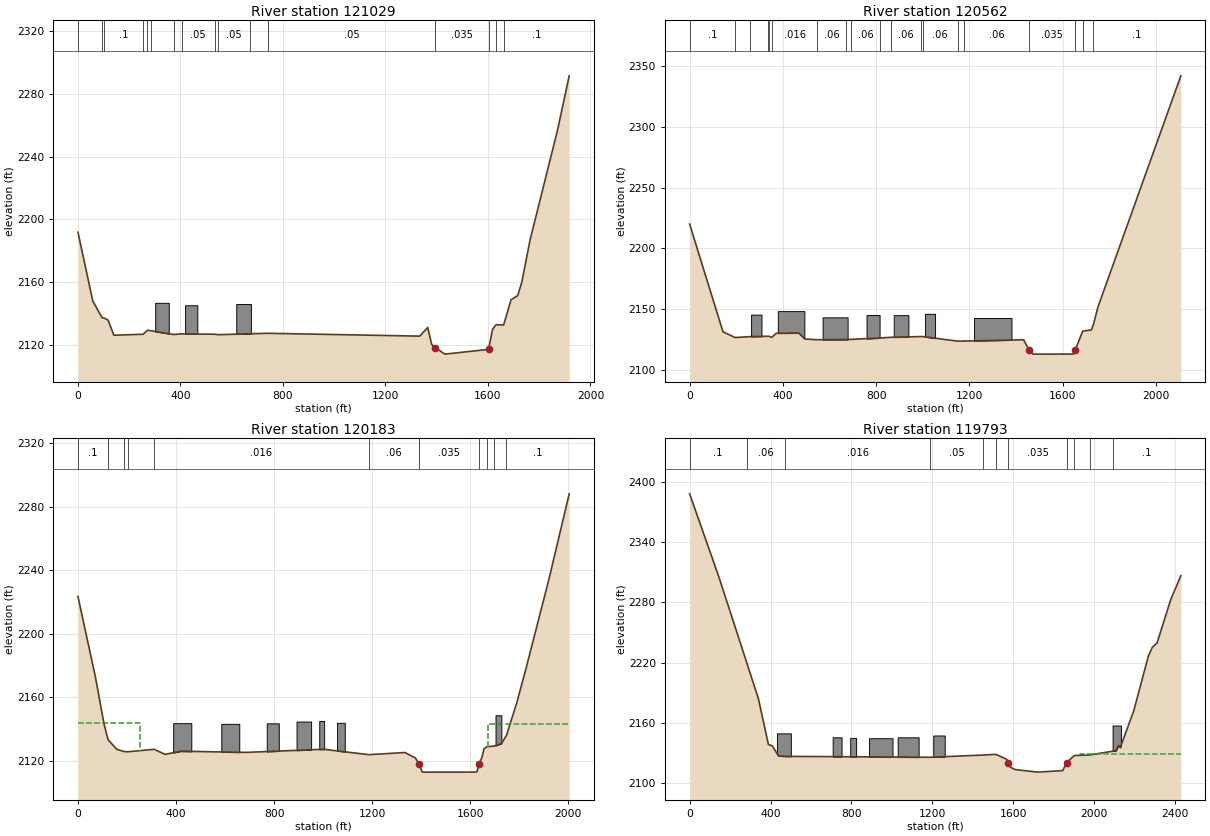
Type RM Length L Ch R = 1 ,121029  ,440,467.3,469.2
BEGIN DESCRIPTION:
channel burned 1.61':
lidar invert = 2115.61
effective invert = 2114.0
END DESCRIPTION:
Node Name=S
XS GIS Cut Line= 2
2229961.13089064447328.8140883862228476.45907868448541.725936561
#Sta/Elev= 30
       0 2191.79    57.8  2147.9    94.2 2137.21   101.7 2137.12   117.5 2135.68
   140.2 2126.05   254.3 2126.69     271  2129.2   285.2 2128.91   373.3  2126.5
   404.1 2126.92   533.2  2126.7   546.7  2126.4   670.8 2126.99   739.8  2127.3
  1333.8 2125.48  1364.8 2131.02  1380.3 2120.29  1393.9 2118.13    1432    2114
  1602.4 2117.03  1617.9 2129.73  1631.8 2132.79  1661.1 2132.59  1690.2 2148.69
  1716.1 2151.32  1732.2 2159.96  1764.5 2186.92  1871.5 2256.89  1917.1 2291.57
#Mann= 16 ,-1,0
       0      .1       0    94.2    .016       0   101.7      .1       0
   254.3     .08       0     271    .016       0   285.2     .05       0
   373.3    .016       0   404.1     .05       0   533.2    .016       0
   546.7     .05       0   670.8    .016       0   739.8     .05       0
  1393.9    .035       0  1602.4     .07       0  1631.8    .016       0
  1661.1      .1       0
#Block Obstruct= 3 ,-1
  301.34   354.3 2146.74  418.04  465.71 2145.18  617.64  674.92 2145.98
Bank Sta=1393.9,1602.4
XS Rating Curve= 0 ,0
Exp/Cntr(USF)=0,0
Exp/Cntr=0.3,0.1

Type RM Length L Ch R = 1 ,120562  ,378.3,379,373.7
BEGIN DESCRIPTION:
channel burned 1.89':
lidar invert = 2115.17
interpolated invert = 2113.28
END DESCRIPTION:
XS GIS Cut Line= 2
2229806.70213926446917.6708005822228139.20012199448206.862888825
#Sta/Elev= 30
       0 2220.06   143.1 2131.62   195.4  2126.9   260.8 2127.65   336.9 2127.97
   341.9 2127.85   352.3 2127.06   372.1 2130.46   468.4 2130.58   494.8 2125.65
   548.5  2125.1   672.8 2125.26   691.5 2125.37     817 2126.53   865.5 2127.13
   993.8 2127.71   999.5 2127.72  1150.9 2123.91  1176.3 2124.03  1176.3 2124.02
  1432.9 2125.07  1455.7 2117.04  1472.8 2113.28  1647.2 2113.32  1655.3 2117.01
  1686.7 2132.22  1723.7 2133.09  1732.4 2137.53  1752.6 2152.32  2107.7 2341.74
#Mann= 19 ,-1,0
       0      .1       0   195.4    .016       0   260.8     .05       0
   336.9    .016       0   341.9     .05       0   352.3    .016       0
   548.5     .06       0   672.8    .016       0   691.5     .06       0
     817    .016       0   865.5     .06       0   993.8    .016       0
   999.5     .06       0  1150.9    .016       0  1176.3     .06       0
  1455.7    .035       0  1655.3     .06       0  1686.7    .016       0
  1732.4      .1       0
#Block Obstruct= 7 ,-1
  263.73  308.34 2145.72  378.38   492.3 2148.58  570.65  677.87 2143.49
  759.01  815.02 2145.39  875.72  938.72 2145.26 1010.02 1053.07 2146.38
 1220.43 1380.85 2142.92
Bank Sta=1455.7,1655.3
XS Rating Curve= 0 ,0
Exp/Cntr(USF)=0,0
Exp/Cntr=0.3,0.1

Type RM Length L Ch R = 1 ,120183  ,403,389.9,380.3
BEGIN DESCRIPTION:
structure xs 4 - channel burned 2.14':
lidar invert = 2114.84
effective invert = 2112.70
END DESCRIPTION:
XS GIS Cut Line= 4
2229568.08121917 446617.160021412228580.41036262 447395.28035205
2228208.14290035447681.2140299492227995.75631452447858.523945553
#Sta/Elev= 30
       0 2223.33    71.2 2172.58   106.8 2142.63   122.8 2133.16   157.7 2127.12
   187.9 2125.69   202.2  2125.5   310.3 2127.09     356 2123.88   417.4 2125.87
   686.4 2125.14  1001.9 2127.11  1186.4  2123.7  1333.3 2125.05  1375.8 2121.69
  1390.1 2118.09  1404.4 2112.71  1621.2  2112.7  1626.9 2112.88  1635.9 2117.92
  1646.8 2121.66  1656.1  2127.4  1667.6 2128.74  1698.2 2129.14  1726.8 2130.69
  1747.6 2135.84  1789.3 2156.26  1826.6  2177.6  1920.2 2233.89  2003.4 2288.04
#Mann= 11 ,-1,0
       0      .1       0   122.8     .08       0   187.9    .016       0
   202.2     .06       0   310.3    .016       0  1186.4     .06       0
  1390.1    .035       0  1635.9     .08       0  1667.6    .016       0
  1698.2     .07       0  1747.6      .1       0
#XS Ineff= 2 , 0
          253.87 2143.41 1670.42         2142.71
Permanent Ineff=
       F       F
#Block Obstruct= 7 ,-1
  388.22  462.22 2143.54  584.54  657.87 2143.13  769.83  818.99 2143.44
  891.42  950.86 2144.57  983.92 1003.96 2144.96 1056.66 1088.11 2143.78
 1702.88 1726.77 2148.55
Bank Sta=1390.1,1635.9
XS Rating Curve= 0 ,0
Exp/Cntr(USF)=0,0
Exp/Cntr=0.5,0.3

Type RM Length L Ch R = 1 ,119793  ,120.9,107.3,102.7
BEGIN DESCRIPTION:
structure xs 3
END DESCRIPTION:
XS GIS Cut Line= 3
2229640.08411498446315.3449802252229258.10127402446337.382451819
2227671.40331926447630.247451994
#Sta/Elev= 30
       0 2388.21   144.1 2305.66   282.8  2219.6   340.5 2183.67   389.5 2138.29
   409.4 2136.76   439.3 2126.87   470.9 2126.42    1190  2125.5  1453.2 2127.73
  1515.1 2128.41 1568.24  2123.4 1576.55 2120.11 1587.16 2115.51  1609.6 2113.23
 1722.55 2110.68 1845.21 2112.23 1864.11 2120.11 1902.73 2127.28  1978.1 2127.74
  2092.6 2131.56  2108.5 2132.17    2121 2137.27  2129.5 2135.16  2196.2 2171.65
  2269.3 2226.88  2288.3  2235.2  2311.5 2239.42  2379.7 2282.93  2429.3 2306.53
#Mann= 11 ,-1,0
       0      .1       0   282.8     .06       0   470.9    .016       0
    1190     .05       0  1453.2    .016       0  1515.1     .05       0
 1576.55    .035       0 1864.11     .08       0 1902.73      .1       0
  1978.1    .016       0  2092.6      .1       0
#XS Ineff= 2 , 0
          1512.2 2124.63  1930.8          2128.6
Permanent Ineff=
       F       F
#Block Obstruct= 7 ,-1
  431.67  500.53 2149.33  707.36  751.35 2145.42  794.28  823.42 2144.86
  887.17 1003.34  2144.5 1028.88 1132.46 2145.41 1204.91 1261.48 2147.23
 2091.67  2132.8 2157.17
Bank Sta=1576.55,1864.11
XS Rating Curve= 0 ,0
Exp/Cntr(USF)=0,0
Exp/Cntr=0.5,0.3

Type RM Length L Ch R = 3 ,119745  ,,,
BEGIN DESCRIPTION:
Bridge No.: 54075GRL050 8th Street
JV notes: road deck updated per surveyed XS data points
channel burned per surveyed cross sections
structure opening based on survey data, photos, and aerial imagery
surveyed inverts are 3-4' below inverts from lidar:
 surveyed invert US is 2110.71
 surveyed invert DS is 2111.04
END DESCRIPTION:
Bridge Culvert--1,0,-1,-1, 0
Deck Dist Width WeirC Skew NumUp NumDn MinLoCord MaxHiCord MaxSubmerge Is_Ogee
28,40,2.6,0, 435, 435, , , 0.98, 0, 0,0,,
   -12.4    -7.3    -3.3      .7     4.7    10.9    16.7    20.7    24.7    28.7
    32.7    36.7    40.7    44.7    52.7    56.7    60.7    64.7    68.7    72.7
    76.7    80.7    84.7    88.7    96.7   100.7   102.7   106.7   110.7   112.7
   114.7   118.8   120.7   122.8   124.7   128.7   130.8   136.7   140.7   144.7
   148.7   152.7   156.7   160.7   164.7   168.7   172.7   176.7   180.7   182.8
   184.7   188.7   192.7   194.7   198.8   200.7   204.7   206.7   210.8   212.7
   220.7   224.7   228.7   232.7   236.7   240.7   244.7   248.7   252.7   258.6
   264.7   268.7   270.9   272.7   284.7   286.6   288.7   290.9   294.6   298.6
   304.7   308.7   312.7   316.7   320.7   324.7   328.7   336.7   340.7   344.7
   346.5   348.7   352.7     355   356.7     359   363.7   364.8     369     371
   373.8   376.2   377.7     379   382.4   384.2   386.2   389.1   391.9     395
   397.6   399.8   403.3   407.5   411.8   413.8   417.5   420.1   430.9   441.3
   445.1   451.4   454.4   457.3   460.1   465.8   472.5   477.7   482.9   491.3
     497   498.4   503.6   508.8   514.1   522.6   528.3   534.8     540   545.5
   548.2   556.7   562.4   565.2   571.2   576.8   581.5   585.1   587.9   597.1
   602.3   607.5   612.7   616.3   628.3   636.2   644.8   649.1   659.5   669.8
     675   684.5   687.4   695.9   706.2   711.4   716.6   718.6     727   732.8
   737.4   739.9   744.2   752.9   763.3   772.6   775.4   778.9   785.7   792.5
   799.7   809.5   815.1   821.4   825.7   829.4   830.9   833.9     836   837.9
   843.6   851.6   857.8   860.7   866.3   872.4   877.8   882.8     888   889.1
   891.9   896.7   898.4   906.1   911.8   915.5   923.2     928   934.3   946.8
   950.3   960.7   965.9   971.9   976.3   982.8   994.2  1008.4  1012.6  1025.4
  1028.3  1033.4  1039.6  1048.2  1053.8  1059.7  1065.2  1073.7  1084.8  1087.9
  1093.6  1096.5  1100.9    1105  1113.5  1128.7  1137.3  1141.9  1144.7  1147.7
  1150.4  1153.8  1158.1  1163.3  1172.6  1181.7  1189.2  1197.7  1207.2  1210.2
  1212.9  1216.5  1221.5  1222.7  1227.1  1230.8  1235.7  1241.5  1249.9  1255.5
  1260.4  1266.6  1272.9    1284  1291.7    1298    1301  1310.5  1315.2  1329.5
  1335.6  1346.5  1360.7    1372  1376.2  1381.4  1386.6  1398.3  1404.6  1414.6
  1423.4  1428.1  1443.7  1448.5  1454.1  1464.5  1469.7  1475.2 1518.62 1541.19
 1541.19 1621.14 1637.68 1721.45  1737.5 1770.23 1821.66 1837.23 1901.63 1917.98
 1941.63 1941.63 1957.44 2007.84  2008.4  2014.1  2022.6  2030.6  2036.8  2044.2
  2051.4  2056.7    2063  2065.2    2068  2072.2  2073.7  2079.4  2085.1  2087.8
  2093.6  2096.4  2102.1  2107.8  2110.6  2116.3  2118.9  2125.7  2130.5  2133.4
  2134.5  2136.2  2141.9  2144.6  2147.6  2150.8  2156.1  2160.5  2163.4  2164.6
  2167.5  2169.6  2173.1  2176.1  2178.8  2181.7  2184.5  2186.4  2187.4  2191.6
  2194.7  2195.9  2196.8  2198.7    2201    2202  2204.4  2207.3  2210.1  2212.4
  2215.8  2217.6  2218.6  2222.8  2224.3  2227.1    2230  2232.3  2235.6  2238.6
  2241.3  2243.6  2248.8  2252.7    2254  2259.2  2261.2  2264.1  2266.9    2270
  2272.6  2276.2  2278.3  2283.9  2285.1  2286.8  2288.8  2289.6  2295.5  2298.1
  2300.7  2301.3  2307.6  2309.5  2312.4  2313.9  2316.3  2320.1  2321.5  2323.7
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                                                                         2128.13
 2128.13 2128.11 2128.11 2128.09 2128.09 2128.09 2128.08 2128.07 2128.06
    29.6    34.7    38.7    42.7    46.7    52.9    58.7    62.7    66.7    70.7
    74.7    78.7    82.7    86.7    94.7    98.7   102.7   106.7   110.7   114.7
   118.7   122.7   126.7   130.7   138.7   142.7   144.7   148.7   152.7   154.7
   156.7   160.8   162.7   164.8   166.7   170.7   172.8   178.7   182.7   186.7
   190.7   194.7   198.7   202.7   206.7   210.7   214.7   218.7   222.7   224.8
   226.7   230.7   234.7   236.7   240.8   242.7   246.7   248.7   252.8   254.7
   262.7   266.7   270.7   274.7   278.7   282.7   286.7   290.7   294.7   300.6
   306.7   310.7   312.9   314.7   326.7   328.6   330.7   332.9   336.6   340.6
   346.7   350.7   354.7   358.7   362.7   366.7   370.7   378.7   382.7   386.7
   388.5   390.7   394.7     397   398.7     401   405.7   406.8     411     413
   415.8   418.2   419.7     421   424.4   426.2   428.2   431.1   433.9     437
   439.6   441.8   445.3   449.5   453.8   455.8   459.5   462.1   472.9   483.3
   487.1   493.4   496.4   499.3   502.1   507.8   514.5   519.7   524.9   533.3
     539   540.4   545.6   550.8   556.1   564.6   570.3   576.8     582   587.5
   590.2   598.7   604.4   607.2   613.2   618.8   623.5   627.1   629.9   639.1
   644.3   649.5   654.7   658.3   670.3   678.2   686.8   691.1   701.5   711.8
     717   726.5   729.4   737.9   748.2   753.4   758.6   760.6     769   774.8
   779.4   781.9   786.2   794.9   805.3   814.6   817.4   820.9   827.7   834.5
   841.7   851.5   857.1   863.4   867.7   871.4   872.9   875.9     878   879.9
   885.6   893.6   899.8   902.7   908.3   914.4   919.8   924.8     930   931.1
   933.9   938.7   940.4   948.1   953.8   957.5   965.2     970   976.3   988.8
   992.3  1002.7  1007.9  1013.9  1018.3  1024.8  1036.2  1050.4  1054.6  1067.4
  1070.3  1075.4  1081.6  1090.2  1095.8  1101.7  1107.2  1115.7  1126.8  1129.9
  1135.6  1138.5  1142.9    1147  1155.5  1170.7  1179.3  1183.9  1186.7  1189.7
  1192.4  1195.8  1200.1  1205.3  1214.6  1223.7  1231.2  1239.7  1249.2  1252.2
  1254.9  1258.5  1263.5  1264.7  1269.1  1272.8  1277.7  1283.5  1291.9  1297.5
  1302.4  1308.6  1314.9    1326  1333.7    1340    1343  1352.5  1357.2  1371.5
  1377.6  1388.5  1402.7    1414  1418.2  1423.4  1428.6  1440.3  1446.6  1456.6
  1465.4  1470.1  1485.7  1490.5  1496.1  1506.5  1511.7  1517.2 1560.62 1583.19
 1583.19 1663.14 1679.68 1763.45  1779.5 1812.23 1863.66 1879.23 1943.63 1959.98
 1983.63 1983.63 1999.44 2049.84  2050.4  2056.1  2064.6  2072.6  2078.8  2086.2
  2093.4  2098.7    2105  2107.2    2110  2114.2  2115.7  2121.4  2127.1  2129.8
  2135.6  2138.4  2144.1  2149.8  2152.6  2158.3  2160.9  2167.7  2172.5  2175.4
  2176.5  2178.2  2183.9  2186.6  2189.6  2192.8  2198.1  2202.5  2205.4  2206.6
  2209.5  2211.6  2215.1  2218.1  2220.8  2223.7  2226.5  2228.4  2229.4  2233.6
  2236.7  2237.9  2238.8  2240.7    2243    2244  2246.4  2249.3  2252.1  2254.4
  2257.8  2259.6  2260.6  2264.8  2266.3  2269.1    2272  2274.3  2277.6  2280.6
  2283.3  2285.6  2290.8  2294.7    2296  2301.2  2303.2  2306.1  2308.9    2312
  2314.6  2318.2  2320.3  2325.9  2327.1  2328.8  2330.8  2331.6  2337.5  2340.1
  2342.7  2343.3  2349.6  2351.5  2354.4  2355.9  2358.3  2362.1  2363.5  2365.7
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                                                                         2128.13
 2128.13 2128.11 2128.11 2128.09 2128.09 2128.09 2128.08 2128.07 2128.06
Pier Skew, UpSta & Num, DnSta & Num=  ,1633.54, 2 ,1697.39, 2 , 0 , 0 , 0 ,,
     2.5     2.5
       0  2128.5
     2.5     2.5
       0  2128.5
Pier Skew, UpSta & Num, DnSta & Num=  ,1733.85, 2 ,1797.7, 2 , 0 , 0 , 0 ,,
     2.5     2.5
       0  2128.5
     2.5     2.5
       0  2128.5
Pier Skew, UpSta & Num, DnSta & Num=  ,1843.06, 2 ,1897.91, 2 , 0 , 0 , 0 ,,
     2.5     2.5
       0  2128.5
     2.5     2.5
       0  2128.5
BR Coef=-1 ,-1 , 0 ,, 0 ,,,0.8,0,1.33,0,
WSPro=,,,, 1 ,,,, 0 ,,,, 0 ,,,,-1 ,-1 ,-1 , 0 , 0 , 0 , 0 , 0
BC Design=,, 0 ,, 0 ,,,,,,
BC Use User HTab Curves=0
BC User HTab FreeFlow(D)= 0

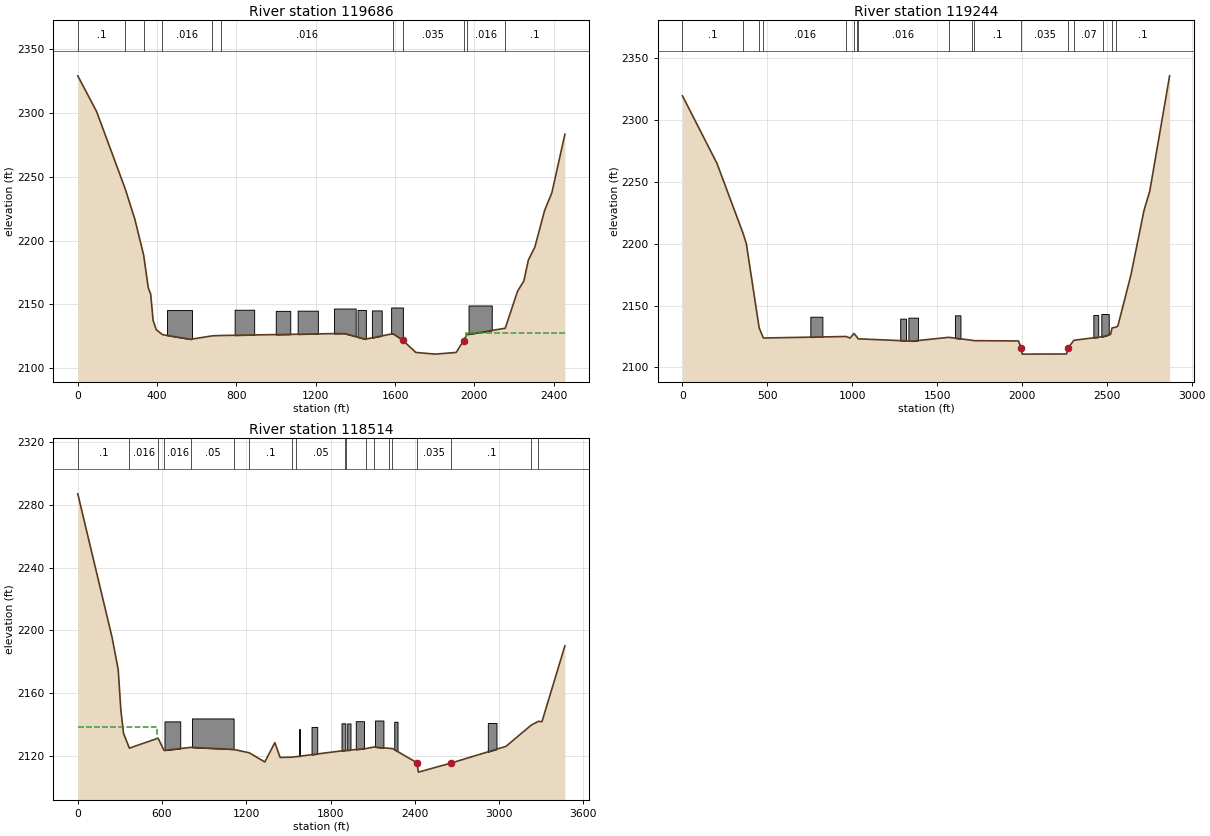
Type RM Length L Ch R = 1 ,119686  ,429.9,441.7,444.3
BEGIN DESCRIPTION:
structure xs 2
END DESCRIPTION:
XS GIS Cut Line= 3
2229607.02790759446216.1763580522229228.71797857446190.465974526
2227642.02002381447531.078829821
#Sta/Elev= 30
       0    2329    95.1    2301   239.4  2240.4   287.5 2216.86   332.1 2188.71
   355.7 2162.86   367.7 2157.96   379.9 2137.45   395.6 2130.21     427 2126.29
   569.3 2122.65   678.4 2125.37   720.3 2125.62  1343.7 2127.24  1449.4 2122.73
  1589.5 2127.05 1638.42 2121.94 1704.59 2112.37 1803.26 2111.04 1908.15 2112.38
 1945.32 2121.61  1962.52126.352  2155.5 2131.31  2217.9 2160.38  2249.4 2168.32
  2271.9 2184.64  2304.7 2194.77  2354.3 2223.71  2390.7 2237.46  2456.4 2283.24
#Mann= 11 ,-1,0
       0      .1       0   239.4     .08       0   332.1      .1       0
     427    .016       0   678.4     .05       0   720.3    .016       0
  1589.5     .08       0 1638.42    .035       0 1945.32     .08       0
  1962.5    .016       0  2155.5      .1       0
#XS Ineff= 2 , 0
          1570.8 2124.45    1956          2127.8
Permanent Ineff=
       F       F
#Block Obstruct= 9 ,-1
  449.85  576.09 2145.52  791.04   889.5  2145.8  998.36 1071.46 2144.92
 1108.74 1210.62 2145.07 1291.85 1401.34 2146.73 1410.84 1452.61 2145.67
 1483.13  1532.6 2145.26 1580.08 1639.42 2147.56 1970.49 2087.43 2149.15
Bank Sta=1638.42,1945.32
XS Rating Curve= 0 ,0
Exp/Cntr(USF)=0,0
Exp/Cntr=0.5,0.3

Type RM Length L Ch R = 1 ,119244  ,687.6,730,720.6
BEGIN DESCRIPTION:
xs 1 - channel burned = 2.78':
lidar invert = 2113.58
effective invert = 2110.80
END DESCRIPTION:
XS GIS Cut Line= 3
2229725.89807675446172.0696783222228734.21185503 446058.20940842
2227283.41164176447240.887050626
#Sta/Elev= 30
       0 2319.74   203.4 2265.06     356 2208.93   376.2 2200.32     452    2132
   476.8 2123.84     964 2125.05   988.2 2123.85  1010.3 2127.52  1027.3 2124.84
  1034.6 2123.19  1354.3 2121.31  1568.5 2124.38    1704 2122.04  1717.7 2121.69
  1979.8 2121.46 1995.052115.798    2002  2110.8  2262.7 2110.92  2270.4 2115.52
  2306.5 2122.01  2477.3 2124.97  2522.3  2126.8  2531.3    2132  2556.9 2132.75
  2565.4 2133.63  2641.9 2174.69  2719.3 2227.08  2753.1 2242.61    2870  2335.9
#Mann= 17 ,-1,0
       0      .1       0     356     .08       0     452      .1       0
   476.8    .016       0     964     .05       0  1010.3    .016       0
  1027.3     .05       0  1034.6    .016       0  1568.5     .06       0
    1704    .016       0  1717.7      .1       0 1995.05    .035       0
  2270.4      .1       0  2306.5     .07       0  2477.3     .06       0
  2531.3    .016       0  2556.9      .1       0
#Block Obstruct= 6 ,-1
  753.43  824.42 2141.05 1282.92 1316.89 2139.51 1330.97 1387.82 2140.29
 1605.29 1637.91 2142.17 2420.88 2449.49 2142.43 2467.83 2511.33 2143.29
Bank Sta=1995.05,2270.4
XS Rating Curve= 0 ,0
Exp/Cntr(USF)=0,0
Exp/Cntr=0.3,0.1

Type RM Length L Ch R = 1 ,118514  ,364.1,357.5,357.4
BEGIN DESCRIPTION:
channel burned 2.72':
lidar invert =  2112.12
effective invert = 2109.4
END DESCRIPTION:
XS GIS Cut Line= 3
2229777.31884381446113.3030874052228205.31253678 445613.78706461
2226758.18523544446715.660644305
#Sta/Elev= 30
       0 2287.08   244.6 2195.29   287.7 2174.98   306.8 2148.99   325.9 2134.14
   367.3 2124.72     572 2131.06     614 2123.29     807 2125.22  1109.4 2123.92
  1220.9 2121.74  1331.7 2115.89    1403 2128.25  1440.8 2118.78  1524.7 2118.96
  1554.1 2119.26  1902.3 2123.25  1909.6 2123.22  2052.3 2124.46  2108.4 2125.44
  2216.3 2124.59  2240.7 2124.47  2415.1 2115.36  2425.1  2109.4 2659.752115.246
  3048.3 2125.83  3229.5 2139.49  3279.4 2141.82    3305 2141.64  3468.3 2190.03
#Mann= 19 ,-1,0
       0      .1       0   367.3    .016       0     572     .05       0
     614    .016       0     807     .05       0  1109.4    .016       0
  1220.9      .1       0  1524.7    .016       0  1554.1     .05       0
  1902.3    .016       0  1909.6     .06       0  2052.3    .016       0
  2108.4     .06       0  2216.3    .016       0  2240.7     .06       0
  2415.1    .035       0 2659.75      .1       0  3229.5    .016       0
  3279.4      .1       0
#XS Ineff= 2 , 0
           565.2 2138.01
Permanent Ineff=
       F       F
#Block Obstruct= 10 ,-1
   617.3  729.54  2141.8   812.9 1109.55 2143.67  1575.4 1582.13 2136.88
 1664.42 1704.88 2138.26 1877.74  1905.1 2140.55 1918.35 1941.68 2140.49
 1979.26 2037.69 2141.93 2116.57 2176.09 2142.35 2253.42  2276.5 2141.57
 2919.44  2981.2 2140.78
Bank Sta=2415.1,2659.75
XS Rating Curve= 0 ,0
Exp/Cntr(USF)=0,0
Exp/Cntr=0.3,0.1