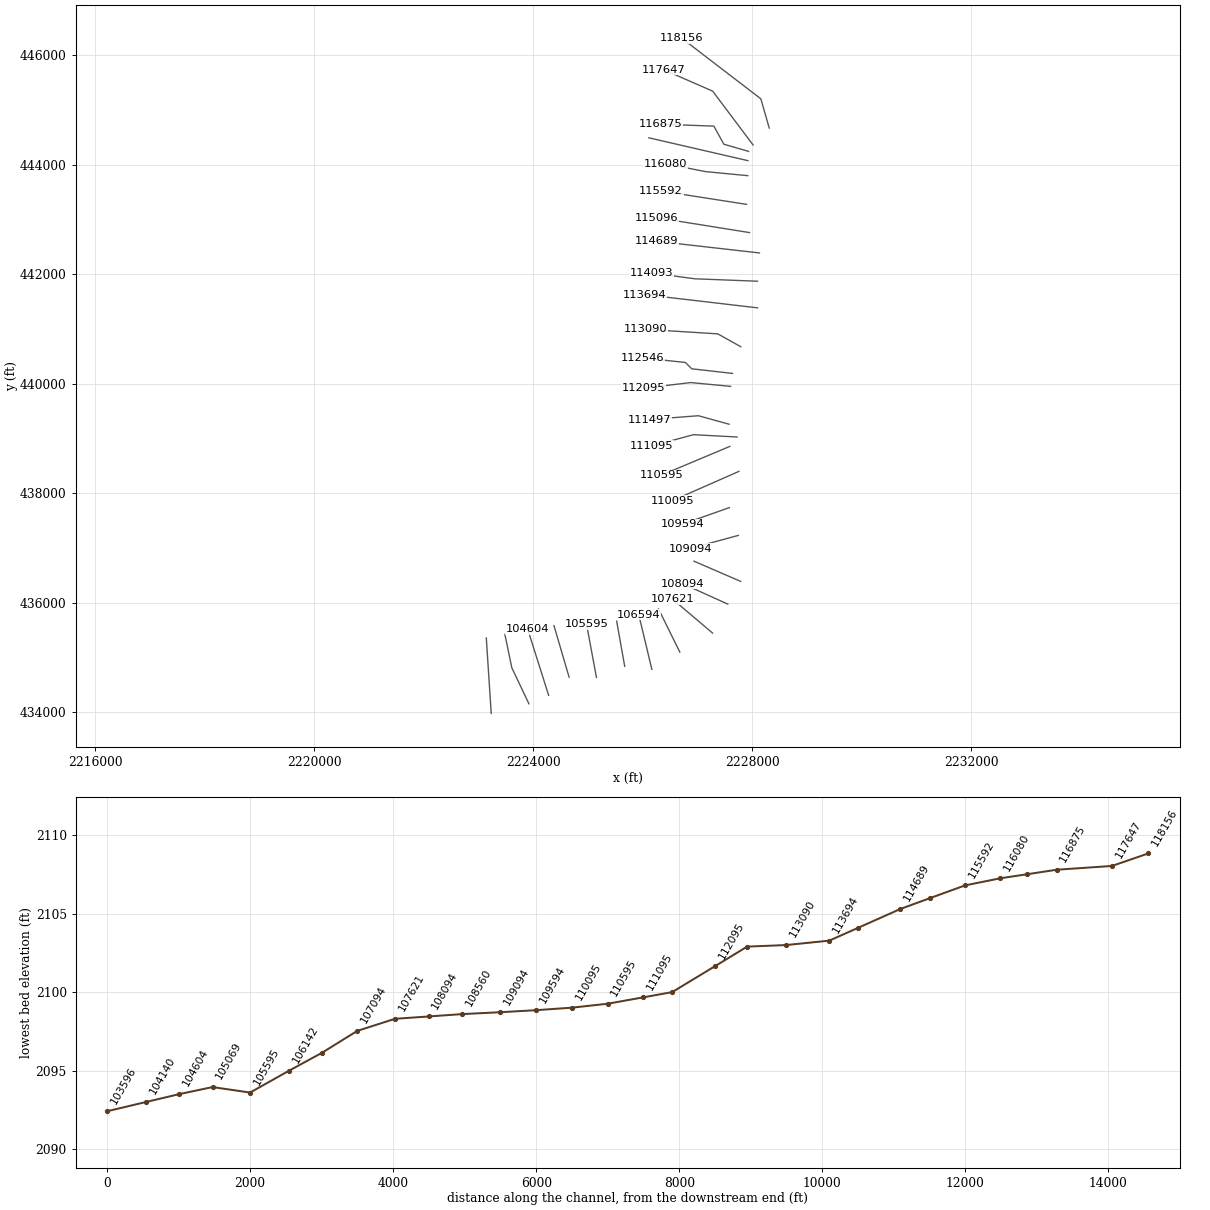
HEC-RAS study GRNBRRRV.prj: GRNBRRRV

--- GRNBRRRV.g01 (geometry) --- (continued)

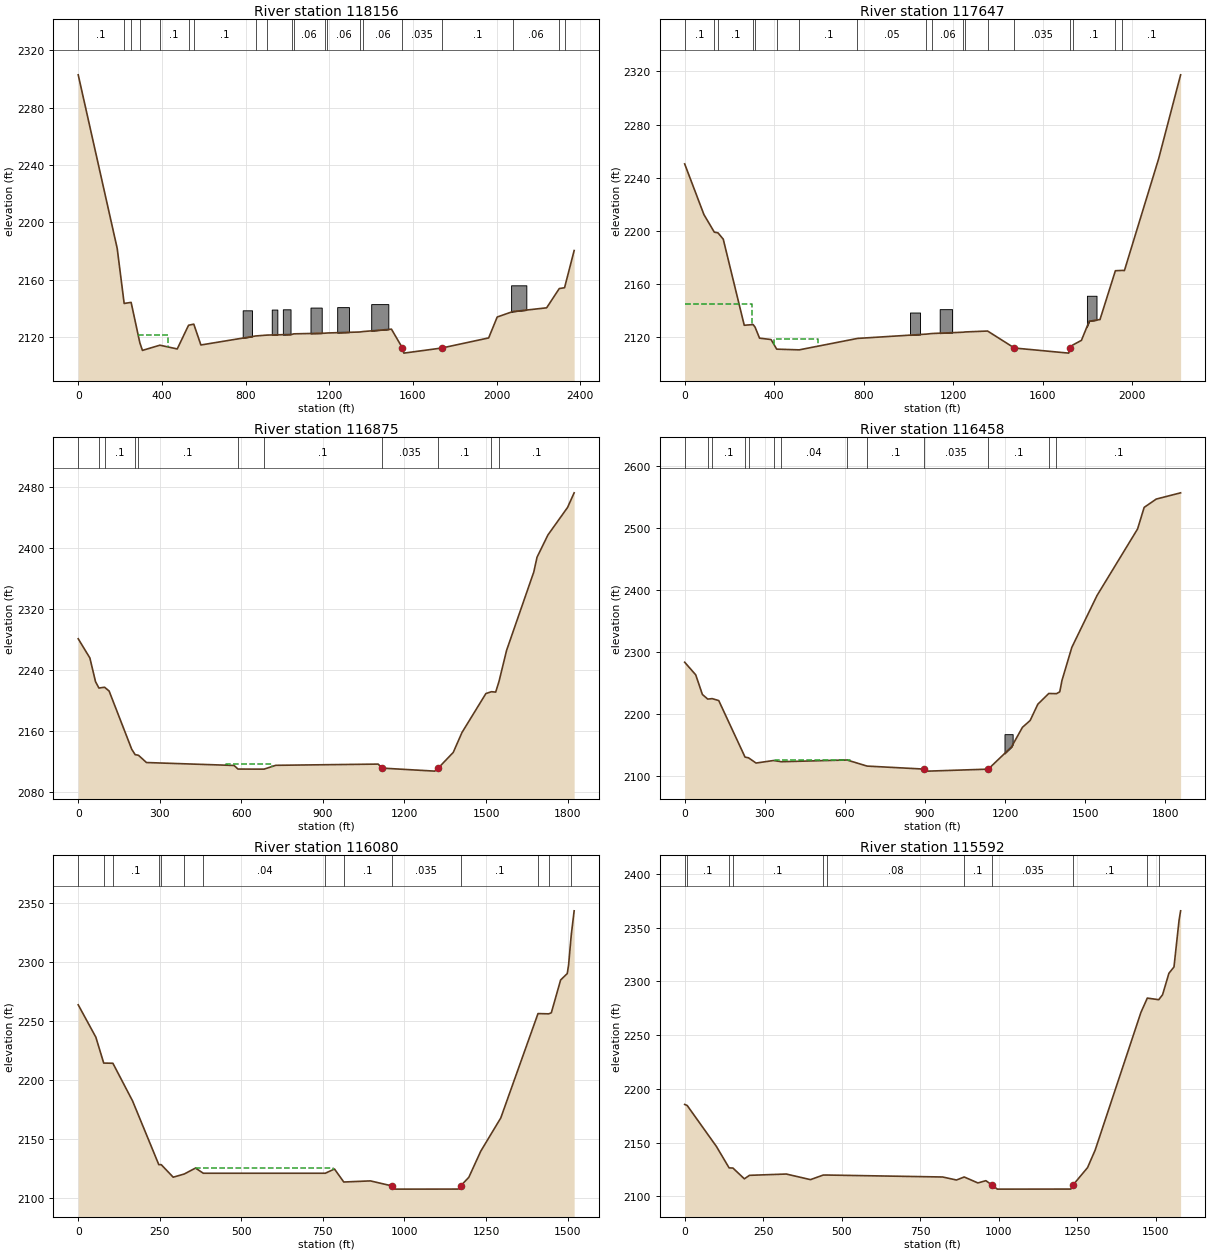
Type RM Length L Ch R = 1 ,118156  ,617.8,509.5,558
BEGIN DESCRIPTION:
channel burned 2.47':
lidar invert = 2111.31
interpolated invert = 2108.84
END DESCRIPTION:
XS GIS Cut Line= 3
2228306.03006347444666.0216329982228152.80121746445200.040854341
2226711.73752228446304.565191875
#Sta/Elev= 30
       0 2302.99   186.4 2181.92   219.7  2143.5     253 2144.24   294.6 2116.11
   307.1 2110.74   390.3 2114.37   473.5 2111.76   527.6  2128.3   552.6 2129.06
   586.6 2114.52   848.7 2120.81   904.9 2121.44    1020 2121.85  1030.9 2122.29
  1178.6 2122.74  1191.4 2122.89  1346.5 2123.58  1361.4 2123.88  1497.7 2125.56
  1550.3  2112.4  1556.9 2108.84 1738.64 2112.41  1962.5 2119.45  2003.3 2134.03
  2077.5 2137.83  2239.6 2140.45  2300.1 2153.89  2325.3 2154.46  2371.2 2180.41
#Mann= 20 ,-1,0
       0      .1       0   219.7    .016       0     253      .1       0
   294.6     .04       0   390.3      .1       0   527.6    .016       0
   552.6      .1       0   848.7    .016       0   904.9     .06       0
    1020    .016       0  1030.9     .06       0  1178.6    .016       0
  1191.4     .06       0  1346.5    .016       0  1361.4     .06       0
  1550.3    .035       0 1738.64      .1       0  2077.5     .06       0
  2300.1    .016       0  2325.3      .1       0
#XS Ineff= 1 ,-1
  283.99  430.29 2121.34
Permanent Ineff=
       F
#Block Obstruct= 7 ,-1
  786.48  831.03  2138.7  925.45  952.07 2139.23  978.45 1015.13 2139.41
  1110.6 1164.22  2140.6 1238.18 1294.52 2140.93 1400.83 1482.68 2143.03
 2069.73 2142.55 2156.15
Bank Sta=1550.3,1738.64
XS Rating Curve= 0 ,0
Exp/Cntr(USF)=0,0
Exp/Cntr=0.3,0.1

Type RM Length L Ch R = 1 ,117647  ,481.3,771.8,837.2
BEGIN DESCRIPTION:
channel burned 2.65':
lidar invert = 2110.69
interolated invert = 2108.04
END DESCRIPTION:
Node Name=R
XS GIS Cut Line= 3
2228011.66699153444356.3816967032227272.55014589445340.359337829
2226370.19276993445734.857286115
#Sta/Elev= 30
       0 2250.37      86 2212.25   132.4 2199.04   148.8 2198.51   172.3 2193.75
   266.1    2129   305.9 2129.51   314.5 2127.59   334.5  2119.3   385.9 2118.25
   411.2 2111.03   511.6  2110.5   771.6 2119.09  1080.1 2122.34  1104.7 2122.79
  1243.7 2123.77  1252.8 2123.97  1353.3 2124.65 1473.09 2111.88  1715.6 2108.04
    1722 2111.73  1733.1 2114.07  1772.4 2117.65  1807.3 2132.07  1855.3  2133.3
  1924.1 2170.02  1954.5 2170.25  1964.5 2170.17  2117.3 2254.24  2215.5 2317.37
#Mann= 18 ,-1,0
       0      .1       0   132.4    .016       0   148.8      .1       0
   305.9    .016       0   314.5      .1       0   411.2     .04       0
   511.6      .1       0   771.6     .05       0  1080.1    .016       0
  1104.7     .06       0  1243.7    .016       0  1252.8     .07       0
  1353.3      .1       0 1473.09    .035       0    1722     .06       0
  1733.1      .1       0  1924.1    .016       0  1954.5      .1       0
#XS Ineff= 2 ,-1
       0   298.9    2145  400.17   593.8  2118.9
Permanent Ineff=
       F       F
#Block Obstruct= 3 ,-1
 1006.45 1051.46 2138.57 1139.24 1194.37 2141.11 1796.99 1839.79 2151.19
Bank Sta=1473.09,1722
XS Rating Curve= 0 ,0
Exp/Cntr(USF)=0,0
Exp/Cntr=0.3,0.1

Type RM Length L Ch R = 1 ,116875  ,190.6,416.8,389.9
BEGIN DESCRIPTION:
channel burned 2.14':
lidar invert = 2109.94
effective invert = 2107.80
END DESCRIPTION:
XS GIS Cut Line= 4
2227929.36292992444239.9231816932227477.15401282444370.825762961
2227295.67543424444701.0572747952226319.85619206444736.757978778
#Sta/Elev= 30
       0 2281.37    42.9 2256.19    63.7 2225.09    76.2 2216.76      97  2217.8
   113.7 2212.82     197 2136.36   209.4 2129.42   221.6 2128.57   251.1 2119.07
   573.4 2115.22   587.6 2110.51   683.4 2110.39   726.5 2115.42  1103.3 2117.02
  1117.5 2111.76  1311.4  2107.8  1323.4 2111.52  1379.4 2132.32  1411.5 2158.43
  1499.5 2209.54    1520 2211.93  1535.5 2211.43  1547.6 2225.24  1575.6 2266.17
  1675.6 2368.87  1687.6 2388.29  1727.7  2417.5  1799.7 2453.47  1824.1 2472.72
#Mann= 11 ,-1,0
       0      .1       0    76.2    .016       0      97      .1       0
   209.4    .016       0   221.6      .1       0   587.6    .035       0
   683.4      .1       0  1117.5    .035       0  1323.4      .1       0
    1520    .016       0  1547.6      .1       0
#XS Ineff= 1 ,-1
  543.89  712.56 2117.56
Permanent Ineff=
       F
Bank Sta=1117.5,1323.4
XS Rating Curve= 0 ,0
Exp/Cntr(USF)=0,0
Exp/Cntr=0.3,0.1

Type RM Length L Ch R = 1 ,116458  ,332.1,378.7,383.5
BEGIN DESCRIPTION:
channel burned 2.05':
lidar invert = 2109.56
interpolated invert = 2107.51
END DESCRIPTION:
XS GIS Cut Line= 2
2227916.44334884444070.7107686332226107.19413774444487.881012798
#Sta/Elev= 30
       0 2283.54    41.3 2263.21    66.4 2231.36    86.5 2223.96   102.9 2224.71
   127.5  2221.6     226 2130.19   239.1 2129.03   267.1 2120.59   332.8 2124.66
   361.5 2122.71   607.8 2125.49   682.8 2115.67   896.3 2110.79   911.6 2107.51
  1136.5 2110.71  1223.6 2146.68  1264.6  2178.4  1293.3  2189.3  1322.1 2215.66
  1363.1 2233.04  1391.9 2232.73  1404.2 2235.65  1412.4 2253.91  1449.3 2307.46
  1543.7 2391.35  1695.6 2499.02  1720.2 2533.84  1765.4 2547.27  1856.7 2557.38
#Mann= 13 ,-1,0
       0      .1       0    86.5    .016       0   102.9      .1       0
     226    .016       0   239.1      .1       0   332.8     .07       0
   361.5     .04       0   607.8     .07       0   682.8      .1       0
   896.3    .035       0  1136.5      .1       0  1363.1    .016       0
  1391.9      .1       0
#XS Ineff= 1 ,-1
   339.6  618.432126.206
Permanent Ineff=
       T
#Block Obstruct= 1 ,-1
 1197.36 1227.79 2167.25
Bank Sta=896.3,1136.5
XS Rating Curve= 0 ,0
Exp/Cntr(USF)=0,0
Exp/Cntr=0.3,0.1

Type RM Length L Ch R = 1 ,116080  ,492.5,487.4,492.8
BEGIN DESCRIPTION:
channel burned 1.87':
lidar invert = 2109.12
interpolated invert = 2107.25
c/e 0.5/0.7 to correct drawdown
END DESCRIPTION:
XS GIS Cut Line= 3
2227914.01559525443796.3099644792227137.95014208443871.120964479
     2226411.472       444015.35
#Sta/Elev= 30
       0 2263.87    54.1 2236.35    78.2 2214.36   106.3 2214.21   166.6 2182.21
     247 2128.07   254.6 2128.02   291.2 2117.39     325 2120.09   359.5 2125.13
   383.5 2120.75   757.5 2120.75   785.6 2124.34   814.1 2113.29   895.7 2114.25
   960.9 2110.04   973.1 2107.25  1164.8 2107.29    1173 2110.16  1197.4 2117.28
  1234.1 2139.55  1295.3  2167.7  1409.5 2256.41  1442.1  2256.2  1450.3 2257.08
  1478.8 2284.95  1499.2 2290.45  1503.3 2297.79  1511.4 2323.21  1520.3 2343.73
#Mann= 14 ,-1,0
       0      .1       0    78.2    .016       0   106.3      .1       0
     247    .016       0   254.6      .1       0     325     .07       0
   383.5     .04       0   757.5     .07       0   814.1      .1       0
   960.9    .035       0    1173      .1       0  1409.5    .016       0
  1442.1     .08       0  1511.4      .1       0
#XS Ineff= 1 ,-1
  362.37  779.712125.005
Permanent Ineff=
       T
Bank Sta=960.9,1173
XS Rating Curve= 0 ,0
Exp/Cntr=0.7,0.5

Type RM Length L Ch R = 1 ,115592  ,498.1,495.7,495.2
BEGIN DESCRIPTION:
channel burned 1.76':
lidar invert = 2108.56
interpolated invert = 2106.80
END DESCRIPTION:
XS GIS Cut Line= 2
2227892.03214782443272.545136349     2226331.288      443515.384
#Sta/Elev= 30
       0 2185.57       8 2184.62   101.1 2146.49   141.5 2126.58   153.7 2126.41
   190.1 2116.37   206.3 2119.63   323.7 2120.84   400.6 2115.63   441.1 2119.87
   452.3 2119.91   821.6 2118.08   865.7 2115.28   890.2  2118.1   933.9 2112.56
   959.3 2114.66   979.5 2110.44   995.7  2106.8    1230 2106.85  1235.9  2110.3
  1283.1 2126.82  1307.4 2143.17  1453.1  2271.2  1473.4 2284.51  1509.8 2283.02
    1522 2287.64  1542.2 2307.56  1558.4  2313.5  1574.6 2357.02  1579.5 2365.69
#Mann= 11 ,-1,0
       0    .016       0       8      .1       0   141.5    .016       0
   153.7      .1       0   441.1    .016       0   452.3     .08       0
   890.2      .1       0   979.5    .035       0  1235.9      .1       0
  1473.4    .016       0  1509.8     .07       0
Bank Sta=979.5,1235.9
XS Rating Curve= 0 ,0
Exp/Cntr=0.3,0.1

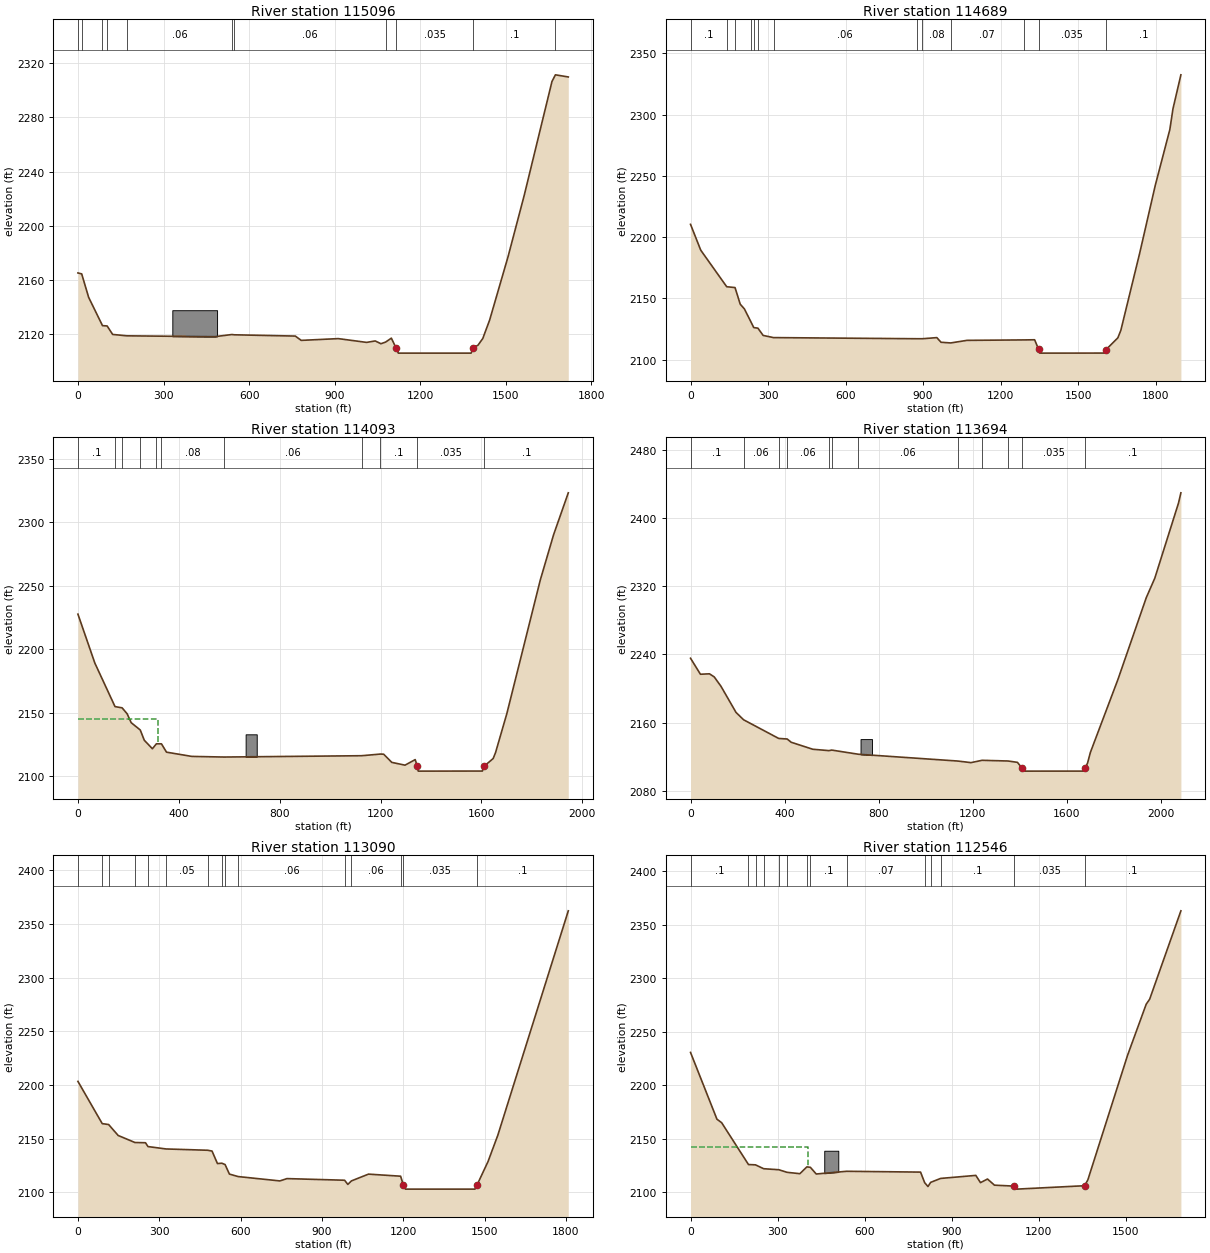
Type RM Length L Ch R = 1 ,115096  ,381.8,407.6,414
BEGIN DESCRIPTION:
channel burned 2.02':
lidar invert = 2108
interpolated invert = 2105.98
END DESCRIPTION:
XS GIS Cut Line= 2
2227945.23721886442757.034032654     2226247.673      443029.033
#Sta/Elev= 30
       0 2165.15    13.2 2164.45    37.5 2147.18    86.1 2126.27   102.4 2126.03
   121.7 2119.77   171.2 2118.75   479.1  2118.1   539.9 2119.71     548  2119.5
   762.2 2118.56   782.9 2115.38   912.6 2116.69  1012.2  2113.9  1042.2 2114.97
  1062.4 2112.91  1078.6 2114.12  1098.9 2117.04  1115.1 2109.87  1123.2 2105.98
  1378.4 2105.98  1386.5 2109.96  1402.7 2111.85  1419.4 2116.76  1443.5 2130.43
  1508.1 2177.22  1564.8  2222.5    1662 2306.43  1674.1 2311.34  1719.2 2309.77
#Mann= 11 ,-1,0
       0    .016       0    13.2      .1       0    86.1    .016       0
   102.4      .1       0   171.2     .06       0   539.9    .016       0
     548     .06       0  1078.6      .1       0  1115.1    .035       0
  1386.5      .1       0  1674.1    .016       0
#Block Obstruct= 1 ,-1
  330.93  487.83 2137.65
Bank Sta=1115.1,1386.5
XS Rating Curve= 0 ,0
Exp/Cntr=0.3,0.1

Type RM Length L Ch R = 1 ,114689  ,592.3,595.4,592
BEGIN DESCRIPTION:
channel burned = 2.01':
lidar invert = 2107.31
effective invert = 2105.30
END DESCRIPTION:
XS GIS Cut Line= 2
2228127.30804986 442384.989171872226241.67331109442598.823863651
#Sta/Elev= 30
       0 2210.37    39.4 2189.34     140 2159.48   172.2 2158.78   192.4  2145.2
   208.5 2141.36   232.6 2131.27   244.7 2126.13   260.8 2125.67   280.9 2119.75
   321.2 2117.97   876.7 2117.04   896.8 2117.03   953.2 2117.96   969.3 2114.16
  1006.8 2113.61  1069.9 2115.72  1290.2 2116.08  1331.6  2116.2  1347.3  2108.3
  1351.7  2105.3  1605.4 2105.34  1608.3 2108.22  1653.7 2117.77  1665.2 2123.82
  1738.2 2186.85  1798.6 2242.26  1854.9 2287.72    1867 2304.64  1897.7 2332.38
#Mann= 13 ,-1,0
       0      .1       0     140    .016       0   172.2      .1       0
   232.6     .05       0   244.7    .016       0   260.8      .1       0
   321.2     .06       0   876.7    .016       0   896.8     .08       0
  1006.8     .07       0  1290.2      .1       0  1347.3    .035       0
  1608.3      .1       0
Bank Sta=1347.3,1608.3
XS Rating Curve= 0 ,0
Exp/Cntr=0.3,0.1

Type RM Length L Ch R = 1 ,114093  ,405.5,399.8,402.4
BEGIN DESCRIPTION:
channel burned 2.13':
lidar invert = 2106.22
interpolated invert = 2104.09
END DESCRIPTION:
Node Name=Q
XS GIS Cut Line= 3
2228091.20493216441868.6242210072226949.34416879441912.758682604
      2226154.35      442019.117
#Sta/Elev= 30
       0 2227.58    67.1 2189.09   147.1 2154.85   175.2 2153.89   195.2 2149.17
   211.2 2142.21   247.2 2136.45   263.2 2128.38   295.3  2121.7   311.3  2125.6
   331.3 2125.56   351.3 2119.01   451.4 2115.67   579.5 2115.17    1125 2116.21
  1199.5 2117.51  1212.5  2117.4  1244.8 2110.98  1297.2 2108.78  1337.6 2113.15
 1345.592108.215  1349.7 2104.09    1604 2104.15 1611.992108.136  1646.8 2113.98
  1656.1 2118.53  1700.8 2149.14    1834 2254.61  1886.5 2290.07  1944.8 2323.02
#Mann= 11 ,-1,0
       0      .1       0   147.1    .016       0   175.2     .07       0
   247.2     .08       0   311.3    .016       0   331.3     .08       0
   579.5     .06       0    1125    .016       0  1199.5      .1       0
 1345.59    .035       0 1611.99      .1       0
#XS Ineff= 2 , 0
           319.3    2145
Permanent Ineff=
       F       F
#Block Obstruct= 1 ,-1
  665.13  709.11 2133.05
Bank Sta=1345.59,1611.99
XS Rating Curve= 0 ,0
Exp/Cntr=0.3,0.1

Type RM Length L Ch R = 1 ,113694  ,578.1,603.8,611.1
BEGIN DESCRIPTION:
channel burned 2.53':
lidar invert = 2105.81
interpolated invert = 2103.28
END DESCRIPTION:
XS GIS Cut Line= 2
2228092.20770612441382.5340340872226021.96758522441624.530863651
#Sta/Elev= 30
       0 2235.54    42.1 2216.79    80.6  2217.3   100.7 2213.65   129.3 2202.73
   193.3 2172.09   225.6 2163.43   374.6 2141.59   410.8 2140.92   427.9 2137.09
   519.5 2128.92     588 2127.29   600.1 2127.95   712.7 2123.09  1135.7  2115.1
  1192.1 2113.24  1239.2 2115.95  1349.2 2115.14  1389.4 2113.59  1408.7 2106.98
  1417.6 2103.28  1671.3 2103.31  1676.5 2106.98  1687.4 2112.55  1699.5 2125.15
  1816.6 2210.62  1937.1 2306.49  1973.4 2329.38  2074.1 2417.33  2084.3 2429.36
#Mann= 12 ,-1,0
       0      .1       0   225.6     .06       0   374.6    .016       0
   410.8     .06       0     588    .016       0   600.1      .1       0
   712.7     .06       0  1135.7      .1       0  1239.2     .06       0
  1349.2      .1       0  1408.7    .035       0  1676.5      .1       0
#Block Obstruct= 1 ,-1
  722.56  771.25 2140.81
Bank Sta=1408.7,1676.5
XS Rating Curve= 0 ,0
Exp/Cntr=0.3,0.1

Type RM Length L Ch R = 1 ,113090  ,670.4,544.4,538.1
BEGIN DESCRIPTION:
channel burned 2.19':
lidar invert = 2105.19
interpolated invert = 2103
END DESCRIPTION:
XS GIS Cut Line= 3
2227785.66904699440672.6777201342227367.00841106440906.896529628
     2226040.709      440990.206
#Sta/Elev= 30
       0 2203.41    89.6 2164.04   113.2 2163.21   148.4 2153.01   210.1 2146.46
   249.2 2146.23   258.4 2142.66   325.1 2140.44   478.4 2139.23   494.6 2138.49
   514.6 2126.84   530.7 2127.14   542.7 2125.93   558.7 2117.02   590.8 2114.71
   744.7 2110.65   771.1 2112.81   983.5 2111.29   995.6 2107.39  1008.7 2110.66
  1071.7 2116.98  1190.2 2115.04    1200 2107.13    1208    2103  1464.5    2103
  1472.5 2107.08  1472.5 2107.09  1512.6 2128.73  1548.7 2153.24  1808.6 2362.38
#Mann= 15 ,-1,0
       0     .08       0    89.6    .016       0   113.2     .06       0
   210.1     .07       0   258.4    .016       0   325.1     .05       0
   478.4      .1       0   530.7    .016       0   542.7     .08       0
   590.8     .06       0   983.5    .045       0  1008.7     .06       0
  1190.2      .1       0    1200    .035       0  1472.5      .1       0
Bank Sta=1200,1472.5
XS Rating Curve= 0 ,0
Exp/Cntr=0.3,0.1

Type RM Length L Ch R = 1 ,112546  ,251,450.2,481.1
BEGIN DESCRIPTION:
channel burned 1.72':
lidar invert = 2104.62
effective invert = 2102.90
END DESCRIPTION:
XS GIS Cut Line= 4
2227634.73232112440184.6746860472226890.99902463440268.911726985
2226775.30229876440384.6084528532226001.11975852440467.459551131
#Sta/Elev= 30
       0 2230.53    91.1 2168.17   107.2 2164.96   199.8 2125.86     224 2125.57
     252 2121.97   304.5    2121   332.7  2118.6     377 2117.31   401.1 2123.68
   413.2 2123.27   433.3 2117.02     538 2119.56   793.1 2118.79   807.2 2108.97
   818.6 2105.33   828.1 2109.24     862 2112.88   983.6 2115.73   999.7 2108.96
  1023.9 2112.33    1048 2106.59  1116.4 2105.72  1124.4  2102.9  1358.8 2106.08
    1370 2111.64  1506.6  2227.7    1571 2275.52    1583 2280.26  1690.7 2362.77
#Mann= 14 ,-1,0
       0      .1       0   199.8    .016       0     224     .06       0
     252    .016       0   304.5     .06       0   332.7     .08       0
   401.1    .016       0   413.2      .1       0     538     .07       0
   807.2    .045       0   828.1     .07       0     862      .1       0
  1116.4    .035       0  1358.8      .1       0
#XS Ineff= 2 , 0
          403.61    2142
Permanent Ineff=
       F       F
#Block Obstruct= 1 ,-1
  461.03   509.4 2138.75
Bank Sta=1116.4,1358.8
XS Rating Curve= 0 ,0
Exp/Cntr=0.3,0.1

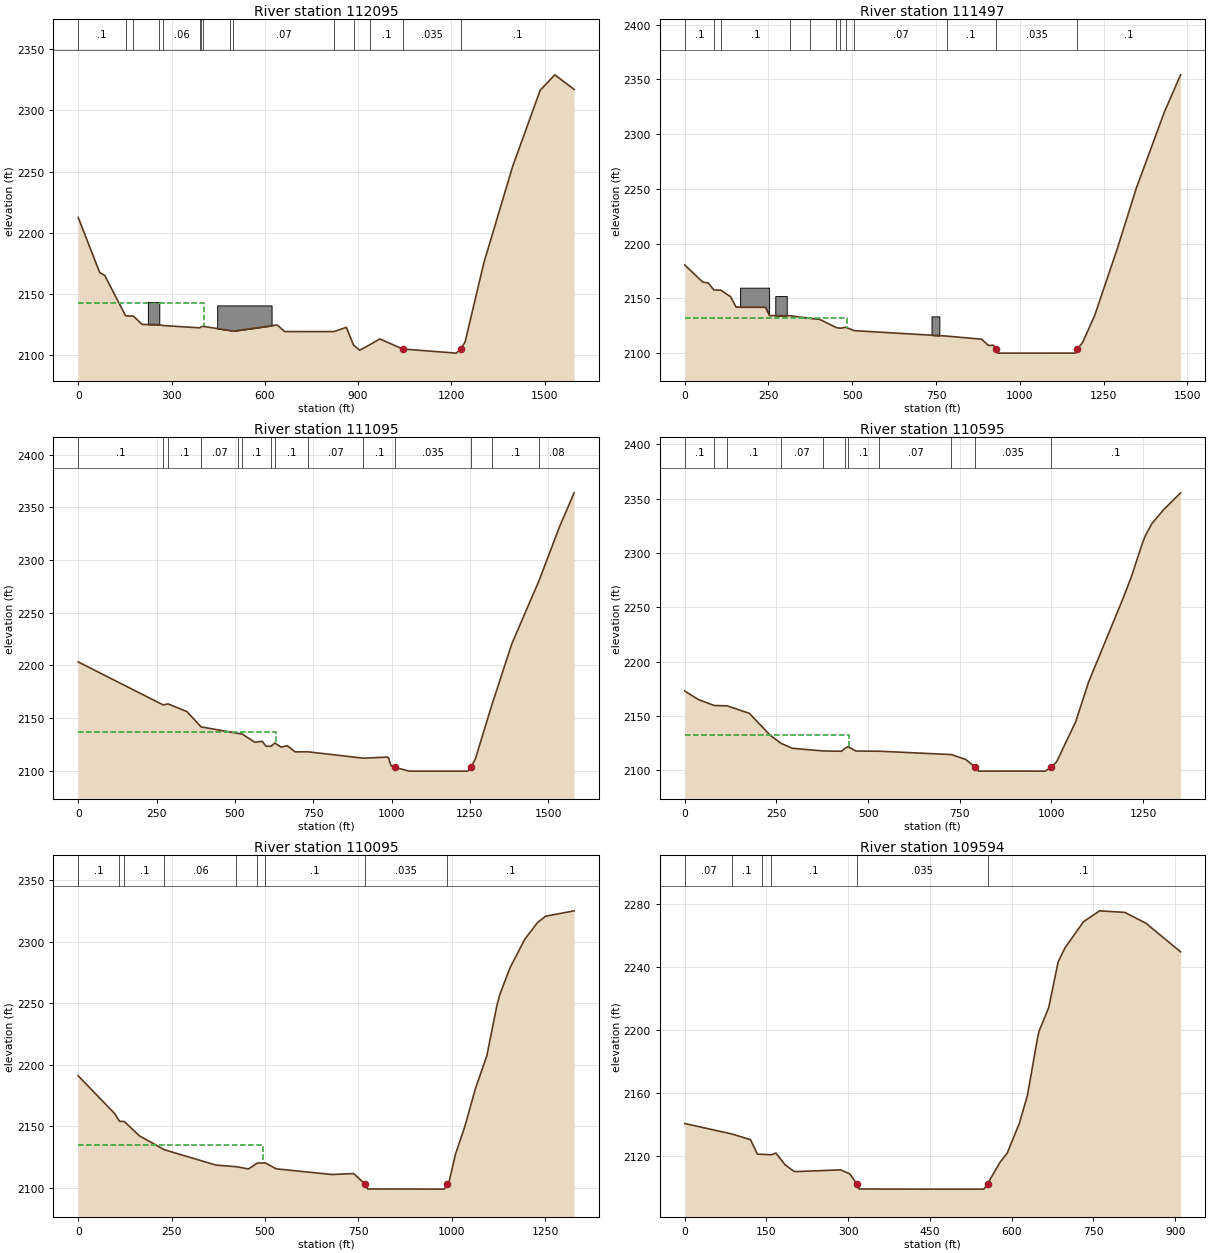
Type RM Length L Ch R = 1 ,112095  ,604.2,598.7,593.7
BEGIN DESCRIPTION:
channel burned 1.91':
lidar invert = 2103.56
interpolated invert = 2101.65
END DESCRIPTION:
XS GIS Cut Line= 3
2227601.10343433439948.0685920362226874.29971991440017.611999467
     2226015.635      439916.715
#Sta/Elev= 30
       0 2212.54    69.2 2167.51    85.3 2165.16   152.2 2132.27   177.7 2131.82
   205.9  2125.1   258.6 2124.91   274.2 2124.18   390.6 2122.32   394.3  2123.1
   402.8  2123.5   487.1 2120.16   499.2 2119.64   639.8 2124.68   663.9 2119.29
   822.5 2119.27   862.2 2122.74   885.3 2108.19   905.4 2104.03   937.4  2108.5
   969.9 2113.26 1043.64 2105.01  1215.6 2101.65  1229.5 2104.97  1243.8 2110.58
  1304.2 2175.31  1396.8 2254.16  1485.4 2316.47  1532.5 2329.11  1594.7 2317.19
#Mann= 15 ,-1,0
       0      .1       0   152.2    .016       0   177.7     .05       0
   258.6    .016       0   274.2     .06       0   390.6     .07       0
   394.3    .016       0   402.8     .05       0   487.1    .016       0
   499.2     .07       0   822.5      .1       0   885.3    .045       0
   937.4      .1       0 1043.64    .035       0  1229.5      .1       0
#XS Ineff= 2 , 0
          404.73 2142.37
Permanent Ineff=
       F       F
#Block Obstruct= 2 ,-1
  224.06   260.7 2143.37  446.88  621.78 2140.66
Bank Sta=1043.64,1229.5
XS Rating Curve= 0 ,0
Exp/Cntr=0.3,0.1

Type RM Length L Ch R = 1 ,111497  ,342,401.3,427.5
BEGIN DESCRIPTION:
channel burned 2.38':
lidar invert = 2102.38
effective invert = 2100
END DESCRIPTION:
XS GIS Cut Line= 3
2227572.20719427439257.050854349 2227012.2669573439412.088758715
2226116.26776265439342.940650701
#Sta/Elev= 30
       0  2180.6      54 2164.86    70.6 2164.04    87.2 2157.66   107.9 2157.51
     137 2151.53   153.6 2142.01   240.8    2142   253.2 2134.26   315.3 2134.16
   373.9 2131.73   402.6 2130.88   452.4 2123.35   464.8 2122.74   480.2  2123.6
   506.4 2120.53   781.2 2115.58     886 2112.71   906.1 2107.07   922.1 2107.19
928.49092103.836   934.1    2100  1166.8 2100.03 1171.582103.801  1187.2 2109.72
    1223 2134.11  1291.5 2196.12  1347.4 2250.61  1431.6 2320.53  1479.7 2354.22
#Mann= 12 ,-1,0
       0      .1       0    87.2    .016       0   107.9      .1       0
   315.3    .016       0   373.9      .1       0   452.4    .016       0
   464.8      .1       0   480.2     .08       0   506.4     .07       0
   781.2      .1       0928.4909    .035       0 1171.58      .1       0
#XS Ineff= 2 , 0
          484.67 2131.87
Permanent Ineff=
       F       F
#Block Obstruct= 3 ,-1
   165.4  251.85 2159.79  270.36  304.49 2152.09  736.51  759.84 2133.56
Bank Sta=928.4909,1171.58
XS Rating Curve= 0 ,0
Exp/Cntr=0.3,0.1

Type RM Length L Ch R = 1 ,111095  ,454.5,500.5,517.7
BEGIN DESCRIPTION:
channel burned 2.02':
lidar invert = 2101.69
interpolated invert = 2099.67
END DESCRIPTION:
XS GIS Cut Line= 3
  2227718.783317439023.5165920362226921.90065855439065.593226611
     2226164.122       438860.63
#Sta/Elev= 30
       0 2203.35     271 2162.56     287 2163.49   347.1 2156.19   392.1 2141.69
   511.3  2135.4   523.3 2134.92   563.4 2127.14   587.4 2127.98   599.4 2123.34
   615.5 2123.26   627.5 2126.36   647.5  2122.5   667.5 2123.79   692.7 2117.94
   732.6 2118.04   910.6 2111.94   986.2 2113.02   990.4 2112.46   998.7  2104.7
  1011.7 2103.22  1056.7 2099.67  1243.2 2099.67  1254.3 2103.32    1268  2111.6
  1320.5 2162.66    1384 2220.53  1471.1 2280.64  1536.8 2332.04    1583 2363.89
#Mann= 14 ,-1,0
       0      .1       0     271    .016       0     287      .1       0
   392.1     .07       0   511.3    .016       0   523.3      .1       0
   615.5    .016       0   627.5      .1       0   732.6     .07       0
   910.6      .1       0  1011.7    .035       0  1254.3     .08       0
  1320.5      .1       0  1471.1     .08       0
#XS Ineff= 2 , 0
           631.8 2136.61
Permanent Ineff=
       F       F
Bank Sta=1011.7,1254.3
XS Rating Curve= 0 ,0
Exp/Cntr=0.3,0.1

Type RM Length L Ch R = 1 ,110595  ,496.5,499.9,502.2
BEGIN DESCRIPTION:
channel burned 1.93':
lidar invert = 2101.19
interpolated invert = 2099.26
END DESCRIPTION:
XS GIS Cut Line= 2
2227586.85789502438852.047151023     2226340.163       438328.04
#Sta/Elev= 30
       0 2173.05    37.6 2165.11      81 2159.68   115.7 2159.36   176.5 2152.45
   232.9 2132.37   263.2 2124.75   293.6 2120.29   376.9 2117.85   428.1 2117.56
   436.8 2120.26   445.5 2121.73   467.2 2117.74   531.1 2117.59   727.5 2114.49
   766.6 2109.93     792 2103.01   801.3 2099.29   983.5 2099.26  1000.1 2103.27
  1013.9 2107.67    1066 2144.59  1101.6 2181.48  1194.6 2257.67  1217.8 2277.99
  1248.2 2309.26  1257.1 2316.62  1274.2 2327.22  1305.6 2339.82  1352.3 2355.44
#Mann= 11 ,-1,0
       0      .1       0      81    .016       0   115.7      .1       0
   263.2     .07       0   376.9      .1       0   436.8    .016       0
   445.5      .1       0   531.1     .07       0   727.5      .1       0
     792    .035       0  1000.1      .1       0
#XS Ineff= 2 , 0
          448.37 2132.42
Permanent Ineff=
       F       F
Bank Sta=792,1000.1
XS Rating Curve= 0 ,0
Exp/Cntr=0.3,0.1

Type RM Length L Ch R = 1 ,110095  ,521.3,501.3,492.2
BEGIN DESCRIPTION:
channel burned 1.89':
lidar invert = 2100.9
interpolated invert = 2099.01
END DESCRIPTION:
Node Name=P
XS GIS Cut Line= 2
2227753.31106946438395.917837072     2226538.267      437860.611
#Sta/Elev= 30
       0 2191.12    97.4 2160.48   110.5 2154.13   123.6 2153.92   163.8 2142.31
   230.5 2131.05   368.4 2118.57   423.5 2117.23   455.8 2115.44   479.3 2120.14
   500.6 2120.33   530.1  2115.5   679.6  2110.9   737.2 2111.67   767.6 2103.27
   774.9 2099.15     980 2099.01     9882103.115   993.5 2105.87  1010.3 2127.75
  1034.6 2149.44  1063.4 2180.65    1094 2207.45  1120.2 2247.32  1128.6  2257.1
  1155.9 2278.84  1195.4 2302.02  1229.5 2315.62  1251.3  2320.8  1327.7 2325.18
#Mann= 9 ,-1,0
       0      .1       0   110.5    .013       0   123.6      .1       0
   230.5     .06       0   423.5      .1       0   479.3    .016       0
   500.6      .1       0   767.6    .035       0     988      .1       0
#XS Ineff= 2 , 0
          493.75 2134.86
Permanent Ineff=
       F       F
Bank Sta=767.6,988
XS Rating Curve= 0 ,0
Exp/Cntr=0.3,0.1

Type RM Length L Ch R = 1 ,109594  ,517.4,500,491.6
BEGIN DESCRIPTION:
channel burned 1.87':
lidar invert = 2100.72
interpolated invert = 2098.85
END DESCRIPTION:
XS GIS Cut Line= 2
     2227578.026      437733.853      2226720.03      437430.634
#Sta/Elev= 30
       0 2140.47    86.8 2133.82   120.8 2130.21   133.5 2121.02     142 2120.94
   158.9 2120.61   167.4 2121.72   184.4 2114.22   201.4 2109.95   286.2 2111.07
   303.2 2108.45   315.9  2102.2   320.1 2098.94   434.2 2098.85   549.2 2098.85
  555.792102.299   578.9 2116.03   591.7  2121.6   614.3 2140.81   628.9 2158.26
   647.7 2195.16   650.3 2199.04     668 2214.02   685.3 2243.01   697.7 2251.82
   731.7 2268.42   761.4 2275.36   807.6 2274.37   846.2 2267.53     910 2249.34
#Mann= 6 ,-1,0
       0     .07       0    86.8      .1       0     142    .016       0
   158.9      .1       0   315.9    .035       0  555.79      .1       0
Bank Sta=315.9,555.79
XS Rating Curve= 0 ,0
Exp/Cntr=0.3,0.1

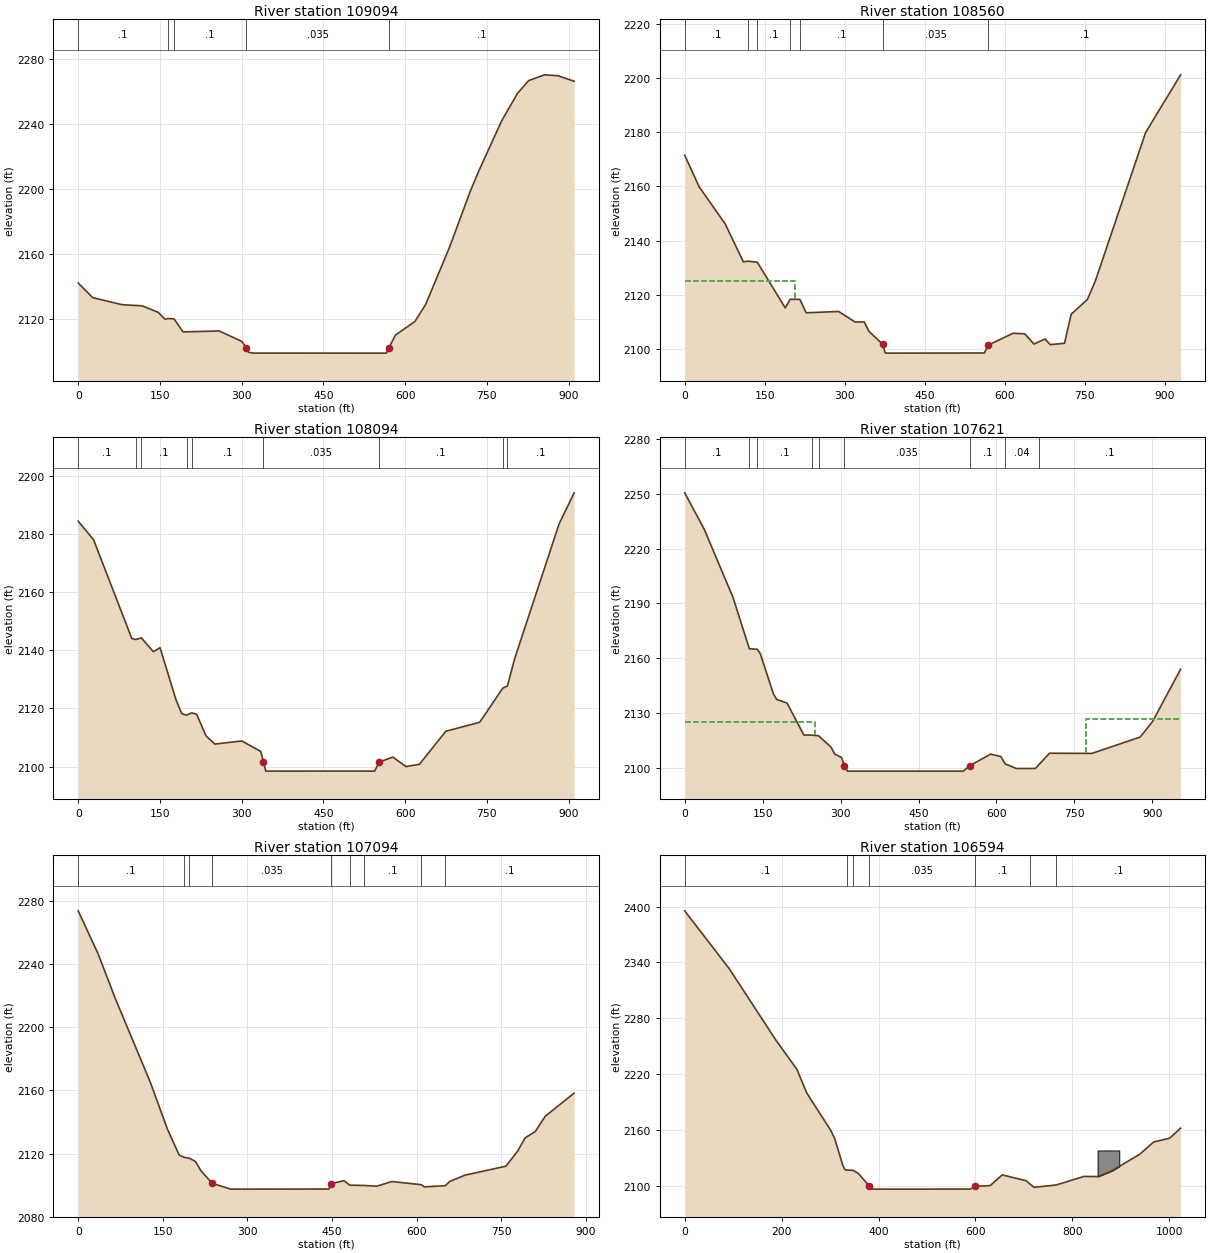
Type RM Length L Ch R = 1 ,109094  ,689.5,533.1,404.5
BEGIN DESCRIPTION:
channel burned 1.75':
lidar invert = 2100.47
interpolated invert = 2098.72
END DESCRIPTION:
XS GIS Cut Line= 2
     2227741.819      437226.315      2226863.84      436987.039
#Sta/Elev= 30
       0 2141.96    26.6 2132.94    80.5 2128.59   117.8 2127.86   146.8 2123.86
   159.2 2119.67   165.2 2120.04   175.8 2119.85   192.4 2111.81   258.7 2112.38
   300.2 2105.92   308.5 2102.08   308.5 2102.06   312.6 2099.21   321.5 2098.75
   510.5 2098.72   565.5 2098.72   569.7 2101.81   582.1 2109.84     618 2118.29
   637.6 2128.79   681.6 2164.24     719 2198.18   735.5 2211.39     777 2241.94
     806 2258.85   826.5 2266.74   855.6 2270.31   880.6 2269.75     910 2266.35
#Mann= 5 ,-1,0
       0      .1       0   165.2    .016       0   175.8      .1       0
   308.5    .035       0   569.7      .1       0
Bank Sta=308.5,569.7
XS Rating Curve= 0 ,0
Exp/Cntr=0.3,0.1

Type RM Length L Ch R = 1 ,108560  ,470.3,466.9,464.8
BEGIN DESCRIPTION:
channel burned 1.62':
lidar invert = 2100.22
effective invert = 2098.60
END DESCRIPTION:
XS GIS Cut Line= 2
2227785.15213951436386.2647791222226931.87908137436755.164941854
#Sta/Elev= 30
       0 2171.51    27.3 2159.81      76 2146.18     110 2132.23   118.7 2132.48
   136.2 2132.06   188.5 2115.25   197.7 2118.42   215.9 2118.41   227.7 2113.46
   288.7 2113.93   319.4 2110.06   336.6 2110.09   345.3 2106.67   371.5 2101.78
   375.8 2098.71   380.1  2098.6   561.7 2098.65   568.9 2101.54   615.5 2105.91
   637.3 2105.72   654.7 2101.96   675.3  2103.8   685.2 2101.74   711.9 2102.22
   724.5 2112.92     755 2118.41   769.7 2125.15   863.9  2179.8   929.6  2201.1
#Mann= 7 ,-1,0
       0      .1       0   118.7    .016       0   136.2      .1       0
   197.7    .016       0   215.9      .1       0   371.5    .035       0
   568.9      .1       0
#XS Ineff= 2 , 0
           206.8    2125
Permanent Ineff=
       F       F
Bank Sta=371.5,568.9
XS Rating Curve= 0 ,0
Exp/Cntr=0.3,0.1

Type RM Length L Ch R = 1 ,108094  ,525.2,472.8,396.9
BEGIN DESCRIPTION:
channel burned 1.55':
lidar invert = 2100
interpolated invert = 2098.45
END DESCRIPTION:
XS GIS Cut Line= 2
     2227549.854       435971.31      2226720.65      436346.171
#Sta/Elev= 30
       0 2184.31    28.2 2177.93    98.4 2143.99   105.5 2143.67     116 2144.22
   137.9 2139.47   150.2 2140.86   179.3 2123.04   190.1 2118.18   198.7 2117.69
   208.5 2118.47   217.3 2117.98   234.5 2110.58   250.6 2107.76   300.3 2108.81
   335.2 2105.18   339.9 2101.52   344.2 2098.45   543.8 2098.46   552.4 2101.59
   577.4 2103.27   601.3 2100.02     626 2100.79   674.5 2112.14   736.7 2115.24
   778.8  2126.9   787.6 2127.73   800.8 2137.06   882.4 2183.39     910 2194.06
#Mann= 9 ,-1,0
       0      .1       0   105.5    .016       0     116      .1       0
   198.7    .016       0   208.5      .1       0   339.9    .035       0
   552.4      .1       0   778.8    .016       0   787.6      .1       0
Bank Sta=339.9,552.4
XS Rating Curve= 0 ,0
Exp/Cntr=0.3,0.1

Type RM Length L Ch R = 1 ,107621  ,602.3,527,395.1
BEGIN DESCRIPTION:
channel burned 1.45':
lidar invert = 2099.75
interpolated invert = 2098.30
END DESCRIPTION:
Node Name=O
XS GIS Cut Line= 2
     2227271.204      435442.811     2226542.878 436059.50884878
#Sta/Elev= 30
       0 2250.54    37.9 2230.46    93.1 2193.25   124.5  2165.2   139.8 2164.97
   145.5 2162.58   170.8 2140.54   176.9 2137.54   196.8 2135.56   229.3 2118.08
     245 2117.97   257.5 2117.66   281.8 2111.39   288.4  2107.7   301.8 2105.73
   307.5 2101.22   313.2  2098.3     536  2098.3   548.4 2101.23   588.5 2107.61
   608.4  2106.3   616.5 2102.31   638.2 2099.75   674.9 2099.76   682.1 2101.99
     702 2108.09   783.6    2108   876.5 2116.92   900.7  2125.6   954.3 2154.08
#Mann= 9 ,-1,0
       0      .1       0   124.5    .016       0   139.8      .1       0
     245    .016       0   257.5      .1       0   307.5    .035       0
   548.4      .1       0   616.5     .04       0   682.1      .1       0
#XS Ineff= 2 , 0
           250.7    2125  771.95         2126.58
Permanent Ineff=
       F       F
Bank Sta=307.5,548.4
XS Rating Curve= 0 ,0
Exp/Cntr=0.3,0.1

Type RM Length L Ch R = 1 ,107094  ,527.5,499.3,422.5
BEGIN DESCRIPTION:
channel burned 1.41':
lidar invert = 2098.94
interpolated invert = 2097.53
END DESCRIPTION:
XS GIS Cut Line= 2
2226673.26203493435094.5197324872226284.21617444435883.182534829
#Sta/Elev= 30
       0  2273.5    35.7 2245.99    65.4 2218.39   127.9 2165.06   158.1 2135.57
     179 2119.09     188 2117.62   196.9 2117.11   208.1 2114.96   217.8 2109.09
   237.5 2101.24   270.6 2097.53   444.5 2097.59     449 2101.06   471.3 2102.85
   481.7 2100.03   507.6 2099.85   529.3 2099.36     556 2102.35   608.2 2100.34
     614 2098.97   650.9 2099.69   658.6 2102.33   685.4 2106.32   758.5 2112.06
   779.4 2121.67   792.4 2129.94   810.3 2133.85   828.1  2143.6   879.4 2158.23
#Mann= 9 ,-1,0
       0      .1       0     188    .016       0   196.9      .1       0
   237.5    .035       0     449      .1       0   481.7    .045       0
   507.6      .1       0   608.2    .045       0   650.9      .1       0
Bank Sta=237.5,449
XS Rating Curve= 0 ,0
Exp/Cntr=0.3,0.1

Type RM Length L Ch R = 1 ,106594  ,457.9,452,432
BEGIN DESCRIPTION:
channel burned 1.93':
lidar invert = 2098.05
interpolated invert = 2096.12
END DESCRIPTION:
XS GIS Cut Line= 2
     2226162.282       434780.132225923.89848839435775.185244097
#Sta/Elev= 30
       0 2395.42    91.6 2333.44   188.4 2256.24   231.6 2224.94     252 2199.43
   301.5 2159.21   309.6 2150.36     326 2122.17   330.1 2117.32   335.3 2116.52
   346.6 2116.44   357.7 2113.32   380.9 2099.41   387.7 2096.16   461.8 2096.12
   589.9  2096.2     599  2099.1   630.4 2099.91   655.1 2111.44   704.4 2105.17
   712.6 2101.48   720.9 2098.08   766.6 2100.57   823.7 2109.79   852.5 2109.61
   881.3 2115.75   938.9 2133.63   967.7  2146.9  1000.6 2150.87  1023.2 2161.75
#Mann= 7 ,-1,0
       0      .1       0   335.3    .016       0   346.6      .1       0
   380.9    .035       0     599      .1       0   712.6    .045       0
   766.6      .1       0
#Block Obstruct= 1 ,-1
  851.89  896.64 2137.71
Bank Sta=380.9,599
XS Rating Curve= 0 ,0
Exp/Cntr=0.3,0.1

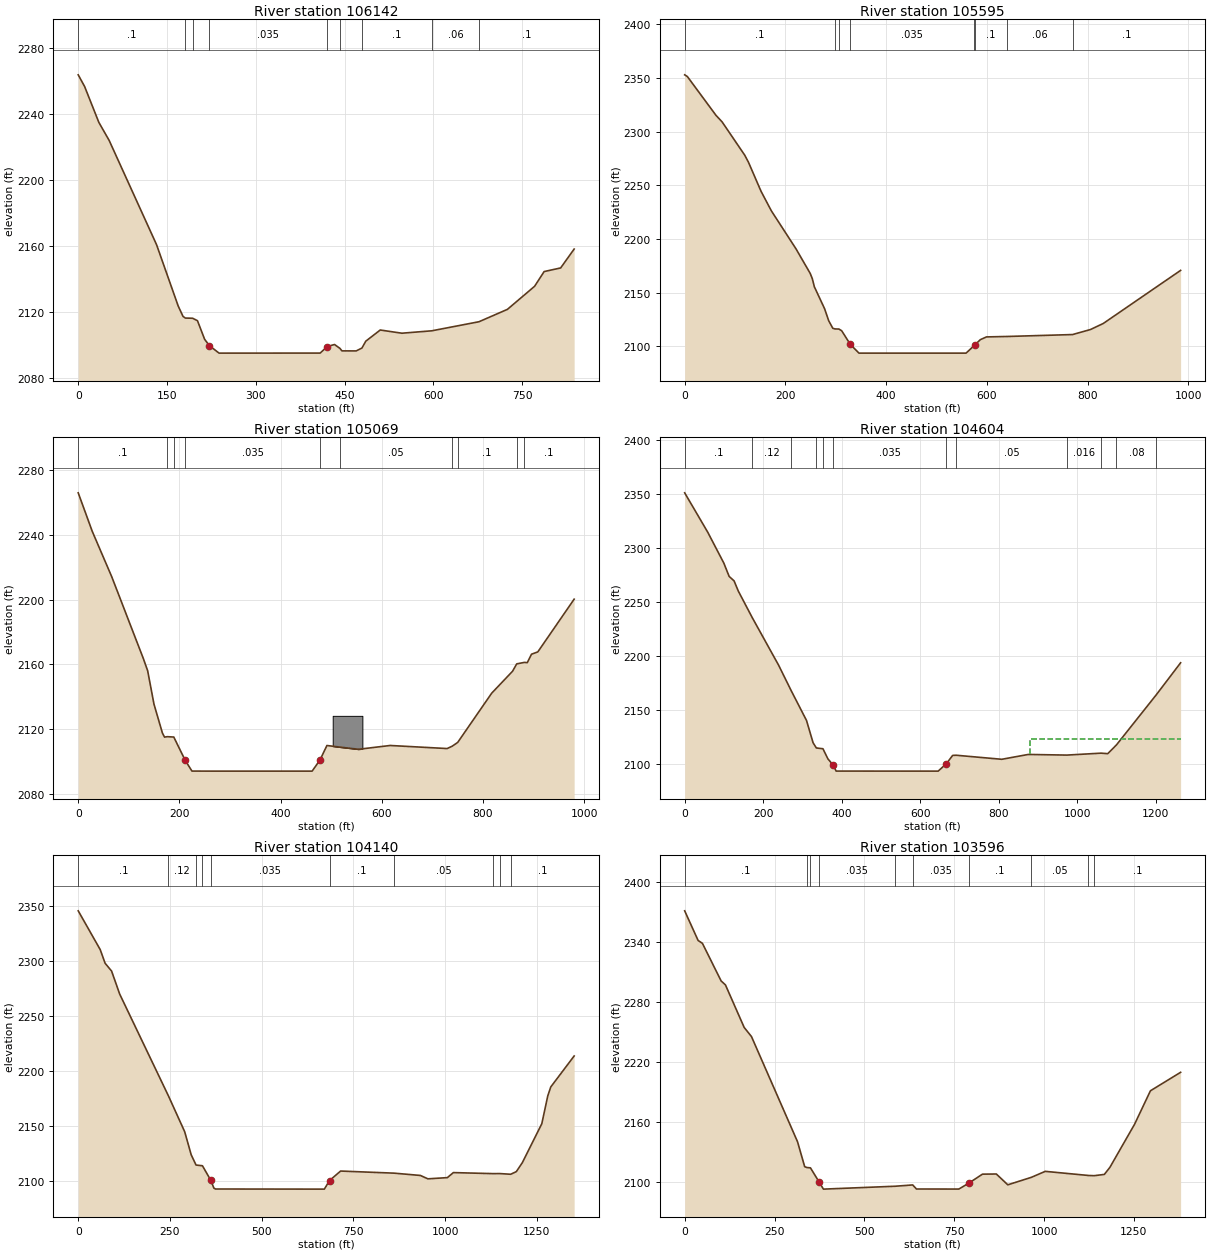
Type RM Length L Ch R = 1 ,106142  ,546,547.8,549.7
BEGIN DESCRIPTION:
channel burned 1.34':
lidar invert = 2096.34
effective invert = 2095
END DESCRIPTION:
XS GIS Cut Line= 2
2225666.44361619434834.928465369 2225519.8602558435659.603592975
#Sta/Elev= 30
       0 2263.93    10.8 2256.85    34.8 2235.11    52.2 2224.16   132.3 2160.85
   168.9 2123.57     177 2117.31     181 2116.28   193.2 2116.17   201.4 2114.69
   213.5  2103.4   221.7 2099.48   237.9    2095   408.6 2095.03   420.7 2099.01
   432.9 2100.24     442 2097.89   445.4 2096.37   469.5 2096.34   479.2 2098.09
   485.7 2102.26   510.1 2109.03   546.7 2107.09   597.2 2108.55   676.9 2114.06
   724.9 2121.57   770.8 2135.57   786.9 2144.51   814.8 2146.71   837.6 2158.18
#Mann= 9 ,-1,0
       0      .1       0     181    .016       0   193.2      .1       0
   221.7    .035       0   420.7      .1       0     442     .04       0
   479.2      .1       0   597.2     .06       0   676.9      .1       0
Bank Sta=221.7,420.7
XS Rating Curve= 0 ,0
Exp/Cntr=0.3,0.1

Type RM Length L Ch R = 1 ,105595  ,511.5,525.3,552.5
BEGIN DESCRIPTION:
channel burned 2.31':
lidar invert = 2095.91
effective invert = 2093.60
END DESCRIPTION:
XS GIS Cut Line= 2
     2225150.606      434632.017 2224970.3977442435600.198162731
#Sta/Elev= 30
       0 2353.03     5.3 2351.46    62.2 2315.26    74.4 2309.11   119.2 2278.17
   126.6 2271.63   151.7 2244.42   172.1 2226.26   220.9 2190.94   249.4 2167.81
   253.5 2162.89   257.5 2155.47   277.9 2134.92     286 2123.77   294.1  2116.8
   298.1 2116.17   306.3 2116.04   311.8 2114.44     329  2101.7   346.1  2093.6
   558.8  2093.6   574.9 2100.67   575.9  2101.1   587.1 2106.15   599.3 2108.71
     640 2109.11   770.2 2110.91   805.8  2115.6   831.2 2121.24   984.8 2170.73
#Mann= 8 ,-1,0
       0      .1       0   298.1    .016       0   306.3      .1       0
     329    .035       0   574.9      .1       0   575.9      .1       0
     640     .06       0   770.2      .1       0
Bank Sta=329,575.9
XS Rating Curve= 0 ,0
Exp/Cntr=0.3,0.1

Type RM Length L Ch R = 1 ,105069  ,463.7,465,470.5
BEGIN DESCRIPTION:
channel burned 1.55':
lidar invert = 2095.5
effective invert = 2093.95
END DESCRIPTION:
XS GIS Cut Line= 2
2224650.88934603434637.4842188542224374.70746776435578.040333534
#Sta/Elev= 30
       0 2266.07    27.7  2242.3    66.4 2214.08   128.9 2163.44   137.3 2156.02
   149.8 2135.32   166.4 2117.55   170.6 2114.98     176 2115.25   188.9 2115.04
   211.4 2100.68   224.8 2093.98     263 2093.95   462.4 2093.95   478.1 2100.94
   491.6  2109.8   516.6 2108.82   554.1 2107.46   616.7 2109.81   729.2 2107.91
   739.2 2109.36   750.1  2111.7   817.3 2142.15   858.5 2155.71   866.8 2160.29
   881.7 2161.18   887.7 2161.07     896 2166.26   908.5  2167.7   980.3  2200.3
#Mann= 10 ,-1,0
       0      .1       0     176    .016       0   188.9      .1       0
   211.4    .035       0   478.1      .1       0   516.6     .05       0
   739.2    .016       0   750.1      .1       0   866.8    .016       0
   881.7      .1       0
#Block Obstruct= 1 ,-1
  503.03   561.7 2128.15
Bank Sta=211.4,478.1
XS Rating Curve= 0 ,0
Exp/Cntr(USF)=0,0
Exp/Cntr=0.3,0.1

Type RM Length L Ch R = 1 ,104604  ,440.3,464,469.8
BEGIN DESCRIPTION:
channel burned 1.62':
lidar invert = 2095.12
effective invert = 2093.50
END DESCRIPTION:
Node Name=N
XS GIS Cut Line= 2
2224277.41223259434305.1645233182223896.11811629 435510.29822068
#Sta/Elev= 30
       0 2351.18    58.8 2314.71    99.8  2286.1   113.3 2273.81   125.9 2269.65
   136.7 2260.22     172 2235.78   239.2 2191.74   271.9 2167.71   310.5 2140.43
   327.3 2119.75   335.6 2114.95   335.6 2114.94   352.4 2114.23     365 2104.87
   377.6 2099.51     386 2093.54   646.1  2093.5   667.1 2100.43   667.1 2100.44
     683 2108.05   691.6 2108.22   808.2 2104.46   875.7 2108.94   973.9 2108.35
  1061.5 2110.14  1078.2 2109.66  1100.5 2117.78  1202.5 2164.43    1264 2193.82
#Mann= 12 ,-1,0
       0      .1       0     172     .12       0   271.9      .1       0
   335.6    .016       0   352.4      .1       0   377.6    .035       0
   667.1      .1       0   691.6     .05       0   973.9    .016       0
  1061.5     .06       0  1100.5     .08       0  1202.5     .12       0
#XS Ineff= 2 , 0
                          879.51         2123.06
Permanent Ineff=
       F       F
Bank Sta=377.6,667.1
XS Rating Curve= 0 ,0
Exp/Cntr=0.3,0.1

Type RM Length L Ch R = 1 ,104140  ,585.1,544.4,406.4
BEGIN DESCRIPTION:
channel burned 1.70':
lidar invert = 2094.7
effective invert = 2093
END DESCRIPTION:
XS GIS Cut Line= 3
2223917.14139532434150.957883707  2223604.725428434809.352184209
2223477.96268605435419.595487996
#Sta/Elev= 30
       0 2345.19      60 2310.04    73.3 2297.69      91 2290.59   113.1 2269.74
     246 2177.46   290.2 2145.09     308 2124.16   321.2 2114.84   338.7 2114.17
   361.1  2101.2   369.9 2093.92   374.4 2093.11     671    2093   685.1 2100.78
   715.3 2109.38     861 2107.48   932.8 2105.39   953.3 2102.33  1006.4 2103.43
  1022.7 2107.98  1131.6 2107.04  1149.4 2107.09    1179 2106.47  1194.3 2108.85
  1210.7 2116.94  1263.8 2152.25  1280.1  2177.5  1288.3  2185.6    1352 2213.66
#Mann= 10 ,-1,0
       0      .1       0     246     .12       0   321.2    .016       0
   338.7      .1       0   361.1    .035       0   685.1      .1       0
     861     .05       0  1131.6    .016       0  1149.4     .08       0
    1179      .1       0
Bank Sta=361.1,685.1
XS Rating Curve= 0 ,0
Exp/Cntr=0.3,0.1

Type RM Length L Ch R = 1 ,103596  ,512.9,502.8,464.6
BEGIN DESCRIPTION:
channel burned 1.06':
lidar invert = 2093.47
interpolated invert = 2092.41
END DESCRIPTION:
XS GIS Cut Line= 2
     2223228.452      433975.8872223138.64717444435353.096801947
#Sta/Elev= 30
       0 2371.09    37.4  2341.4    49.4 2338.53   101.5 2300.85   113.5 2296.89
   165.6 2254.29   185.9 2245.18     314  2139.9     334 2114.87   340.2 2114.02
     350 2113.72     374 2099.62   386.1 2092.41   586.5 2095.32   634.6 2096.61
     645 2092.52   762.9 2092.49   790.1 2098.26   828.7  2107.4   867.3 2107.56
   899.2 2096.72   964.8 2104.23  1003.4 2110.21  1123.7 2106.08  1139.7 2105.88
  1167.8 2107.13  1183.1 2114.11  1251.9 2157.32  1296.1 2190.88  1380.1 2209.39
#Mann= 10 ,-1,0
       0      .1       0   340.2    .016       0     350      .1       0
     374    .035       0   586.5      .1       0   634.6    .035       0
   790.1      .1       0   964.8     .05       0  1123.7    .016       0
  1139.7      .1       0
Bank Sta=374,790.1
XS Rating Curve= 0 ,0
Exp/Cntr=0.3,0.1