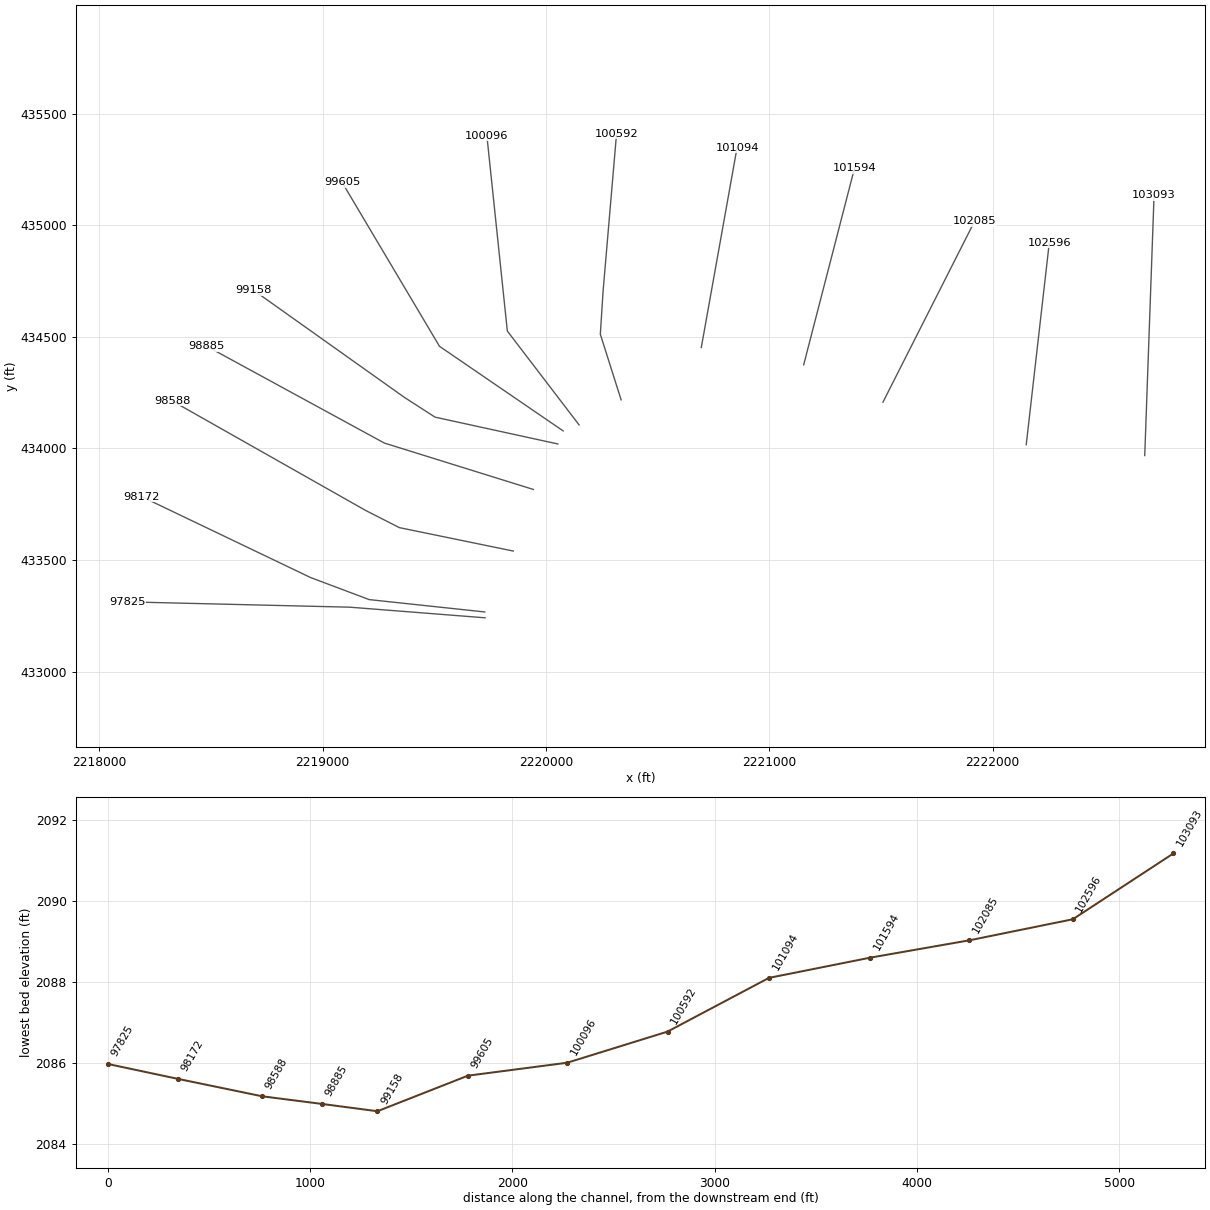
HEC-RAS study GRNBRRRV.prj: GRNBRRRV

--- GRNBRRRV.g01 (geometry) --- (continued)

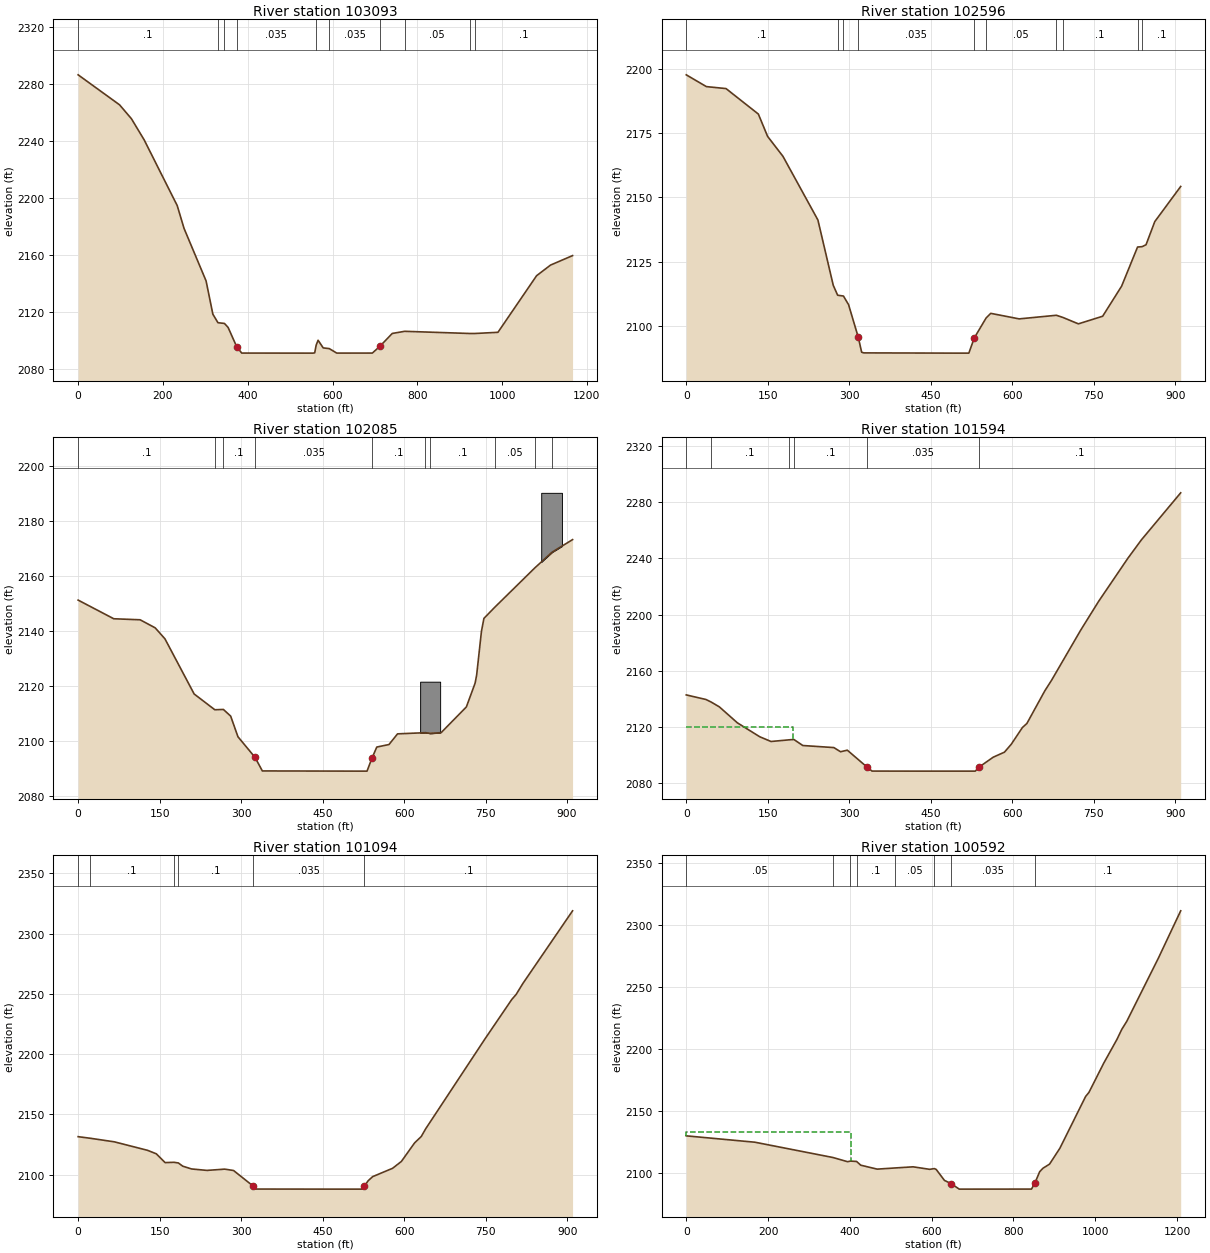
Type RM Length L Ch R = 1 ,103093  ,509.9,497.7,482.3
BEGIN DESCRIPTION:
channel burned 1.44':
lidar invert = 2092.62
interpolated invert = 2091.18
END DESCRIPTION:
XS GIS Cut Line= 2
     2222680.506      433967.5822222722.28194185435133.053255608
#Sta/Elev= 30
       0  2286.6    97.7 2265.54   125.7 2255.77   155.8 2240.89   233.7 2194.78
   249.8 2178.77   301.8 2141.88   317.8 2118.52   329.8 2112.53   345.1 2112.03
   353.8 2109.19   373.8  2095.8   385.8 2091.22   553.8 2091.18     558  2091.4
   561.5 2096.87     566 2100.21     578 2094.87   592.4 2094.34     610  2091.2
     694 2091.22   712.2 2096.11   740.9 2104.99   770.1  2106.5   923.6 2104.97
   936.3 2104.97   990.2  2105.8  1081.4 2145.56  1114.3 2153.01  1166.2 2159.66
#Mann= 10 ,-1,0
       0      .1       0   329.8    .016       0   345.1      .1       0
   373.8    .035       0   561.5      .1       0   592.4    .035       0
   712.2      .1       0   770.1     .05       0   923.6    .016       0
   936.3      .1       0
Bank Sta=373.8,712.2
XS Rating Curve= 0 ,0
Exp/Cntr=0.3,0.1

Type RM Length L Ch R = 1 ,102596  ,571.2,510.7,421.2
BEGIN DESCRIPTION:
channel burned 2.36':
lidar invert = 2092.62
interpolated invert = 2091.18
END DESCRIPTION:
XS GIS Cut Line= 2
     2222150.066       434016.41     2222253.177      434920.558
#Sta/Elev= 30
       0 2197.56      37 2192.99    73.2 2192.22   132.7 2182.33   149.7 2173.67
   177.9 2165.95   242.3 2141.22   270.5 2115.91   278.6 2112.02   289.3 2111.71
   298.7 2108.38   316.6  2095.7   322.8  2089.9   326.9 2089.64   493.8 2089.55
   520.1 2089.55   530.1 2095.44   551.9  2103.2   560.4 2104.99   612.7 2102.84
   681.2 2104.24   692.8 2103.43   721.7 2100.91   766.4 2103.87   801.3 2115.55
   830.6 2130.72   839.1 2130.88   846.2 2131.61   862.3 2140.59     910 2154.23
#Mann= 10 ,-1,0
       0      .1       0   278.6    .016       0   289.3      .1       0
   316.6    .035       0   530.1      .1       0   551.9     .05       0
   681.2    .016       0   692.8      .1       0   830.6    .016       0
   839.1      .1       0
Bank Sta=316.6,530.1
XS Rating Curve= 0 ,0
Exp/Cntr=0.3,0.1

Type RM Length L Ch R = 1 ,102085  ,443.5,491.2,532.8
BEGIN DESCRIPTION:
channel burned 1.51':
lidar invert = 2090.54
interpolated invert = 2089.03
END DESCRIPTION:
XS GIS Cut Line= 2
     2221508.667      434206.624     2221919.575      435018.758
#Sta/Elev= 30
       0 2151.17    65.6 2144.39   114.1 2144.02   141.8  2141.1   159.8  2137.1
   213.6 2117.06   251.6 2111.33   267.4 2111.44   280.8 2109.02   294.2 2101.52
   325.6 2094.04   339.1  2089.1   512.8 2089.03   531.8 2089.03   540.8 2093.68
   549.8 2097.78   572.2 2098.69     588 2102.57   639.4    2103   648.4 2102.73
   668.3 2103.02   714.7 2112.36   730.8    2121   733.6  2123.9   742.5 2139.88
     747 2144.52   766.6  2148.5   840.6 2162.85   872.5 2168.58   910.2 2173.15
#Mann= 10 ,-1,0
       0      .1       0   251.6    .016       0   267.4      .1       0
   325.6    .035       0   540.8      .1       0   639.4    .016       0
   648.4      .1       0   766.6     .05       0   840.6     .06       0
   872.5     .05       0
#Block Obstruct= 2 ,-1
  629.57  666.42 2121.53  852.47  890.62 2190.15
Bank Sta=325.6,540.8
XS Rating Curve= 0 ,0
Exp/Cntr=0.3,0.1

Type RM Length L Ch R = 1 ,101594  ,481.2,500,508.2
BEGIN DESCRIPTION:
channel burned 1.15':
lidar invert = 2089.75
interpolated invert = 2088.60
END DESCRIPTION:
XS GIS Cut Line= 2
      2221153.88      434374.169      2221381.46      435255.252
#Sta/Elev= 30
       0 2142.83    36.2 2139.57    45.6  2137.8    60.9 2134.32      94 2122.99
   135.3 2113.04     156 2109.69     189 2110.86   198.1  2111.1   214.5 2106.82
   271.6 2105.35     284  2102.4   296.4 2103.51   332.7 2091.48   341.9 2088.63
   424.5  2088.6   531.9  2088.6   539.5 2091.63     565 2098.52   585.6 2102.09
     598 2107.64   618.7 2119.64   626.9  2122.5     660 2145.78   672.4 2153.29
   726.1    2189   759.1 2209.48   812.8 2240.06   837.6 2253.11     910 2286.61
#Mann= 6 ,-1,0
       0     .06       0    45.6      .1       0     189    .016       0
   198.1      .1       0   332.7    .035       0   539.5      .1       0
#XS Ineff= 2 , 0
           197.3    2120
Permanent Ineff=
       F       F
Bank Sta=332.7,539.5
XS Rating Curve= 0 ,0
Exp/Cntr=0.3,0.1

Type RM Length L Ch R = 1 ,101094  ,478.2,501.7,511.5
BEGIN DESCRIPTION:
channel burned 1.49':
lidar invert = 2089.59
interpolated invert = 2088.10
END DESCRIPTION:
Node Name=M
XS GIS Cut Line= 2
     2220695.534      434451.546     2220855.706      435347.339
#Sta/Elev= 30
       0 2131.58    22.6 2130.26    66.7  2127.3   127.6 2120.29   143.9 2117.37
   160.1 2110.09   176.4 2110.34   184.5 2109.79   192.6 2107.11   208.9 2104.81
   237.3 2103.62   269.8 2104.67   286.1 2103.53   321.8 2090.74   326.7 2088.16
   464.9  2088.1   521.8  2088.1  526.812090.669     534 2095.14   542.1 2098.46
   578.7 2105.35   594.9 2111.04   619.3 2126.45   631.5  2131.7   639.5    2138
   749.3 2212.98   798.2 2245.37   806.2 2249.52   818.4 2258.49     910 2318.81
#Mann= 6 ,-1,0
       0     .05       0    22.6      .1       0   176.4    .016       0
   184.5      .1       0   321.8    .035       0  526.81      .1       0
Bank Sta=321.8,526.81
XS Rating Curve= 0 ,0
Exp/Cntr=0.3,0.1

Type RM Length L Ch R = 1 ,100592  ,447.8,496.1,520.4
BEGIN DESCRIPTION:
channel burned 2.67':
lidar invert = 2089.44
interpolated invert = 2086.77
END DESCRIPTION:
XS GIS Cut Line= 4
2220336.68085481434217.2118195642220243.61541594434510.869688254
2220255.94073275434704.423227252     2220316.118      435408.683
#Sta/Elev= 30
       0 2129.72   167.8 2124.59   358.5 2112.27   394.5 2108.87   401.2 2109.38
   416.3 2109.09   426.6 2106.08   466.7 2102.89   510.3 2103.83   554.7 2104.75
   595.1 2102.72   606.5 2103.32   611.1 2102.64   631.2 2093.81   647.2 2091.26
   667.4 2086.77     844  2086.8     852 2091.43   864.1 2100.85   872.1 2103.61
   888.2 2106.94   913.5 2119.77   976.3 2161.44   984.5 2164.76  1020.6 2188.27
  1052.8 2207.38  1064.8 2215.58  1076.8 2221.95  1153.9 2272.74  1208.8 2311.12
#Mann= 8 ,-1,0
       0     .05       0   358.5      .1       0   401.2    .016       0
   416.3      .1       0   510.3     .05       0   606.5      .1       0
   647.2    .035       0     852      .1       0
#XS Ineff= 2 , 0
          403.04 2132.88
Permanent Ineff=
       F       F
Bank Sta=647.2,852
XS Rating Curve= 0 ,0
Exp/Cntr=0.3,0.1

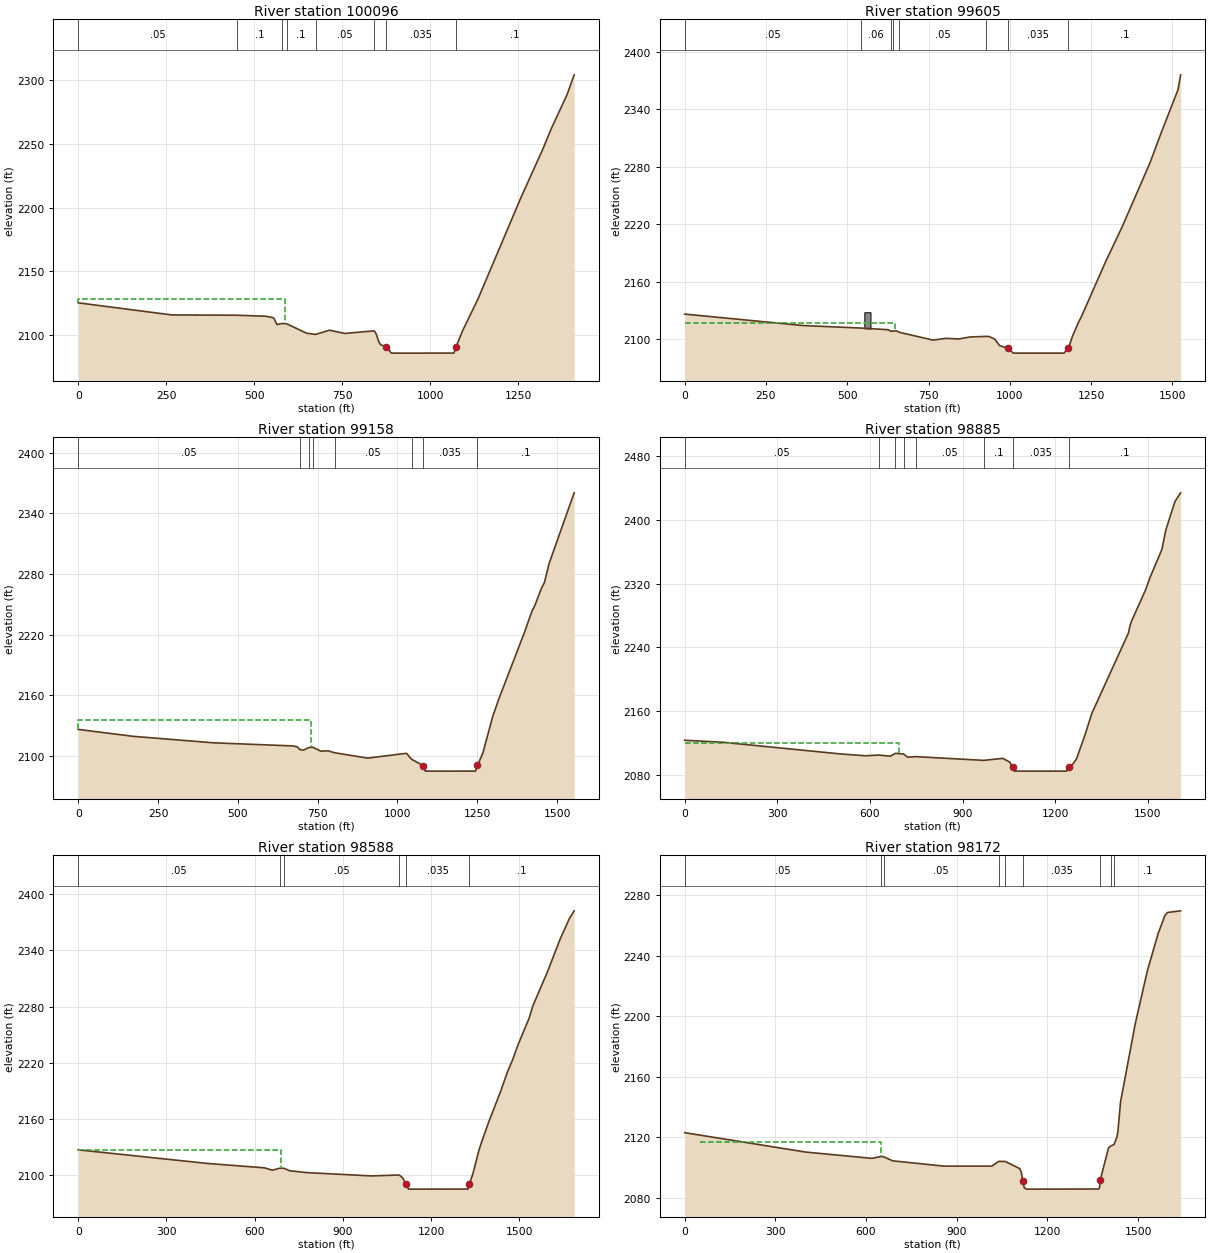
Type RM Length L Ch R = 1 ,100096  ,367.3,490.7,544.9
BEGIN DESCRIPTION:
channel burned 3.28':
lidar invert = 2089.28
interpolated invert = 2086
END DESCRIPTION:
XS GIS Cut Line= 3
2220148.47073339434104.9124136582219827.34982483434525.451199771
     2219735.714      435401.116
#Sta/Elev= 30
       0 2125.41   265.8 2115.93   451.3 2115.69   532.9  2114.9     553 2113.87
     557 2112.88     565 2108.39   579.1 2109.21   592.6 2108.98   649.5 2101.57
   674.9 2100.66   713.8 2103.97   757.5 2101.44   841.2 2103.44   846.6 2101.29
   854.6 2094.77   858.6 2092.82874.86792090.909   878.7 2090.43   889.1 2086.21
   894.8    2086  1067.8 2086.031074.2672091.167  1091.9 2103.19  1136.2 2128.38
  1257.4 2207.24  1321.2 2246.22  1345.3 2262.31  1389.5 2288.53  1409.6 2304.04
#Mann= 8 ,-1,0
       0     .05       0   451.3      .1       0   579.1    .016       0
   592.6      .1       0   674.9     .05       0   841.2      .1       0
874.8679    .035       01074.267      .1       0
#XS Ineff= 2 , 0
          586.82  2128.5
Permanent Ineff=
       F       F
Bank Sta=874.8679,1074.267
XS Rating Curve= 0 ,0
Exp/Cntr=0.3,0.1

Type RM Length L Ch R = 1 ,99605   ,324.1,447.3,494.3
BEGIN DESCRIPTION:
channel burned 3.48':
lidar invert = 2089.16
interpolated invert = 2085.68
END DESCRIPTION:
XS GIS Cut Line= 3
2220077.14771185434077.9737911192219523.56835713434457.159241916
     2219087.686      435191.653
#Sta/Elev= 30
       0 2126.43   364.8 2114.45   541.1 2111.86   626.6 2110.12   633.2 2108.52
   641.8 2108.67   650.9 2108.95   660.6 2107.37   763.9 2099.28     803 2101.11
   842.8 2100.46   877.8 2102.56   926.8 2103.12   936.2 2103.03   953.7 2100.23
   968.3 2093.57993.53342090.832  1010.6 2085.68  1166.8 2085.681178.7332090.951
  1184.3 2094.94    1192 2102.84  1210.6 2117.49  1219.9 2123.67  1295.2 2181.63
  1344.9 2217.16  1430.1 2283.61  1466.4 2316.57  1517.1 2360.58  1525.1  2376.1
#Mann= 8 ,-1,0
       0     .05       0   541.1     .06       0   633.2    .016       0
   641.8      .1       0   660.6     .05       0   926.8      .1       0
993.5334    .035       01178.733      .1       0
#XS Ineff= 2 , 0
          648.01 2116.98
Permanent Ineff=
       F       F
#Block Obstruct= 1 ,-1
  552.36  571.48 2128.34
Bank Sta=993.5334,1178.733
XS Rating Curve= 0 ,0
Exp/Cntr=0.3,0.1

Type RM Length L Ch R = 1 ,99158   ,233,273.2,286.5
BEGIN DESCRIPTION:
channel burned 4.20':
lidar invert = 2089
effective invert = 2084.80
END DESCRIPTION:
XS GIS Cut Line= 4
2220053.48160136 434019.455572682219503.74137336434139.643687798
2219365.79038554434228.7344173662218692.29604644 434707.58433717
#Sta/Elev= 30
       0 2126.15   170.5 2119.31   423.1 2112.85   671.7 2109.77     686  2108.9
   693.7 2106.24   705.1 2105.61   722.6 2108.12   734.2 2108.52     760 2104.59
   782.9 2104.88     803    2103   906.3 2097.72  1028.3 2102.44    1044 2096.58
1080.8582090.209  1086.7  2084.9  1092.1  2084.8  1244.3 2084.831250.5562090.397
  1267.7 2103.06  1298.3 2138.97  1317.9 2156.69  1396.8 2221.52  1420.9 2242.97
  1430.8 2249.26  1450.4  2265.6  1459.9 2271.34  1474.9 2290.48  1553.3 2360.45
#Mann= 8 ,-1,0
       0     .05       0   693.7      .1       0   722.6    .016       0
   734.2      .1       0     803     .05       0    1044      .1       0
1080.858    .035       01250.556      .1       0
#XS Ineff= 2 , 0
          730.14 2135.06
Permanent Ineff=
       F       F
Bank Sta=1080.858,1250.556
XS Rating Curve= 0 ,0
Exp/Cntr=0.3,0.1

Type RM Length L Ch R = 1 ,98885   ,302.9,296.8,294.9
BEGIN DESCRIPTION:
channel burned 3.96':
lidar invert = 2088.94
interpolated invert = 2084.98
END DESCRIPTION:
XS GIS Cut Line= 3
2219943.60514723433815.7509858172219277.02543344434023.453360405
2218480.02794955434458.179260705
#Sta/Elev= 30
       0 2123.73   124.8 2121.11   506.4 2106.47     586 2104.22   627.9 2105.16
   665.6 2103.73   682.3 2107.26   708.9 2106.46   721.9 2102.46   749.3 2103.14
   968.4 2098.47  1030.3 2100.97  1052.6 2096.27  1062.8 2090.04  1068.2 2084.99
  1236.8 2084.98 1243.37 2089.98  1257.3 2093.92  1268.7 2100.25  1295.6 2129.53
  1318.8 2157.66  1436.9 2257.98  1441.8 2266.75  1446.4 2272.38    1492 2311.74
  1507.9 2328.64  1545.5 2363.03    1558 2387.21  1587.6    2423    1606 2433.88
#Mann= 8 ,-1,0
       0     .05       0   627.9      .1       0   682.3    .016       0
   708.9      .1       0   749.3     .05       0   968.4      .1       0
  1062.8    .035       0 1243.37      .1       0
#XS Ineff= 2 , 0
           694.9    2120
Permanent Ineff=
       F       F
Bank Sta=1062.8,1243.37
XS Rating Curve= 0 ,0
Exp/Cntr(USF)=0,0
Exp/Cntr=0.3,0.1

Type RM Length L Ch R = 1 ,98588   ,388.4,415.4,423.2
BEGIN DESCRIPTION:
channel burned 3.67':
lidar invert = 2088.84
interpolated invert = 2085.17
END DESCRIPTION:
XS GIS Cut Line= 4
2219854.32282945433539.653281641 2219343.9079565 433644.67568719
2219193.21385363433721.539718248     2218326.332      434212.824
#Sta/Elev= 30
       0 2127.09     440 2112.55   633.1  2107.9     660 2105.36   686.9  2107.6
   700.7 2107.32   719.1 2104.77   778.8 2102.78   997.8 2099.25  1091.5 2100.25
  1103.3 2097.33  1113.4 2091.08  1123.7 2085.17  1324.6 2085.23  1325.9 2085.35
  1330.5 2090.97  1342.2 2101.41  1362.7 2126.36  1371.9 2135.42  1395.3 2156.02
  1436.2 2189.09  1459.6 2209.97  1477.7 2223.41  1496.1 2239.39    1533 2267.11
  1546.6 2280.99    1596 2317.08  1638.6 2351.62  1670.2 2373.72  1686.7 2382.13
#Mann= 6 ,-1,0
       0     .05       0   686.9    .016       0   700.7     .05       0
  1091.5     .08       0  1113.4    .035       0  1330.5      .1       0
#XS Ineff= 2 , 0
          689.58 2127.23
Permanent Ineff=
       F       F
Bank Sta=1113.4,1330.5
XS Rating Curve= 0 ,0
Exp/Cntr=0.3,0.1

Type RM Length L Ch R = 1 ,98172   ,171.3,347.8,405.9
BEGIN DESCRIPTION:
channel burned 3.09':
lidar invert = 2088.69
interpolated invert - 2085.60
END DESCRIPTION:
Node Name=L
XS GIS Cut Line= 4
2219726.31541044433266.7872405022219209.05124991433322.175573622
2218946.61905801433421.0053985992218189.03838433433784.108580394
#Sta/Elev= 30
       0 2122.97   400.2 2110.13   619.5 2105.97   649.4 2107.19   657.9 2107.04
   687.9 2104.34   856.6 2100.84  1016.3 2100.84  1038.4 2103.94  1060.2 2103.94
  1108.5 2099.17  1113.9 2096.621118.3142091.104  1123.5 2086.45  1131.6  2085.6
  1369.3 2085.68  1372.3 2086.341374.6842091.543  1402.2 2112.87  1410.3 2114.29
  1420.3 2115.05  1430.4 2120.33  1433.2 2123.79  1442.1 2143.45  1490.9 2195.35
  1530.8  2230.2  1566.3 2254.72  1588.5 2266.62  1597.3 2268.72  1640.7 2269.82
#Mann= 9 ,-1,0
       0     .05       0   649.4    .016       0   657.9     .05       0
  1038.4    .016       0  1060.2      .1       01118.314    .035       0
1374.684      .1       0  1410.3    .016       0  1420.3      .1       0
#XS Ineff= 1 ,-1
   51.72  649.01 2116.63
Permanent Ineff=
       F
Bank Sta=1118.314,1374.684
XS Rating Curve= 0 ,0
Exp/Cntr=0.3,0.1

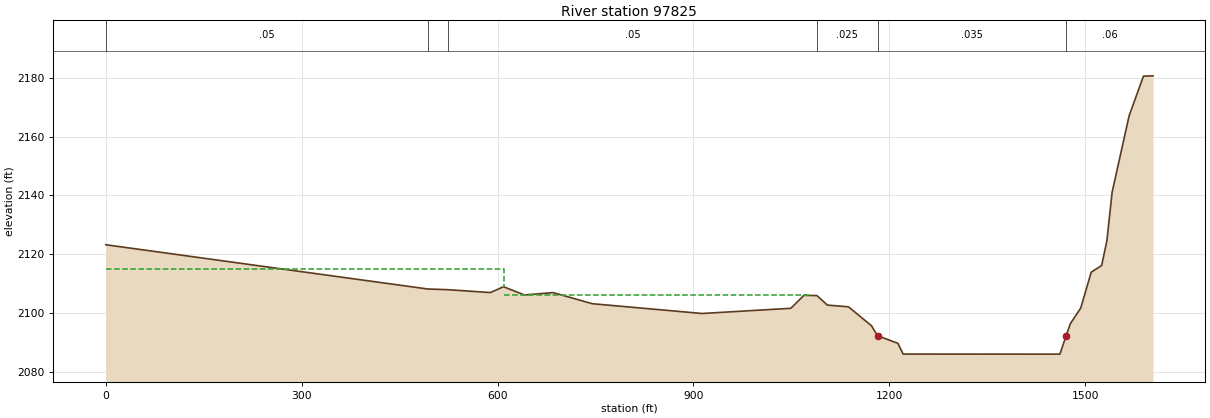
Type RM Length L Ch R = 1 ,97825   ,90,180.8,229.1
BEGIN DESCRIPTION:
xs 4 - channel burned 2.62':
lidar invert = 2088.59
interpolated invert = 2085.97
END DESCRIPTION:
XS GIS Cut Line= 3
2219727.47164228433240.6192160692219121.31278266433288.245983611
2218125.48037042433312.059367382
#Sta/Elev= 30
       0 2123.22   492.8 2108.16   524.4 2107.91   589.1 2106.94   609.2 2108.92
   641.2 2106.13   685.2 2106.92   745.2 2103.14   913.3 2099.81  1049.3 2101.58
  1069.3 2105.99  1089.3 2105.91  1105.3 2102.67  1137.6 2102.08  1172.8 2095.64
  1182.1 2092.24  1213.3 2089.65  1221.3 2085.99  1411.6 2085.97  1461.4 2085.97
 1470.88 2092.16  1477.4 2096.33  1493.4 2101.69  1509.4 2113.88  1525.4 2116.17
  1533.4 2124.58  1541.4 2141.09  1567.4  2167.1  1589.4 2180.64  1604.1 2180.75
#Mann= 6 ,-1,0
       0     .05       0   492.8      .1       0   524.4     .05       0
  1089.3    .025       0  1182.1    .035       0 1470.88     .06       0
#XS Ineff= 2 ,-1
       0   609.2    2115   609.2 1079.36 2106.01
Permanent Ineff=
       F       F
Bank Sta=1182.1,1470.88
XS Rating Curve= 0 ,0
Exp/Cntr(USF)=0,0
Exp/Cntr=0.5,0.3