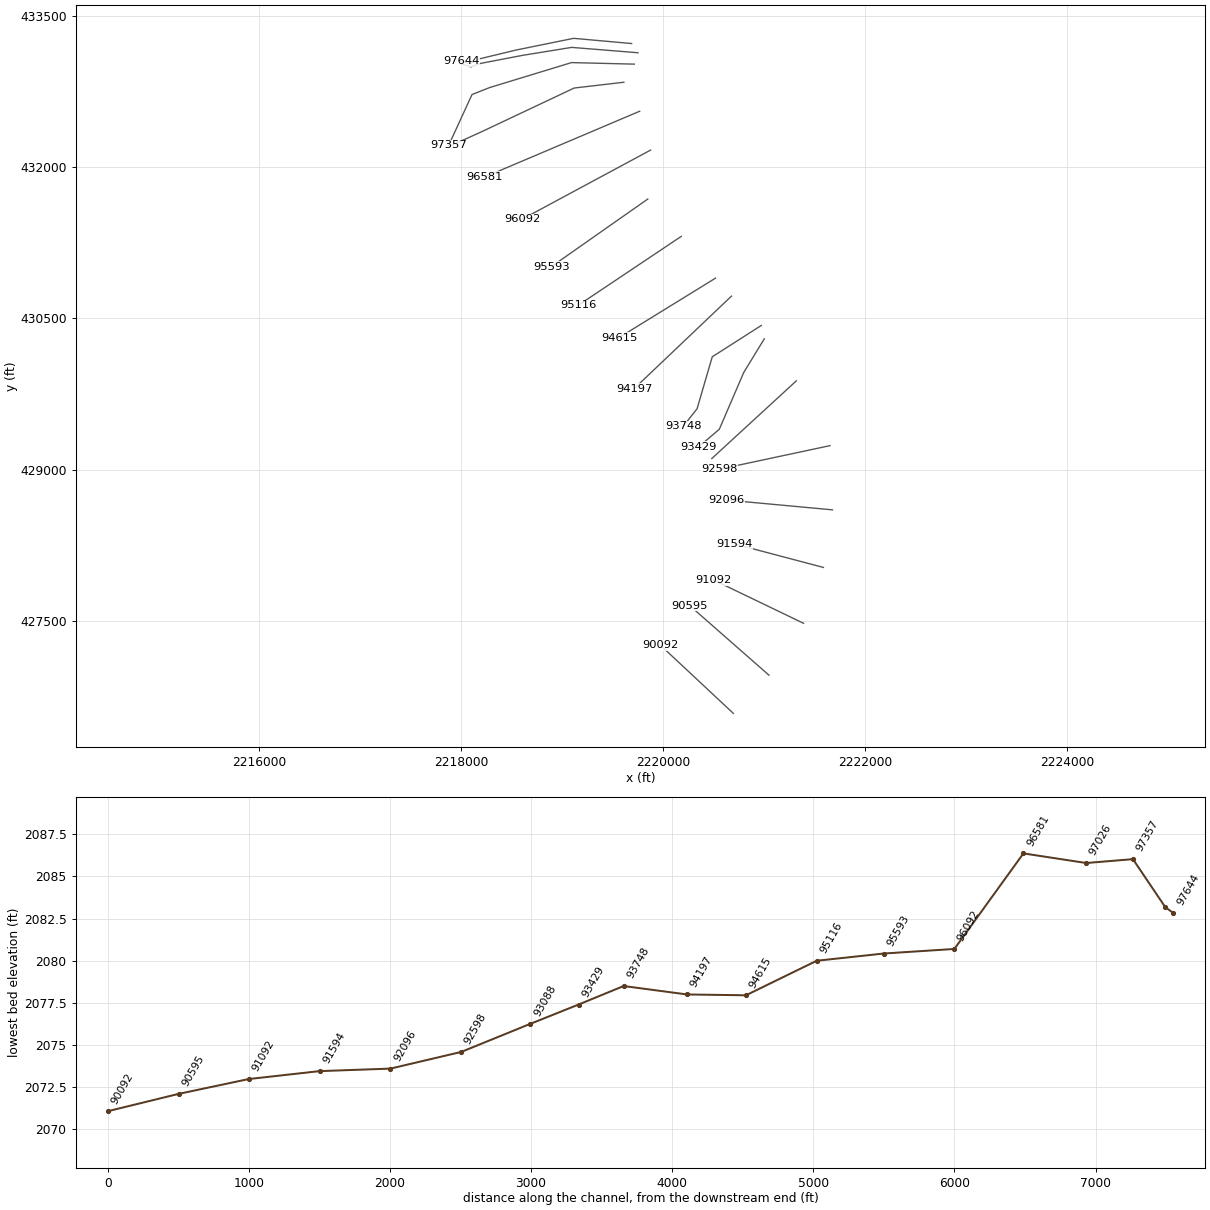
HEC-RAS study GRNBRRRV.prj: GRNBRRRV

--- GRNBRRRV.g01 (geometry) --- (continued)

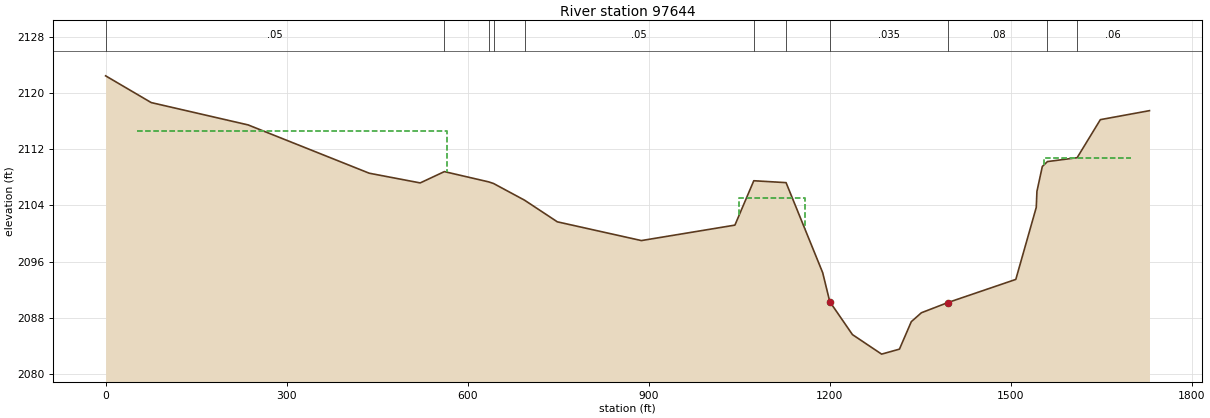
Type RM Length L Ch R = 1 ,97644   ,77.1,57.8,49
BEGIN DESCRIPTION:
structure xs 3
channel burned per surveyed cross section data
END DESCRIPTION:
XS GIS Cut Line= 6
2219687.45100188433223.6732262212219113.30402793433275.174782024
2218542.91190882433159.0438587212218170.17371201433069.218190435
2218086.42160392433023.918308074 2217997.9676543433049.196700552
#Sta/Elev= 30
       0 2122.46    75.6 2118.65   236.2 2115.47     437 2108.59   521.4 2107.21
   561.5 2108.82   634.8 2107.36   642.9 2107.13   694.4 2104.75   748.7 2101.67
     888    2099    1043  2101.2  1074.3 2107.52  1127.8 2107.25 1188.48 2094.43
 1200.25  2090.3 1237.81 2085.61 1286.15 2082.83  1315.7 2083.54 1335.35 2087.45
 1352.07 2088.72 1395.52 2090.16 1508.57 2093.47 1542.45 2103.72  1543.6 2106.01
  1552.5 2109.55    1561 2110.25  1610.2  2110.8  1648.7 2116.22  1730.1  2117.5
#Mann= 11 ,-1,0
       0     .05       0   561.5      .1       0   634.8    .016       0
   642.9      .1       0   694.4     .05       0  1074.3    .016       0
  1127.8     .08       0 1200.25    .035       0 1395.52     .08       0
    1561    .016       0  1610.2     .06       0
#XS Ineff= 3 ,-1
   52.73     566 2114.65    1050    1159 2105.11  1555.5    1700 2110.71
Permanent Ineff=
       F       F       F
Bank Sta=1200.25,1395.52
XS Rating Curve= 0 ,0
Exp/Cntr=0.5,0.3

Type RM Length L Ch R = 3 ,97621   ,,,
BEGIN DESCRIPTION:
Bridge No.: 54075GRL040 Buckeye Road
JV notes: road deck updated per surveyed XS data points
channel burned per surveyed cross sections
structure opening based on survey data, photos, and aerial imagery
surveyed inverts are 3-6' below inverts from lidar:
 surveyed invert US is 2082.83
 surveyed invert DS is 2084.39
END DESCRIPTION:
Bridge Culvert--1,0,-1,-1, 0
Deck Dist Width WeirC Skew NumUp NumDn MinLoCord MaxHiCord MaxSubmerge Is_Ogee
12,24,2.6,0, 358, 352, , , 0.98, 0, 0,0,,
     -16   -10.5     1.6     5.6     9.6    13.6    17.6    25.7    33.7    34.6
    36.6    37.7    41.7    45.7    49.7    53.8    57.8    58.8    60.9    66.2
    69.9    73.8    77.8    81.9    84.7    85.9    89.9    93.9    97.9   101.9
   110.6     114     118     122     126     130   134.1   142.1   143.8   151.2
   154.1   162.2   170.2   174.2   178.2   182.2   186.2   190.3   195.6   201.5
   206.3   210.3   217.8   222.4   226.4   230.4   232.2   238.4     241   242.5
   245.4   247.3     251   254.5   262.5     263   266.5   273.2   278.6   282.6
     288   291.7   295.4   299.1   302.8   304.1   306.9   314.7   318.7   320.1
   328.7   330.8   334.8   336.1   338.8   342.8   347.1   350.8   354.5   358.9
   361.9   362.9   370.9   374.9   377.2   381.6     386   387.8   391.5   394.8
   398.9   402.6   407.1     410   415.1   416.8   423.1   427.1   431.1   435.9
   439.2   443.1   447.5   450.7   454.4   456.3     458   459.3   465.1   467.3
   469.1   472.8   473.9   480.2   483.9   491.4     495   499.4   502.4   506.1
   507.4   511.4   515.5   522.2   524.6   527.5     532   537.4   539.8   543.6
   547.6   551.6   559.6   565.2   567.6   571.7   575.7   579.7   581.2   584.9
   587.7   591.7   592.3   595.7   599.7   603.4   603.8   607.1   607.8   608.6
   610.8   611.8   612.9   615.8   617.3   618.3   619.8   621.7   623.8   625.7
   627.9   629.4   631.9   635.9   639.8   643.2   644.1   646.6   650.1   652.2
   656.9   660.4   664.4   665.4   668.5   670.6   674.1   676.6   680.7   684.4
   684.8   685.4   687.8   692.9     697   698.1   700.4     701   705.1   709.2
   711.8   713.3   717.3   721.4   725.4     729   733.6   737.7   741.7   746.1
   749.5   756.4     758   760.4   762.1   774.3   778.4   783.8   786.5   790.4
   794.1   797.6   798.7   802.8   804.4   810.9   814.7   818.1   820.3   823.1
   827.2   831.2   835.2   835.3   840.3   842.2   843.5   847.5     849   851.6
   855.3   859.7   865.3   866.2   867.9   871.9   876.5   880.3   884.1   886.7
   892.3   895.3   900.3   904.5   908.6   912.6   916.7   920.3   922.6   925.3
   928.9     937   941.1   945.1   948.5   953.3   957.4   958.8   960.3   965.5
   965.6   969.1   972.5   975.3   977.7   979.4   981.8   982.8   985.3   989.6
   993.1   998.1  1002.1  1006.8  1010.3  1014.3  1018.4  1020.5    1024  1026.5
  1030.3  1031.9  1035.3  1037.7  1040.3  1042.8  1046.9    1048  1050.3  1051.4
  1054.8  1058.3  1063.2  1065.1  1067.2  1068.5  1070.3  1071.3  1075.4  1079.4
  1082.3  1083.5  1085.7  1089.1  1091.6    1092 1127.98 1171.08 1172.01 1172.01
 1286.93 1357.62 1459.35 1543.26 1543.26 1547.42 1589.77 1640.62  1642.6  1643.4
  1646.5  1650.7  1652.3  1655.5  1658.7    1662  1663.2  1667.4  1671.7  1675.7
  1678.1  1679.9  1686.4  1688.2  1692.4  1696.5  1700.7  1700.7  1704.9  1707.2
  1713.2  1716.8  1720.1  1721.5  1723.3  1726.5  1729.4    1733
 2123.27 2123.06 2122.56 2122.39 2122.17 2121.87 2121.61 2120.98 2120.29 2120.23
 2120.16 2120.08 2119.91 2119.67 2119.48 2119.37 2119.33 2119.34 2119.31 2119.34
 2119.35 2119.33 2119.28 2119.28 2119.23 2119.22 2119.11 2118.95 2118.89 2118.75
 2118.54 2118.48  2118.5 2118.43 2118.23 2117.94 2117.76 2117.67 2117.63 2117.51
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                                                                  2104.3  2104.3
2104.9412105.3352105.902 2106.37 2106.37
    63.6    71.7    79.7    80.6    82.6    83.7    87.7    91.7    95.7    99.8
   103.8   104.8   106.9   112.2   115.9   119.8   123.8   127.9   130.7   131.9
   135.9   139.9   143.9   147.9   156.6     160     164     168     172     176
   180.1   188.1   189.8   197.2   200.1   208.2   216.2   220.2   224.2   228.2
   232.2   236.3   241.6   247.5   252.3   256.3   263.8   268.4   272.4   276.4
   278.2   284.4     287   288.5   291.4   293.3     297   300.5   308.5     309
   312.5   319.2   324.6   328.6     334   337.7   341.4   345.1   348.8   350.1
   352.9   360.7   364.7   366.1   374.7   376.8   380.8   382.1   384.8   388.8
   393.1   396.8   400.5   404.9   407.9   408.9   416.9   420.9   423.2   427.6
     432   433.8   437.5   440.8   444.9   448.6   453.1     456   461.1   462.8
   469.1   473.1   477.1   481.9   485.2   489.1   493.5   496.7   500.4   502.3
     504   505.3   511.1   513.3   515.1   518.8   519.9   526.2   529.9   537.4
     541   545.4   548.4   552.1   553.4   557.4   561.5   568.2   570.6   573.5
     578   583.4   585.8   589.6   593.6   597.6   605.6   611.2   613.6   617.7
   621.7   625.7   627.2   630.9   633.7   637.7   638.3   641.7   645.7   649.4
   649.8   653.1   653.8   654.6   656.8   657.8   658.9   661.8   663.3   664.3
   665.8   667.7   669.8   671.7   673.9   675.4   677.9   681.9   685.8   689.2
   690.1   692.6   696.1   698.2   702.9   706.4   710.4   711.4   714.5   716.6
   720.1   722.6   726.7   730.4   730.8   731.4   733.8   738.9     743   744.1
   746.4     747   751.1   755.2   757.8   759.3   763.3   767.4   771.4     775
   779.6   783.7   787.7   792.1   795.5   802.4     804   806.4   808.1   820.3
   824.4   829.8   832.5   836.4   840.1   843.6   844.7   848.8   850.4   856.9
   860.7   864.1   866.3   869.1   873.2   877.2   881.2   881.3   886.3   888.2
   889.5   893.5     895   897.6   901.3   905.7   911.3   912.2   913.9   917.9
   922.5   926.3   930.1   932.7   938.3   941.3   946.3   950.5   954.6   958.6
   962.7   966.3   968.6   971.3   974.9     983   987.1   991.1   994.5   999.3
  1003.4  1004.8  1006.3  1011.5  1011.6  1015.1  1018.5  1021.3  1023.7  1025.4
  1027.8  1028.8  1031.3  1035.6  1039.1  1044.1  1048.1  1052.8  1056.3  1060.3
  1064.4  1066.5    1070  1072.5  1076.3  1077.9  1081.3  1083.7  1086.3  1088.8
  1092.9    1094  1096.3  1097.4  1100.8  1104.3  1109.2  1111.1  1113.2  1114.5
  1116.3  1117.3  1121.4  1125.4  1128.3  1129.5  1131.7  1135.1  1137.6    1138
 1173.98 1217.08 1218.01 1218.01 1332.93 1403.62 1505.35 1589.26 1589.26 1593.42
 1635.77 1686.62  1688.6  1689.4  1692.5  1696.7  1698.3  1701.5  1704.7    1708
  1709.2  1713.4  1717.7  1721.7  1724.1  1725.9  1732.4  1734.2  1738.4  1742.5
  1746.7  1746.7  1750.9  1753.2  1759.2  1762.8  1766.1  1767.5  1769.3  1772.5
  1775.4  1781.1
 2121.61 2120.98 2120.29 2120.23 2120.16 2120.08 2119.91 2119.67 2119.48 2119.37
 2119.33 2119.34 2119.31 2119.34 2119.35 2119.33 2119.28 2119.28 2119.23 2119.22
 2119.11 2118.95 2118.89 2118.75 2118.54 2118.48  2118.5 2118.43 2118.23 2117.94
 2117.76 2117.67 2117.63 2117.51 2117.45 2117.44 2117.35 2117.28 2117.36  2117.4
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                  2104.3  2104.32104.9412105.3352105.902 2106.37 2106.37
Pier Skew, UpSta & Num, DnSta & Num=  ,1373.62, 2 ,1406.53, 2 , 0 , 0 , 0 ,,
     2.5     2.5
       0  2106.5
     2.5     2.5
       0  2106.5
BR Coef=-1 ,-1 , 0 ,, 0 ,,,0.8,0,1.33,0,
WSPro=,,,, 1 ,,,, 0 ,,,, 0 ,,,,-1 ,-1 ,-1 , 0 , 0 , 0 , 0 , 0
BR U #Sta/Elev= 344
       0 2122.46    11.3 2122.09    19.4 2121.75    27.4 2121.23    43.4 2120.02
      56 2119.47    67.5 2119.11    72.5 2118.78    75.6 2118.65    79.6  2118.6
    83.6 2118.64    91.6 2118.48   103.4 2118.04   111.7 2117.91   127.8 2117.28
   147.9 2116.79     152 2116.78   163.9 2116.54     176 2116.49     184 2116.56
   187.2 2116.52   199.7 2116.07   212.1 2115.72   220.2 2115.69   228.2 2115.52
   232.2 2115.56   236.2 2115.47   240.3 2115.28   244.3 2115.03   256.3 2114.55
   260.3 2114.46   266.1 2114.27   272.4 2114.01   304.5 2112.45   319.6 2111.85
   328.6 2111.63   336.6 2111.53   339.8 2111.35   348.7 2110.97     375 2110.13
     384 2109.97   388.8 2109.81   406.1 2109.53   412.3 2109.36   413.5 2109.32
   417.2 2109.16     429 2108.94   431.9 2108.84     437 2108.59   453.1 2108.38
   465.1 2108.12   476.1 2107.95   483.5 2107.88   489.2 2107.76   497.3  2107.7
   504.9 2107.55   509.3 2107.41     513 2107.41   516.7 2107.32   521.4 2107.21
   538.8 2107.33   545.5 2107.48   546.2 2107.53   554.1 2107.92   557.2 2108.11
   557.5 2108.13   557.8 2108.19   561.5 2108.82   565.5 2109.39   566.7 2109.45
   568.3 2109.51   569.6 2109.58   577.6 2109.27   581.7 2109.18   614.3 2107.02
   619.8 2107.15   634.8 2107.36   642.9 2107.13   643.5 2107.08   646.9 2106.76
     647 2106.75   647.1 2106.75   655.2 2106.94   657.1 2106.87   657.4 2106.86
   659.2 2106.79   660.5 2106.69   662.5 2106.56   663.3 2106.49   667.6  2106.3
   671.5 2105.95   675.6 2105.78   679.7 2105.96   687.6 2105.24   691.9 2105.01
   693.2 2104.87   694.4 2104.75     696 2104.59   697.8 2104.39   698.4 2104.33
   700.1 2104.14   706.8 2103.66   708.6 2103.52   711.4 2103.23   712.3 2103.13
   726.8 2102.49   748.7 2101.67   755.5 2101.54   762.2 2101.51   773.5 2101.26
   775.2 2101.24   775.8 2101.23   777.6  2101.2   779.2 2101.19   780.4 2101.18
   781.7 2101.16   782.6 2101.16   785.5 2101.16   785.8 2101.16   814.4 2100.41
   833.5 2100.03   855.2 2099.42   862.4 2099.27   863.3 2099.24     864 2099.24
   872.6  2099.1   874.2 2099.04   875.6    2099     888    2099   891.1 2099.05
   903.4 2099.15   913.6 2099.29   914.9 2099.31   916.4 2099.33   924.6 2099.63
   940.9 2100.02   949.5 2100.16   969.1 2100.34   973.6 2100.28   977.6 2100.31
   981.7 2100.31   982.7  2100.3   985.4 2100.26   986.1 2100.26   987.4 2100.28
   989.5  2100.3   992.9 2100.39   998.1 2100.48  1000.8 2100.53  1006.2 2100.72
  1006.4 2100.73  1009.8 2100.74    1011 2100.76  1018.5  2100.9    1020 2100.91
  1022.5 2100.95  1030.7 2100.95  1033.6    2101  1034.8 2101.01    1037 2101.06
  1038.9  2101.1  1040.4 2101.14  1041.8 2101.17    1043  2101.2  1046.9 2101.43
    1047 2101.44  1047.1 2101.45  1047.6 2101.51  1050.5 2101.84  1051.1  2101.9
    1052 2102.09  1055.2 2102.78  1060.7 2104.29  1062.3 2104.74  1063.4 2105.05
  1064.1  2105.2  1067.5    2106  1067.5 2106.01  1067.6 2106.05  1070.9 2106.83
  1071.5 2106.98  1072.5 2107.19  1074.3 2107.52  1075.6 2107.81  1077.7 2107.99
  1079.7 2108.19  1082.8  2108.3  1083.8 2108.33  1084.4 2108.34  1087.8 2108.44
  1087.9 2108.44    1093 2108.41  1094.6 2108.41    1096 2108.41    1098 2108.38
  1098.2 2108.38  1100.1 2108.35  1101.4 2108.33  1103.3 2108.32  1104.2  2108.3
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BR U #Mann= 11
       0     .05   561.5      .1   634.8    .016   642.9      .1   694.4     .05
  1074.3    .016  1127.8     .08 1200.25     .03 1395.52     .08    1561    .016
  1610.2     .06
BR D #Sta/Elev= 340
       0 2123.69     6.5 2123.21    26.5  2122.2    42.6 2122.13    62.5 2121.87
    66.6 2121.77    74.7 2121.29    90.7 2120.92    98.8 2120.79   122.8  2120.9
   138.9 2120.61   150.9 2120.68     159 2120.81     167 2120.78     175 2120.61
     187 2120.57   198.2 2120.23   203.1 2120.01   219.1 2119.59   223.2 2119.58
   231.2 2119.82   239.2 2119.58     255 2118.93   259.3 2118.87   271.3 2118.36
   279.3 2118.14   292.6 2118.01   311.5 2117.23   315.5 2117.13   319.5 2117.11
   363.6 2115.61   379.7 2115.43   395.7 2115.07   400.3 2114.89   407.7 2114.78
   411.8 2114.67     430 2114.46   447.1 2113.95   459.7 2113.65   496.1 2113.06
   507.9    2113   520.1 2112.79   528.2  2112.5   532.2 2112.45     545 2112.44
   547.6 2112.39   548.2 2112.38     552 2112.35   552.5 2112.34   556.2 2112.22
   556.3 2112.22   560.3 2112.15   567.3 2112.14   568.3 2112.15   569.4 2112.17
     571 2112.22   572.3 2112.25   580.3 2112.06   592.4 2112.08   593.3 2112.03
   595.6 2111.92   596.4 2111.88   600.7 2111.74   604.8 2111.62   608.2 2111.53
   608.4 2111.53   613.1 2111.45   632.5 2110.83   640.5 2110.79   648.6    2111
   652.4 2111.57   652.6 2111.59   656.4 2112.38   656.6 2112.41   656.8 2112.44
   658.5 2112.64   660.6 2112.87   660.7 2112.88   664.7 2112.95   665.4 2112.79
   667.6 2112.34   668.7 2112.11   670.3 2111.57   672.8  2110.7   674.6 2110.65
   675.1 2110.63   676.8 2110.57   680.9 2110.08   684.8 2108.15     689 2106.75
     693 2106.77   694.5  2106.9   695.5    2107   697.1 2107.14     699 2107.17
   702.5 2107.21   709.2 2107.19   709.4 2107.18   717.3 2107.01   721.4 2107.08
   725.5  2107.3   726.9 2107.56   730.3  2108.2   733.2 2108.85   733.6 2108.93
   735.5 2108.89   737.6 2108.82   740.8 2107.91   741.7  2107.7   745.7 2106.78
   747.7  2106.7   747.8 2106.69   749.8 2106.61   751.3 2106.66   752.5 2106.74
   753.8 2106.79   754.7 2106.69   757.4 2106.46   757.9 2106.41   758.2 2106.35
   761.9 2105.62   771.9    2105   772.2 2104.98   774.1 2104.86   782.6 2104.21
   789.6 2103.82   790.3 2103.78   794.3 2103.39   806.5  2102.7   810.6  2102.4
   824.5 2101.73   834.9 2101.09     847  2100.6   851.1 2100.52   852.3 2100.48
   854.2 2100.42   855.1 2100.39   859.2 2100.35   863.2 2100.37   863.8 2100.34
   866.3 2100.25   867.3 2100.21   899.7 2099.53     920 2099.39   944.3 2099.61
   946.1 2099.59   946.5 2099.58     950 2099.53   950.9  2099.5   952.4 2099.47
   953.4 2099.43   956.9 2099.31   976.7 2099.07   992.9 2099.35    1009 2099.53
  1009.1 2099.53  1009.2 2099.54  1009.7 2099.56  1012.7 2099.69  1013.2 2099.71
  1013.9 2099.73  1016.2  2099.8  1019.7  2099.9  1021.3 2099.95  1023.2 2099.98
  1030.1  2100.1  1062.2 2100.16    1065 2100.23  1065.9 2100.23  1067.1 2100.24
  1068.5 2100.24  1069.9 2100.24  1071.9 2100.23    1072 2100.23    1074 2100.23
  1075.4 2100.24  1076.8 2100.26    1078 2100.27  1078.9 2100.27  1081.6 2100.26
  1082.1 2100.26  1084.5 2100.27  1085.9 2100.28  1086.4 2100.28  1089.4  2100.3
  1090.2 2100.31  1091.3 2100.34  1092.9 2100.36  1098.3 2100.41  1099.8 2100.45
  1103.3 2100.55  1105.8 2100.64  1106.4 2100.67  1106.8 2100.68  1109.5 2100.77
  1110.3 2100.81  1110.4 2100.81  1110.6 2100.81  1113.8 2100.86  1114.5 2100.87
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BR D #Mann= 11
       0     .05   656.8      .1   709.2    .016   717.3      .1   771.9     .05
 1247.57     .03 1404.03     .08  1612.2     .06  1676.8    .016  1702.5     .06
  1717.7     .05
BC Design=,, 0 ,, 0 ,,,,,,
BC Use User HTab Curves=0
BC User HTab FreeFlow(D)= 0

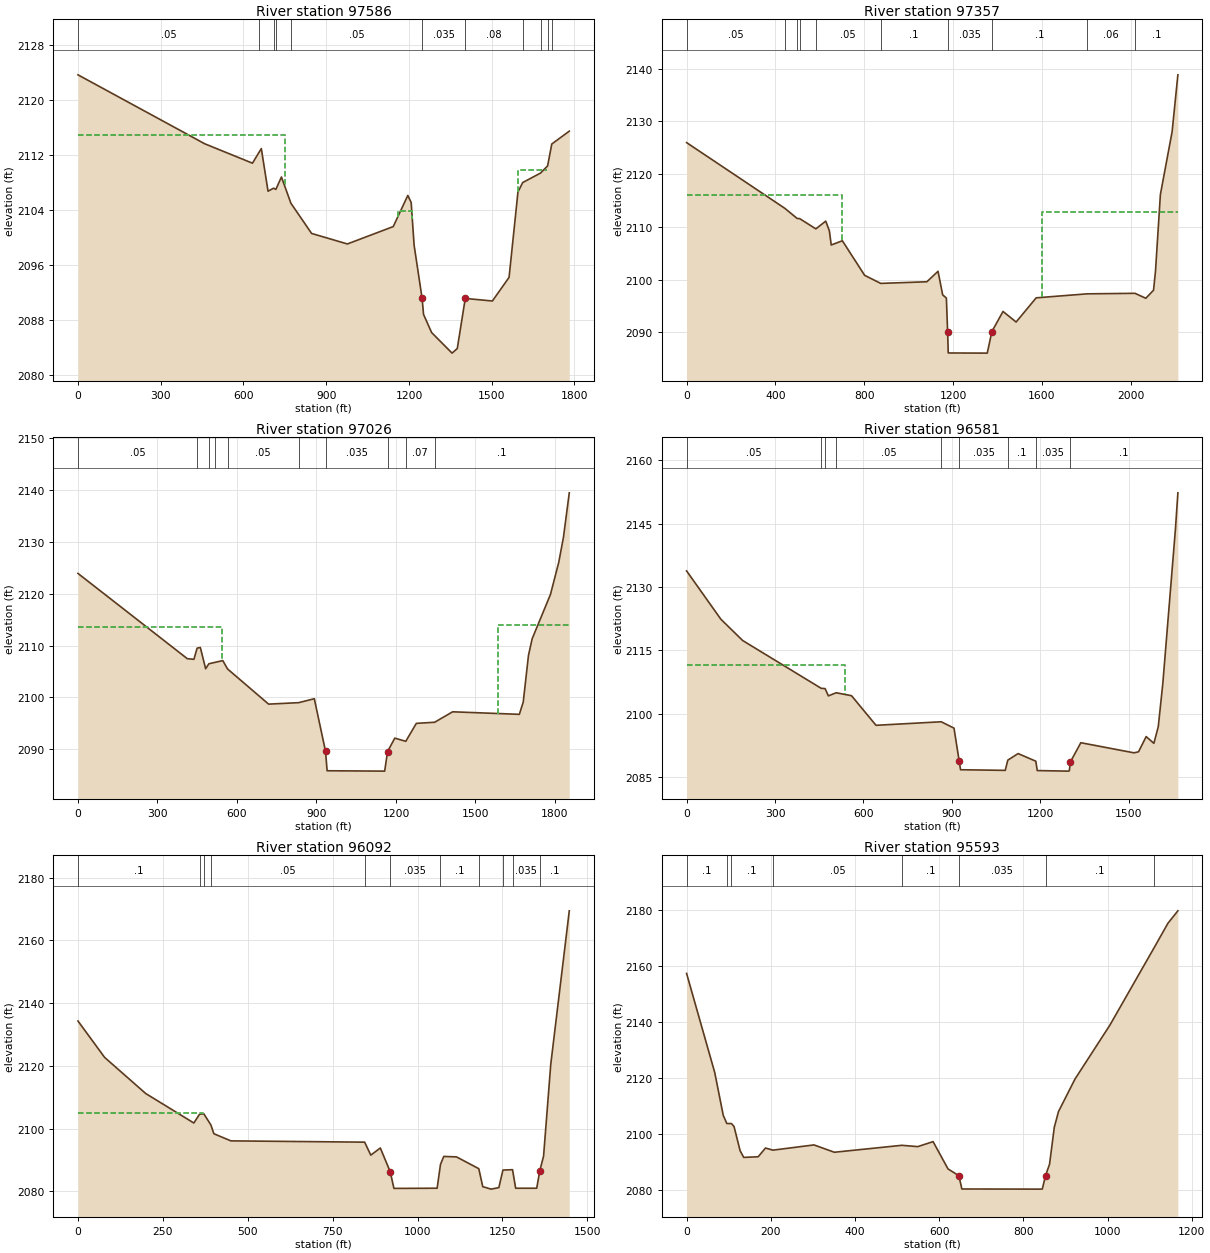
Type RM Length L Ch R = 1 ,97586   ,192.5,229.2,258.8
BEGIN DESCRIPTION:
structure xs 2
channel burned per surveyed cross section inverts
END DESCRIPTION:
XS GIS Cut Line= 6
2219750.60623511433132.2788034262219094.22937763433185.523925626
2218597.81125013433104.8346877282218191.24342473433026.552022165
2218096.96822514432992.6704513782217995.94973023433022.687033667
#Sta/Elev= 30
       0 2123.69   459.7 2113.65   632.5 2110.83   656.8 2112.44   664.7 2112.95
     689 2106.75   709.2 2107.19   717.3 2107.01   737.6 2108.82   771.9    2105
     847  2100.6   976.7 2099.07  1142.9  2101.6  1195.7 2106.13  1207.9 2105.11
 1218.55 2098.89 1247.57 2091.14 1252.83 2088.81 1282.16 2086.17 1356.19 2083.18
 1375.08 2083.85 1404.03 2091.14 1502.38 2090.77 1562.84 2094.21    1595 2106.63
  1612.2 2108.01  1676.8 2109.39  1702.5 2110.43  1717.7 2113.62  1781.1 2115.49
#Mann= 11 ,-1,0
       0     .05       0   656.8      .1       0   709.2    .016       0
   717.3      .1       0   771.9     .05       0 1247.57    .035       0
 1404.03     .08       0  1612.2     .06       0  1676.8    .016       0
  1702.5     .06       0  1717.7     .05       0
#XS Ineff= 3 ,-1
       0     751    2115    1159    1212  2103.8  1595.3    1700 2109.88
Permanent Ineff=
       F       F       F
Bank Sta=1247.57,1404.03
XS Rating Curve= 0 ,0
Exp/Cntr(USF)=0,0
Exp/Cntr=0.5,0.3

Type RM Length L Ch R = 1 ,97357   ,286.1,330.4,379.7
BEGIN DESCRIPTION:
structure xs 1 - channel burned 2.41':
lidar invert = 2088.44
interpolated invert = 2086.03
END DESCRIPTION:
XS GIS Cut Line= 5
 2219714.1555123433019.574468038 2219092.3219126433034.834188276
2218282.49184639432787.735253577 2218107.3552898432718.565577124
2217875.68620275432213.604599244
#Sta/Elev= 30
       0 2125.98   442.1 2113.52   498.1 2111.58   509.1 2111.56   582.2 2109.61
   626.7 2111.08   643.1 2109.23   651.4 2106.55   701.6 2107.35     802 2100.79
   874.4 2099.26  1082.2 2099.57  1132.4 2101.56  1153.3 2097.09    1170 2096.48
 1175.692089.996  1178.4 2086.06  1354.1 2086.031374.9092090.122  1425.1 2093.94
  1484.1 2091.93  1574.4 2096.52  1803.8 2097.28  2019.3 2097.38  2068.1 2096.44
    2103 2097.97  2111.8 2101.62  2133.8 2116.12  2186.6 2128.05  2212.6 2138.84
#Mann= 10 ,-1,0
       0     .05       0   442.1      .1       0   498.1    .016       0
   509.1      .1       0   582.2     .05       0   874.4      .1       0
 1175.69    .035       01374.909      .1       0  1803.8     .06       0
  2019.3      .1       0
#XS Ineff= 2 , 0
          701.41 2115.96 1598.59         2112.72
Permanent Ineff=
       F       F
Bank Sta=1175.69,1374.909
XS Rating Curve= 0 ,0
Exp/Cntr(USF)=0,0
Exp/Cntr=0.3,0.1

Type RM Length L Ch R = 1 ,97026   ,459.3,445.5,431.8
BEGIN DESCRIPTION:
channel burned 2.51':
lidar invert = 2088.31
effective invert = 2085.80
END DESCRIPTION:
XS GIS Cut Line= 4
2219610.76365181432840.248808958 2219118.5264002432782.828826921
2218207.63946895 432352.23986814 2217887.8735073432207.420331816
#Sta/Elev= 30
       0 2123.92   412.6 2107.48   437.5 2107.36   449.6 2109.51   461.7 2109.64
   481.8 2105.54   493.9  2106.5   515.9 2106.76   546.6 2107.11   564.5  2105.5
   719.4 2098.72   832.7    2099   891.9 2099.76  934.25 2089.61   940.2 2085.87
  1157.4  2085.8  1168.3 2089.57  1195.6 2092.16  1237.1 2091.55  1276.9 2095.01
  1345.8 2095.22    1414 2097.24  1665.7 2096.75  1680.3 2099.12  1700.1 2108.11
  1714.1 2111.33  1783.1 2119.87  1814.3 2126.05  1831.9 2130.82  1854.1 2139.46
#Mann= 10 ,-1,0
       0     .05       0   449.6      .1       0   493.9    .016       0
   515.9      .1       0   564.5     .05       0   832.7      .1       0
  934.25    .035       0  1168.3      .1       0  1237.1     .07       0
  1345.8      .1       0
#XS Ineff= 2 , 0
          545.35 2113.52 1584.95         2113.99
Permanent Ineff=
       F       F
Bank Sta=934.25,1168.3
XS Rating Curve= 0 ,0
Exp/Cntr(USF)=0,0
Exp/Cntr=0.3,0.1

Type RM Length L Ch R = 1 ,96581   ,456.5,489.3,528.5
BEGIN DESCRIPTION:
channel burned 1.33':
lidar invert = 2087.7
interpolated invert = 2086.37
END DESCRIPTION:
XS GIS Cut Line= 2
2219767.28939916432552.915454243 2218233.1550565431901.360492768
#Sta/Elev= 30
       0 2133.79   116.4 2122.34   190.3  2117.3   456.7 2105.98     470 2105.91
   481.1 2104.19   507.5 2104.93   559.6 2104.23   642.7 2097.22   863.9 2098.06
   907.3 2096.55924.55152088.878   929.5  2086.7  1081.1 2086.55  1089.8 2088.97
  1124.7 2090.53  1184.8 2088.72  1189.8  2086.5  1294.1 2086.37  1298.6 2086.45
1301.651 2088.48  1337.5  2093.1  1518.2  2090.7  1533.4 2090.96  1559.2 2094.55
  1585.4 2092.95  1600.3 2096.92  1615.7 2107.13  1658.5  2143.7  1666.8 2152.28
#Mann= 9 ,-1,0
       0     .05       0   456.7    .016       0     470      .1       0
   507.5     .05       0   863.9      .1       0924.5515    .035       0
  1089.8      .1       0  1184.8    .035       01301.651      .1       0
#XS Ineff= 2 , 0
          536.45 2111.51
Permanent Ineff=
       F       F
Bank Sta=924.5515,1301.651
XS Rating Curve= 0 ,0
Exp/Cntr=0.3,0.1

Type RM Length L Ch R = 1 ,96092   ,448,499.1,577.4
BEGIN DESCRIPTION:
channel burned 4.33':
lidar invert = 2085.03
interpolated invert = 2080.7
END DESCRIPTION:
XS GIS Cut Line= 2
2219875.40042921432168.113680661     2218601.579      431481.917
#Sta/Elev= 30
       0 2134.32    78.4 2122.72   199.4  2111.2   341.2 2101.79   358.1 2104.61
   370.7 2104.71   391.4 2101.17   400.2 2098.37   450.4 2096.09   844.2 2095.68
   862.4 2091.54   890.4 2093.82919.53162086.253   930.5 2080.93  1057.7 2080.99
  1067.6 2088.58  1077.3 2091.13  1114.8 2090.98  1180.4 2087.22 1192.13 2081.48
  1216.8  2080.7  1239.5 2081.19  1251.5 2086.78  1279.8  2086.9    1289 2080.99
    1351 2080.991360.028 2086.53  1371.2 2091.24  1392.4 2120.55  1446.9 2169.46
#Mann= 11 ,-1,0
       0      .1       0   358.1    .016       0   370.7      .1       0
   391.4     .05       0   844.2      .1       0919.5316    .035       0
  1067.6      .1       0  1180.4    .035       0  1251.5      .1       0
  1279.8    .035       01360.028      .1       0
#XS Ineff= 2 , 0
       0  366.87    2105               0
Permanent Ineff=
       F       F
Bank Sta=919.5316,1360.028
XS Rating Curve= 0 ,0
Exp/Cntr=0.3,0.1

Type RM Length L Ch R = 1 ,95593   ,486.1,476.3,473.9
BEGIN DESCRIPTION:
channel burned 3.55':
lidar invert = 2083.98
interpolated invert = 2080.43
END DESCRIPTION:
XS GIS Cut Line= 2
2219847.51130882431682.981260849     2218892.025      431012.523
#Sta/Elev= 30
       0 2157.47    66.9 2122.07    87.1 2106.79    95.6 2103.87   106.7 2103.84
   112.8 2102.76   127.2 2094.14   135.8 2091.76   170.1 2091.99   187.5 2095.11
   205.1 2094.35   302.6 2096.22   351.1  2093.6   511.5 2096.08   549.3 2095.61
   585.6  2097.4   621.1 2087.65   646.9 2085.22     654 2080.48   836.4 2080.43
   845.1 2080.45   852.7 2085.23   862.3 2089.32   873.6 2102.52   883.6 2108.14
   922.7 2119.72  1005.9 2139.06  1110.4 2166.55  1143.7 2175.41  1167.2 2179.82
#Mann= 8 ,-1,0
       0      .1       0    95.6    .016       0   106.7      .1       0
   205.1     .05       0   511.5      .1       0   646.9    .035       0
   852.7      .1       0  1110.4     .05       0
Bank Sta=646.9,852.7
XS Rating Curve= 0 ,0
Exp/Cntr=0.3,0.1

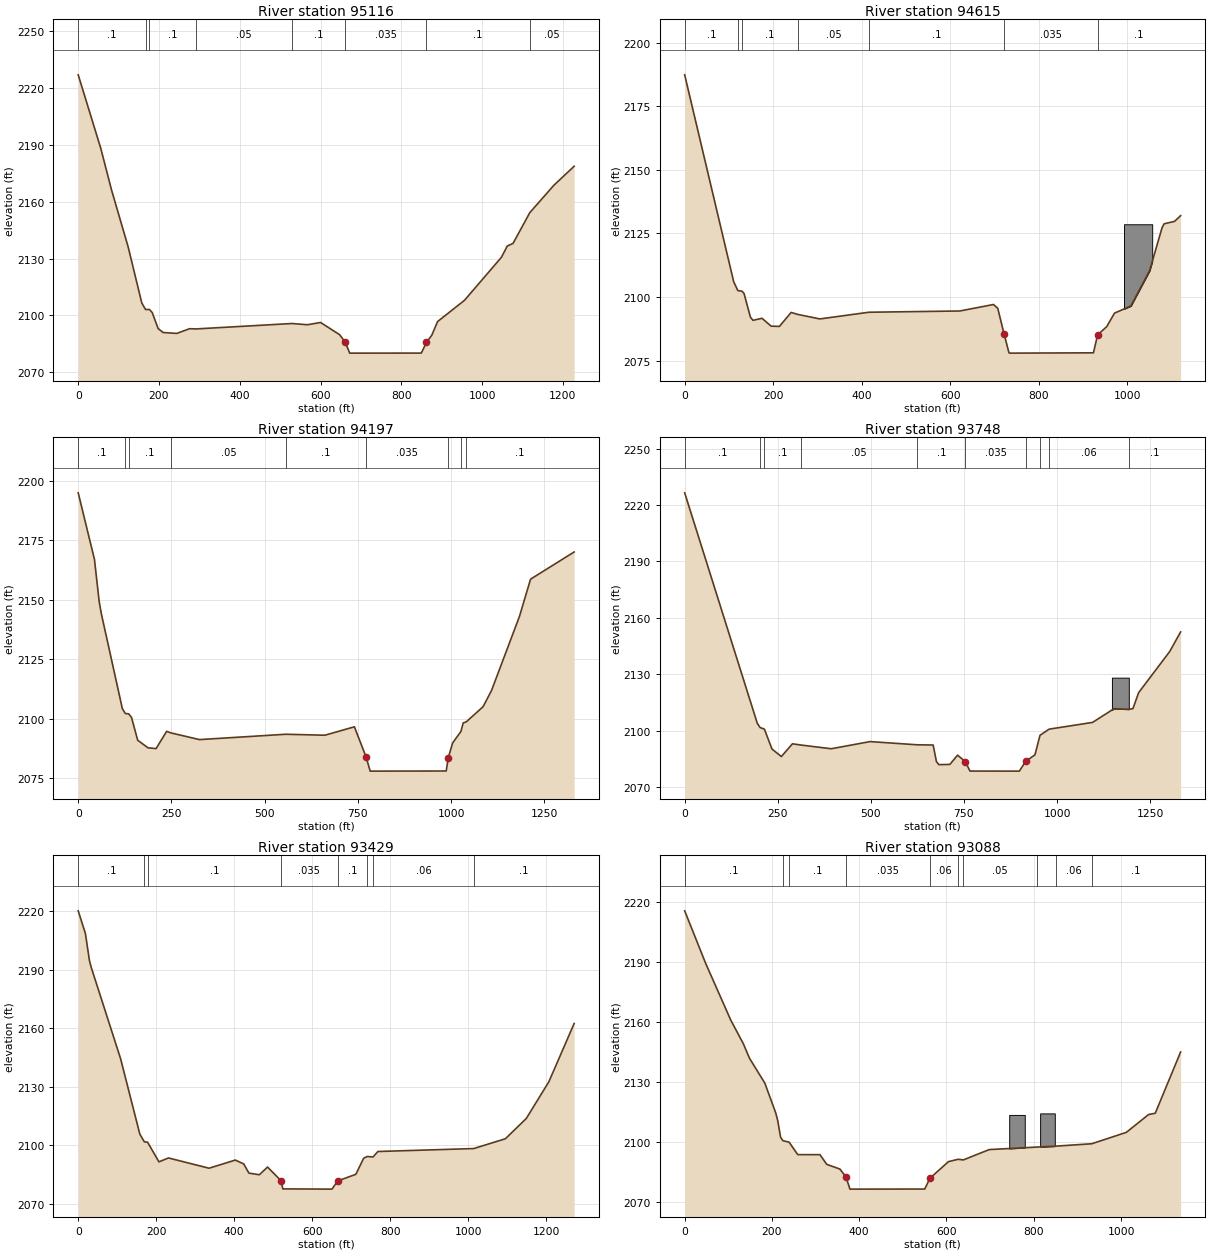
Type RM Length L Ch R = 1 ,95116   ,521.4,501.4,497.2
BEGIN DESCRIPTION:
channel burned 3.19':
lidar invert = 2083.19
effective invert = 2080.0
END DESCRIPTION:
Node Name=K
XS GIS Cut Line= 2
2220178.66141526431313.0642733352219158.59022339430629.723423785
#Sta/Elev= 30
       0 2227.08      56 2188.13    82.4  2166.3   123.4 2136.34   157.4 2106.51
   166.7 2103.05   176.3 2103.07   183.3 2101.43   197.8    2093     210 2090.91
   243.9 2090.41   275.6  2092.9   291.9 2092.79   529.3 2095.65   567.6    2095
     600  2096.2   647.5  2089.7     661 2085.78   672.2    2080   849.4 2080.02
   862.2 2085.69   875.3 2089.43   889.7 2096.68   956.3 2107.91  1047.8 2130.66
  1062.2 2136.59  1076.6    2138  1117.9 2154.21  1177.7 2168.73  1227.8 2178.76
#Mann= 8 ,-1,0
       0      .1       0   166.7    .016       0   176.3      .1       0
   291.9     .05       0   529.3      .1       0     661    .035       0
   862.2      .1       0  1117.9     .05       0
Bank Sta=661,862.2
XS Rating Curve= 0 ,0
Exp/Cntr=0.3,0.1

Type RM Length L Ch R = 1 ,94615   ,310.6,417.7,449.4
BEGIN DESCRIPTION:
channel burned 4.67':
lidar invert = 2082.62
effective invert = 2077.95
END DESCRIPTION:
XS GIS Cut Line= 2
2220518.39907492430899.4551209062219564.43060533430311.224466327
#Sta/Elev= 30
       0 2187.39   110.8    2106   120.1 2102.56   129.5  2102.3   134.1 2101.43
   148.6 2092.07   154.4 2090.84   174.8 2091.65   195.3 2088.56   214.1 2088.46
   240.6 2093.95   255.8 2093.16   305.6  2091.4   416.2 2094.03   621.6 2094.52
   697.9 2097.07   707.5 2095.57   721.6 2085.61   732.9 2078.05   735.7 2077.95
   923.7 2078.07   933.1  2085.1   953.8  2088.4   971.3 2093.67  1008.3  2096.5
  1050.6 2110.36  1078.8 2127.29  1083.5 2128.82  1106.9 2129.75  1120.7 2132.01
#Mann= 7 ,-1,0
       0      .1       0   120.1    .016       0   129.5      .1       0
   255.8     .05       0   416.2      .1       0   721.6    .035       0
   933.1      .1       0
#Block Obstruct= 1 ,-1
  992.74 1056.49 2128.63
Bank Sta=721.6,933.1
XS Rating Curve= 0 ,0
Exp/Cntr=0.3,0.1

Type RM Length L Ch R = 1 ,94197   ,337.6,448.7,523
BEGIN DESCRIPTION:
channel burned 4.19':
lidar invert = 2082.19
effective invert = 2078.00
END DESCRIPTION:
XS GIS Cut Line= 2
2220675.75396848430720.9299809632219712.06219842429804.084542713
#Sta/Elev= 30
       0 2194.98    43.6 2166.98    56.1 2149.46    61.8 2144.34   118.4 2104.27
   126.4 2102.21   135.3 2102.08     143 2100.56   159.5    2091   187.1  2087.8
   208.9 2087.48   237.2 2094.72   249.2 2094.05   325.2 2091.25     557  2093.5
   661.6 2093.09   740.8 2096.63   772.4 2083.82   783.1    2078     987 2078.05
   992.6 2083.62  1004.3 2089.84  1026.6 2094.68  1032.6 2098.27  1040.7  2098.7
    1086 2105.08  1108.6  2111.9  1183.5 2143.02  1213.3 2158.69  1330.2 2170.12
#Mann= 9 ,-1,0
       0      .1       0   126.4    .016       0   135.3      .1       0
   249.2     .05       0     557      .1       0   772.4    .035       0
   992.6      .1       0  1026.6    .016       0  1040.7      .1       0
Bank Sta=772.4,992.6
XS Rating Curve= 0 ,0
Exp/Cntr=0.3,0.1

Type RM Length L Ch R = 1 ,93748   ,291.5,319.5,322.1
BEGIN DESCRIPTION:
channel burned 3.19':
lidar invert = 2081.69
effective invert = 2078.50
END DESCRIPTION:
XS GIS Cut Line= 4
2220970.86562528430430.2508490612220485.81867486430119.995822129
2220335.61001601 429605.570103612220199.51953177429432.516771801
#Sta/Elev= 30
       0  2226.5     195 2103.94   202.5 2101.69   214.1 2100.82   234.4 2090.27
   259.6 2086.25   289.4 2093.03   311.8 2092.39   393.7  2090.4   497.9 2094.21
   624.5  2092.5   667.3 2092.38   676.1 2083.54   682.6 2081.95   712.1 2082.07
   732.9 2086.99   753.5 2083.58   766.2 2078.53   898.7  2078.5   916.2 2083.77
   940.6 2087.14   954.2 2097.56   978.8 2100.83  1095.4 2104.41  1152.9 2111.69
  1194.2 2111.38  1203.8 2111.75  1219.1 2120.25  1302.4 2142.08  1331.8 2152.52
#Mann= 10 ,-1,0
       0      .1       0   202.5    .016       0   214.1      .1       0
   311.8     .05       0   624.5      .1       0   753.5    .035       0
   916.2      .1       0   954.2    .016       0   978.8     .06       0
  1194.2      .1       0
#Block Obstruct= 1 ,-1
 1147.29 1192.64 2128.22
Bank Sta=753.5,916.2
XS Rating Curve= 0 ,0
Exp/Cntr(USF)=0,0
Exp/Cntr=0.3,0.1

Type RM Length L Ch R = 1 ,93429   ,420.1,340.7,232.2
BEGIN DESCRIPTION:
channel burned 3.04':
lidar invert = 2080.44
effective invert = 2077.4
END DESCRIPTION:
XS GIS Cut Line= 4
2221000.94127229430297.7834308472220797.64561065429965.117802709
  2220555.706972 429402.274441972220350.73118092429227.540980726
#Sta/Elev= 30
       0  2220.1    18.5 2208.44    28.8  2194.6      33 2191.34   108.7 2144.29
   158.1 2105.56   169.5 2101.68   177.9 2101.47     207 2091.39   231.6 2093.38
   335.6 2088.12   402.9  2092.3   424.6  2090.3   437.7 2085.62   464.5 2084.77
   485.6 2088.72   520.4 2081.67   524.8 2077.52     651  2077.4     665 2081.56
     712 2084.99     732 2093.22   741.1 2094.12   756.3 2093.91   768.5 2096.69
  1014.3  2098.2  1095.5 2103.22  1149.1 2113.61  1206.9 2132.39  1271.9 2162.32
#Mann= 8 ,-1,0
       0      .1       0   169.5    .016       0   177.9      .1       0
   520.4    .035       0     665      .1       0   741.1    .016       0
   756.3     .06       0  1014.3      .1       0
Bank Sta=520.4,665
XS Rating Curve= 0 ,0
Exp/Cntr(USF)=0,0
Exp/Cntr=0.3,0.1

Type RM Length L Ch R = 1 ,93088   ,549.6,490.2,301.5
BEGIN DESCRIPTION:
channel burned 3.62':
lidar invert = 2079.88
interpolated invert = 2076.26
END DESCRIPTION:
XS GIS Cut Line= 2
     2221317.956      429881.6282220481.38470367429112.201574236
#Sta/Elev= 30
       0 2215.38    47.9 2189.22   105.7 2160.72   134.6 2148.87   148.4 2141.75
   183.8  2129.2   208.9 2114.22   213.4 2110.33   219.8 2102.22   225.2 2100.47
   239.4 2099.73   259.2  2093.5   310.1 2093.49   325.6 2088.64   355.7  2086.3
   369.6 2082.37   378.8 2076.26   550.2  2076.3     562 2081.68   604.6 2090.01
     627 2091.19   638.5 2090.85     698 2096.03   806.7 2097.27   851.5 2097.76
   932.9 2098.94  1012.2 2104.63  1063.2 2113.55  1078.5 2114.19  1136.6 2144.81
#Mann= 10 ,-1,0
       0      .1       0   225.2    .016       0   239.4      .1       0
   369.6    .035       0     562     .06       0     627    .016       0
   638.5     .05       0   806.7    .016       0   851.5     .06       0
   932.9      .1       0
#Block Obstruct= 2 ,-1
  743.78  779.44 2113.36  814.62  848.25 2114.12
Bank Sta=369.6,562
XS Rating Curve= 0 ,0
Exp/Cntr=0.3,0.1

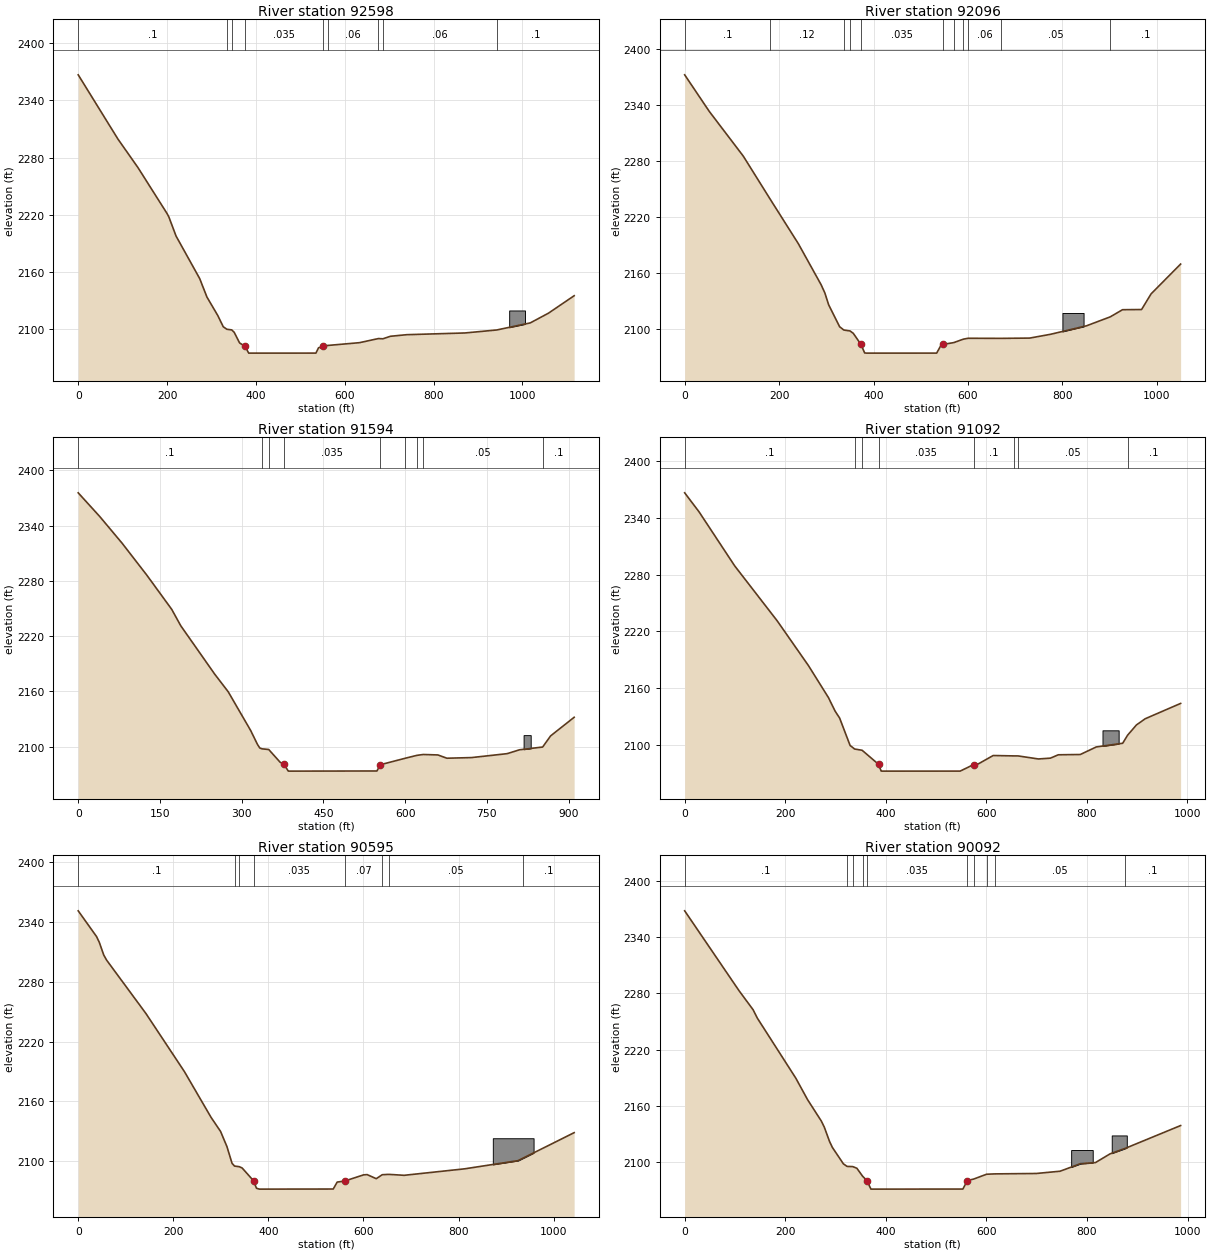
Type RM Length L Ch R = 1 ,92598   ,532.1,501.7,399.4
BEGIN DESCRIPTION:
channel burned 4.91':
lidar invert = 2079.5
interpolated invert = 2074.59
END DESCRIPTION:
XS GIS Cut Line= 2
     2221651.605      429239.862 2220559.6664678429006.719634689
#Sta/Elev= 30
       0 2366.97    89.4 2299.52   134.4 2269.62   199.8 2221.42     204  2217.8
   220.3  2197.6   273.5 2152.93   289.8 2133.54   314.4 2113.96   326.6 2102.27
   334.8 2099.64   345.6    2099   351.2 2096.45   363.4 2085.26   375.4 2081.85
   383.9 2074.59   535.2 2074.62   541.1 2080.19   552.2 2081.98   561.3 2082.62
   633.4 2085.58   675.9 2089.89     686 2089.64   702.8 2092.28   739.7 2093.96
   870.6 2095.77   942.3 2098.91  1017.9 2106.36  1058.8 2116.57  1116.6 2134.89
#Mann= 9 ,-1,0
       0      .1       0   334.8    .016       0   345.6      .1       0
   375.4    .035       0   552.2     .08       0   561.3     .06       0
   675.9    .016       0     686     .06       0   942.3      .1       0
#Block Obstruct= 1 ,-1
  970.33 1005.85 2119.41
Bank Sta=375.4,552.2
XS Rating Curve= 0 ,0
Exp/Cntr=0.3,0.1

Type RM Length L Ch R = 1 ,92096   ,519,502.8,453.3
BEGIN DESCRIPTION:
channel burned 5.52':
lidar invert = 2079.12
interpolated invert = 2073.60
END DESCRIPTION:
Node Name=J
XS GIS Cut Line= 2
     2221675.852      428603.6972220629.79725689428700.721423785
#Sta/Elev= 30
       0 2372.06    51.9 2332.98   124.2 2284.83   180.4 2239.29   240.7 2191.02
   288.9 2147.07   296.9 2138.19     305 2125.41   328.2 2101.92   337.1 2098.38
   350.3 2097.38   357.2 2094.82   373.3 2082.99   381.3  2073.8   385.3  2073.6
   533.8 2073.63   542.6 2081.75   547.1 2082.95   570.1  2084.9   590.2 2088.56
   600.2 2089.53   670.1 2089.43   730.8 2089.73     775  2093.8   851.3 2102.92
   901.3 2112.47   927.5 2120.17   967.8 2120.36   987.9 2137.12  1050.5  2169.1
#Mann= 11 ,-1,0
       0      .1       0   180.4     .12       0   337.1    .016       0
   350.3      .1       0   373.3    .035       0   547.1      .1       0
   570.1     .08       0   590.2    .016       0   600.2     .06       0
   670.1     .05       0   901.3      .1       0
#Block Obstruct= 1 ,-1
  800.13  844.93 2116.68
Bank Sta=373.3,547.1
XS Rating Curve= 0 ,0
Exp/Cntr=0.3,0.1

Type RM Length L Ch R = 1 ,91594   ,519.2,501.7,444.9
BEGIN DESCRIPTION:
channel burned 5.30':
lidar invert = 2078.75
interpolated invert = 2073.45
END DESCRIPTION:
XS GIS Cut Line= 2
     2221586.189      428033.197     2220706.427      428265.832
#Sta/Elev= 30
       0  2375.7    39.3 2350.12    80.7 2320.88   126.2 2286.06   171.6 2249.13
   188.1 2231.41   250.3  2178.9   275.2 2159.68   316.5 2117.52   328.9  2102.5
   333.1  2098.6   337.2 2097.65   349.6 2096.93   370.3 2083.24   377.9 2080.65
   385.3 2073.55   386.9 2073.45   548.1 2073.61   554.6 2080.43   600.4 2087.49
   621.6  2090.6   633.2 2091.51   659.9 2091.03   676.5 2087.47   721.5 2088.15
     787 2092.42   809.9 2096.64   852.2 2099.63   866.8 2111.71     910 2131.93
#Mann= 9 ,-1,0
       0      .1       0   337.2    .016       0   349.6      .1       0
   377.9    .035       0   554.6     .06       0   600.4     .06       0
   621.6    .016       0   633.2     .05       0   852.2      .1       0
#Block Obstruct= 1 ,-1
  817.22  830.28 2112.54
Bank Sta=377.9,554.6
XS Rating Curve= 0 ,0
Exp/Cntr=0.3,0.1

Type RM Length L Ch R = 1 ,91092   ,522.7,496.4,411.9
BEGIN DESCRIPTION:
channel burned 5.43':
lidar invert = 2078.41
interpolated invert = 2072.98
END DESCRIPTION:
XS GIS Cut Line= 2
     2221389.927      427479.5512220501.02556373427907.820329831
#Sta/Elev= 30
       0 2366.01    28.6    2346    99.6 2289.03     184 2231.28   246.1 2184.22
   286.1 2150.34   299.4 2136.04   308.2 2128.96   329.1 2100.04   338.1 2096.27
   353.1 2094.91   386.1 2079.97   390.8 2073.13   392.7 2072.98   548.1 2073.01
   575.1 2079.91   583.6 2080.41   613.8 2089.41   654.6 2089.01   663.5 2088.98
   703.7 2085.79   727.7 2086.66   743.4 2090.18   787.1 2090.48   818.9 2098.44
   871.5 2102.33   881.1 2110.74   898.8  2121.6   916.4 2128.17   986.7 2144.27
#Mann= 8 ,-1,0
       0      .1       0   338.1    .016       0   353.1      .1       0
   386.1    .035       0   575.1      .1       0   654.6    .016       0
   663.5     .05       0   881.1      .1       0
#Block Obstruct= 1 ,-1
  831.25   863.4 2115.94
Bank Sta=386.1,575.1
XS Rating Curve= 0 ,0
Exp/Cntr=0.3,0.1

Type RM Length L Ch R = 1 ,90595   ,506.4,503,494.9
BEGIN DESCRIPTION:
channel burned 5.90':
lidar invert = 2078
effective invert = 2072.10
END DESCRIPTION:
XS GIS Cut Line= 2
     2221047.234      426965.7742220263.44949277427654.029989492
#Sta/Elev= 30
       0 2351.03    38.6 2325.22    44.3 2319.51    53.7 2306.76    59.7 2301.65
   142.5 2248.07   223.4 2189.87   279.5 2143.97   299.4 2129.94   312.8 2114.76
   323.5 2098.04   328.8 2095.22   338.6  2094.6   344.8 2093.29   368.9  2080.4
  374.88 2073.02     381  2072.1   536.4  2072.2   544.7 2079.19   560.1 2080.15
   600.3  2086.4   607.7 2086.64   626.9 2082.57   639.5 2086.54   653.5 2086.88
   685.5 2085.95   812.4 2092.42     925 2100.67   935.6 2103.13  1043.1  2128.7
#Mann= 8 ,-1,0
       0      .1       0   328.8    .016       0   338.6      .1       0
   368.9    .035       0   560.1     .07       0   639.5    .016       0
   653.5     .05       0   935.6      .1       0
#Block Obstruct= 1 ,-1
  872.01  957.76  2123.1
Bank Sta=368.9,560.1
XS Rating Curve= 0 ,0
Exp/Cntr=0.3,0.1

Type RM Length L Ch R = 1 ,90092   ,505.7,498.9,498.7
BEGIN DESCRIPTION:
channel burned 6.51':
lidar invert = 2077.58
interpolated invert = 2071.07
END DESCRIPTION:
XS GIS Cut Line= 2
     2220694.575      426587.2712219974.41759921427260.961883051
#Sta/Elev= 30
       0 2368.28   108.2 2282.91   136.1 2262.61   144.5 2253.66     221 2189.55
   244.3 2166.67   271.7 2143.77   277.6 2137.31   288.1 2121.92   293.6 2115.68
   315.5 2098.14   322.8 2095.33   334.2 2095.13   342.4 2093.34   353.8 2084.85
   362.5 2080.12   370.3  2071.1   373.8 2071.07   553.2 2071.15     562 2080.22
   574.7 2081.83   600.3 2086.98   617.2 2087.35   698.9 2087.77   746.4 2090.19
     787 2098.27   816.7 2099.41   845.9 2108.76   875.2 2114.44   986.1 2138.97
#Mann= 10 ,-1,0
       0      .1       0   322.8    .016       0   334.2      .1       0
   353.8    .045       0   362.5    .035       0     562    .045       0
   574.7     .06       0   600.3    .016       0   617.2     .05       0
   875.2      .1       0
#Block Obstruct= 2 ,-1
  768.44  811.32 2112.81  849.13  879.09 2128.41
Bank Sta=362.5,562
XS Rating Curve= 0 ,0
Exp/Cntr=0.3,0.1