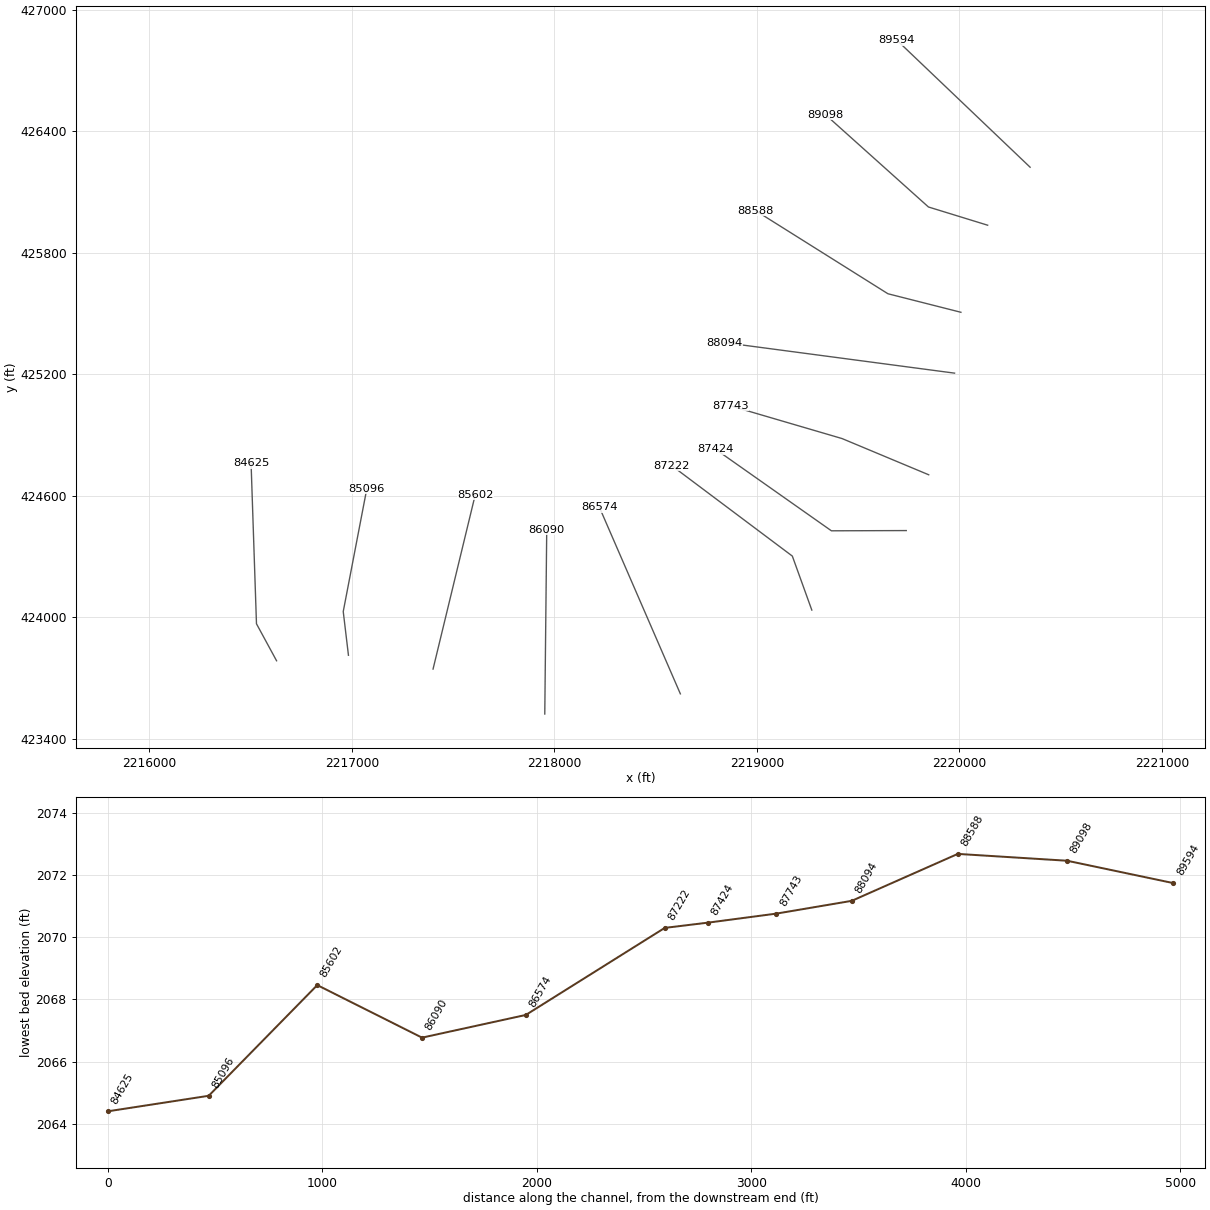
HEC-RAS study GRNBRRRV.prj: GRNBRRRV

--- GRNBRRRV.g01 (geometry) --- (continued)

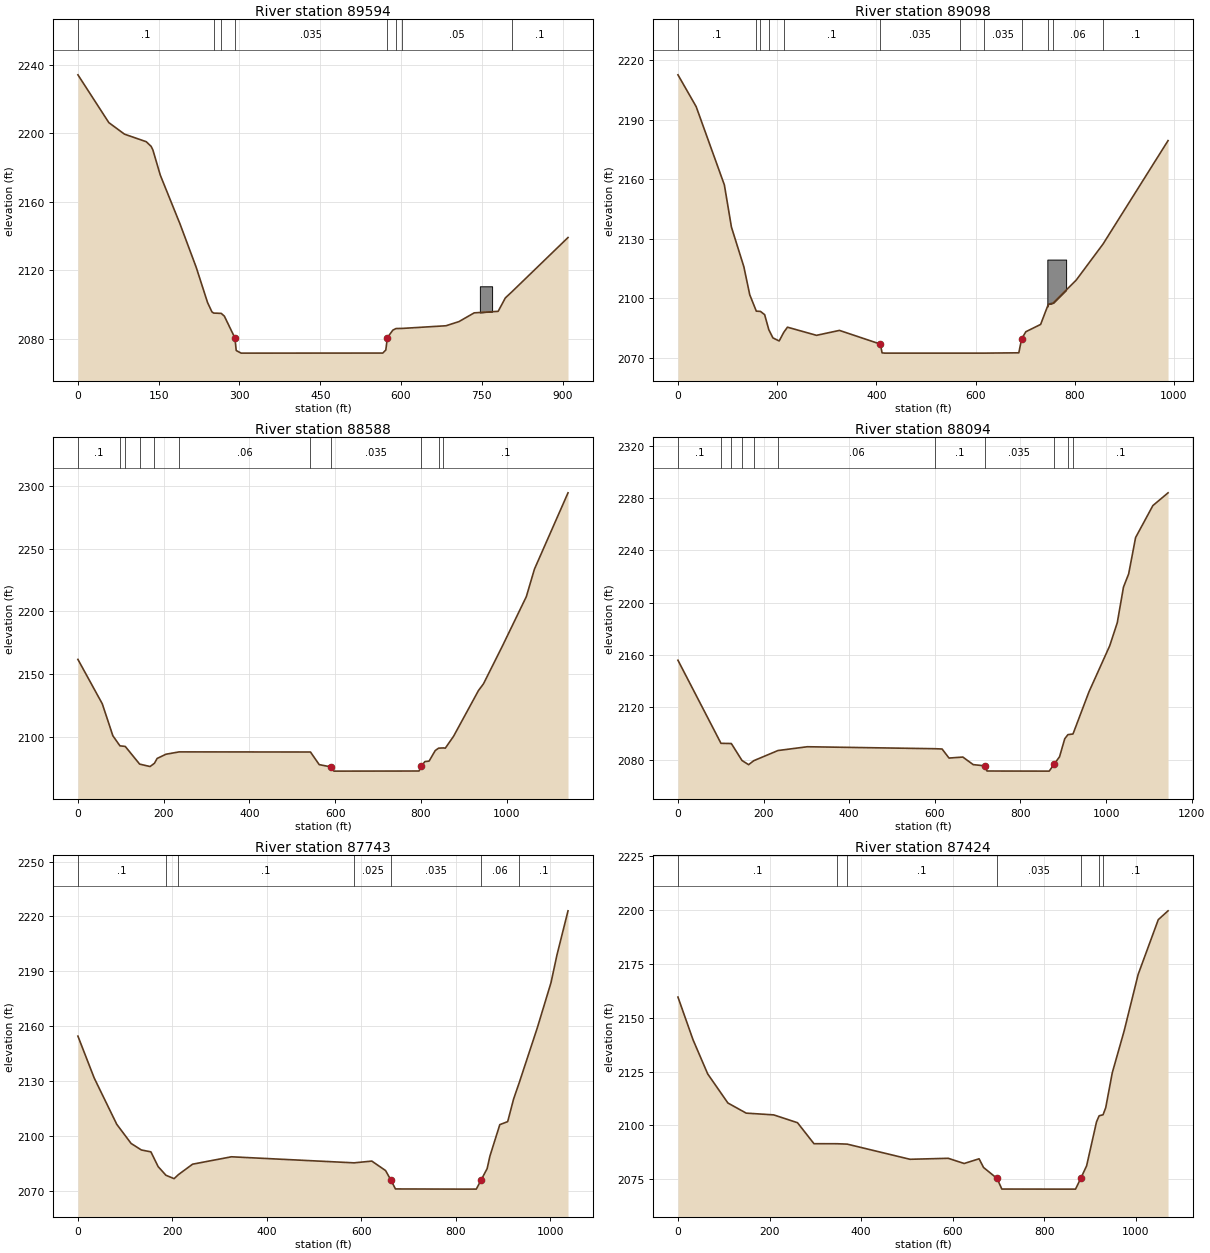
Type RM Length L Ch R = 1 ,89594   ,462.9,495.5,503.5
BEGIN DESCRIPTION:
channel burned 5.43':
lidar invert = 2077.17
interpolated invert = 2071.74
END DESCRIPTION:
XS GIS Cut Line= 2
     2220348.911      426221.591     2219690.275      426849.523
#Sta/Elev= 30
       0 2234.16    57.4 2206.27    86.4 2199.54   126.9 2195.12     136 2192.39
   139.2 2190.32     153 2175.57   189.8 2146.94   219.7 2121.77   240.7 2101.28
   248.7 2095.87     252 2095.11   266.1 2094.94   271.9 2093.33   291.6 2080.54
   293.9 2073.27     303 2071.74   566.1 2071.78   571.7 2073.57   574.6  2080.8
   584.9  2085.2   590.7 2086.09   602.3 2086.16   683.4 2087.71   707.5 2090.14
   735.8 2095.24   780.3 2096.13   793.6 2103.95   805.2 2107.35     910 2139.21
#Mann= 8 ,-1,0
       0      .1       0     252    .016       0   266.1      .1       0
   291.6    .035       0   574.6     .06       0   590.7    .016       0
   602.3     .05       0   805.2      .1       0
#Block Obstruct= 1 ,-1
  746.31  769.06 2110.75
Bank Sta=291.6,574.6
XS Rating Curve= 0 ,0
Exp/Cntr=0.3,0.1

Type RM Length L Ch R = 1 ,89098   ,462.7,510,539.5
BEGIN DESCRIPTION:
channel burned 4.32':
lidar invert = 2076.78
interpolated invert = 2072.46
END DESCRIPTION:
Node Name=I
XS GIS Cut Line= 3
2220139.22340525425935.2467527352219846.86695143426025.198887009
     2219338.875      426480.651
#Sta/Elev= 30
       0 2212.57    36.7 2196.56    93.6 2157.14   107.8 2135.94   132.9 2115.93
   144.8 2101.81     158 2093.59   166.4 2093.46   174.8 2091.83   183.2 2084.26
   191.5 2080.12   204.1 2078.59   213.3 2082.91   220.8 2085.52   279.4 2081.42
   325.6  2083.9  408.01 2077.01   411.6 2072.59   416.9 2072.46   567.8 2072.46
   616.7 2072.46   687.3 2072.62     693 2079.66   701.5 2083.24   731.3 2086.92
   746.8 2097.07   756.6 2097.66   803.2 2109.28   857.1 2127.38   988.2 2179.45
#Mann= 12 ,-1,0
       0      .1       0     158    .016       0   166.4      .1       0
   183.2    .045       0   213.3      .1       0  408.01    .035       0
   567.8      .1       0   616.7    .035       0     693     .06       0
   746.8    .016       0   756.6     .06       0   857.1      .1       0
#Block Obstruct= 1 ,-1
  744.81  782.68 2119.56
Bank Sta=408.01,693
XS Rating Curve= 0 ,0
Exp/Cntr=0.3,0.1

Type RM Length L Ch R = 1 ,88588   ,338.5,494.4,547.1
BEGIN DESCRIPTION:
channel burned 2.94':
lidar invert = 2075.62
interpolated invert = 2072.68
END DESCRIPTION:
XS GIS Cut Line= 3
2220007.19325034425505.2909290392219646.75694764425596.781271602
      2218993.85      426006.762
#Sta/Elev= 30
       0 2161.69    56.8 2126.34    81.5 2100.85      98 2092.83   110.4 2092.35
   143.9 2078.28   168.2 2076.34   178.4 2078.93   184.7 2082.77   205.3 2086.14
   236.1 2088.01   542.3 2087.91   562.6 2077.88  590.37    2076   596.9 2072.68
   795.3 2072.77   800.5 2076.65   809.2 2080.28   818.9 2080.68   833.1 2089.05
   841.1 2090.98     852 2091.16   856.7    2091     876 2100.49     934 2136.89
   945.6  2142.2   989.4 2172.05  1045.6  2211.7  1064.5  2233.6  1142.8 2294.42
#Mann= 11 ,-1,0
       0      .1       0      98    .016       0   110.4      .1       0
   143.9    .045       0   178.4      .1       0   236.1     .06       0
   542.3      .1       0  590.37    .035       0   800.5      .1       0
   841.1    .016       0     852      .1       0
Bank Sta=590.37,800.5
XS Rating Curve= 0 ,0
Exp/Cntr=0.3,0.1

Type RM Length L Ch R = 1 ,88094   ,429.5,350.9,331.2
BEGIN DESCRIPTION:
channel burned 3.49':
lidar invert = 2074.66
interpolated invert = 2071.17
END DESCRIPTION:
XS GIS Cut Line= 2
2219975.76659266425204.7635052542218841.01173062425355.202352825
#Sta/Elev= 30
       0 2155.98   100.5 2092.43   124.7 2092.28   124.7 2092.27   149.6 2079.31
     165  2076.1   177.1 2079.16   233.6 2086.92   302.2 2089.82   600.8 2088.31
   616.9  2088.1   633.1 2081.16   665.4 2081.93   689.6 2076.14   716.1 2075.24
   721.9 2071.26   867.1 2071.17   878.2 2076.26   891.3 2082.19   903.4 2095.93
   910.8 2099.07   922.7 2099.59   959.9 2131.75  1008.5 2167.08  1026.1 2184.68
  1040.6 2211.92  1052.7 2222.03  1068.9 2249.82  1109.2 2274.25  1144.7 2284.03
#Mann= 11 ,-1,0
       0      .1       0   100.5    .016       0   124.7      .1       0
   149.6     .04       0   177.1      .1       0   233.6     .06       0
   600.8      .1       0   716.1    .035       0   878.2      .1       0
   910.8    .016       0   922.7      .1       0
Bank Sta=716.1,878.2
XS Rating Curve= 0 ,0
Exp/Cntr=0.3,0.1

Type RM Length L Ch R = 1 ,87743   ,425,318.2,283.1
BEGIN DESCRIPTION:
channel burned 3.30':
lidar invert = 2074.06
interpolated invert = 2070.76
END DESCRIPTION:
XS GIS Cut Line= 3
2219848.05809013424702.8743188182219420.19652935424881.734479469
2218869.58779951425043.059330252
#Sta/Elev= 30
       0 2154.51    34.6 2131.51    82.2 2106.25   112.6 2095.76   134.3 2092.19
   154.5 2091.17   169.8  2083.1   186.3 2078.36   203.6 2076.49   212.6 2078.67
   242.7 2084.41     325 2088.46   584.6 2085.15   622.2  2086.1   651.3 2080.92
   662.8 2075.59   672.2 2070.86   818.1 2070.76   843.4 2070.78  853.18 2075.59
   866.3 2081.99   872.2 2088.84   893.1 2106.05   909.8 2107.71   922.3 2120.08
     934 2128.85   972.3  2158.9  1001.5 2183.78    1014 2198.82  1037.5 2223.09
#Mann= 7 ,-1,0
       0      .1       0   186.3    .045       0   212.6      .1       0
   584.6    .025       0   662.8    .035       0  853.18     .06       0
     934      .1       0
Bank Sta=662.8,853.18
XS Rating Curve= 0 ,0
Exp/Cntr(USF)=0,0
Exp/Cntr=0.3,0.1

Type RM Length L Ch R = 1 ,87424   ,214.8,202.6,200.2
BEGIN DESCRIPTION:
channel burned 3.06':
lidar invert = 2073.53
interpolated invert = 2070.47
END DESCRIPTION:
XS GIS Cut Line= 3
2219737.18906215 424427.411810592219367.57806772424426.253417754
2218794.79404513424829.455494283
#Sta/Elev= 30
       0 2159.55      33  2139.7      65  2123.9     109 2110.43     149 2105.72
     209 2104.91     261 2101.28     297 2091.54   347.9 2091.52   369.6 2091.34
   506.7 2084.31   590.1 2084.77   624.9 2082.36   657.5 2084.54   667.3  2080.5
   696.6 2075.45   707.2 2070.51   833.5 2070.47   868.1 2070.47   879.4 2075.42
   892.3 2081.29   913.9 2101.65   919.6 2104.49   928.2 2104.96     934 2108.25
   948.3 2124.43   974.2 2143.83  1004.8 2170.05  1048.8 2195.48  1070.1 2199.56
#Mann= 7 ,-1,0
       0      .1       0   347.9    .016       0   369.6      .1       0
   696.6    .035       0   879.4      .1       0   919.6    .016       0
   928.2      .1       0
Bank Sta=696.6,879.4
XS Rating Curve= 0 ,0
Exp/Cntr=0.3,0.1

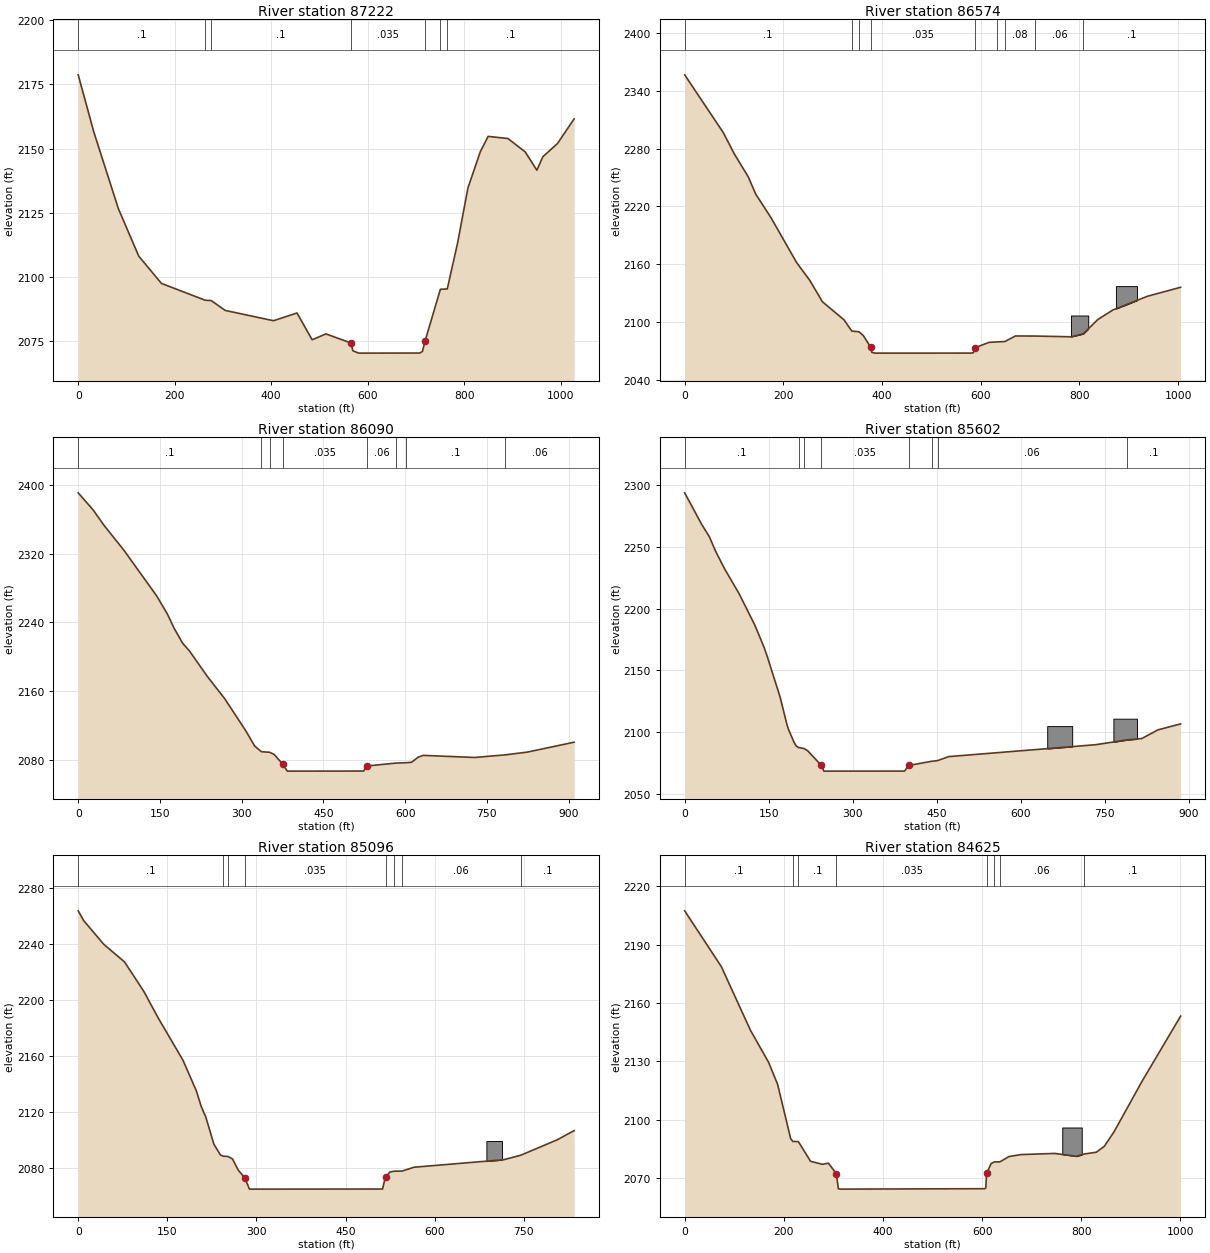
Type RM Length L Ch R = 1 ,87222   ,748.4,647.6,571.1
BEGIN DESCRIPTION:
channel burned 3.04':
lidar invert = 2073.34
effective invert = 2070.3
c/e 0.5/0.7 to correct drawdown
END DESCRIPTION:
XS GIS Cut Line= 3
2219270.76844876424034.866657683 2219174.6405764424301.401477185
2218578.81080158424748.143329831
#Sta/Elev= 30
       0 2178.76    32.2 2156.58    83.2 2126.62   125.5  2108.1   172.5 2097.47
   263.2 2090.92   275.7 2090.78   304.9 2086.93   404.9 2082.93   453.5 2085.95
   484.9  2075.5   513.5 2077.79  565.76 2074.23  569.26 2071.23   581.4  2070.3
   707.8 2070.33   713.5 2070.95   719.2 2075.16   750.7 2095.17     765 2095.31
   786.4 2113.22   807.8 2134.65   833.5  2148.8   849.7 2154.77   890.7 2153.94
   926.4 2148.75   950.7 2141.59   963.1 2146.84   993.5    2152    1028 2161.62
#Mann= 7 ,-1,0
       0      .1       0   263.2    .016       0   275.7      .1       0
  565.76    .035       0   719.2      .1       0   750.7    .016       0
     765      .1       0
Bank Sta=565.76,719.2
XS Rating Curve= 0 ,0
Exp/Cntr=0.7,0.5

Type RM Length L Ch R = 1 ,86574   ,533.3,483.8,376.6
BEGIN DESCRIPTION:
channel burned 5.31':
lidar invert = 2072.81
effective invert = 2067.50
END DESCRIPTION:
XS GIS Cut Line= 2
2218621.67763469423621.1394697742218221.62035282424543.033918532
#Sta/Elev= 30
       0 2356.52    78.5 2296.32   100.3 2274.62   128.9 2250.53   144.1 2232.51
   174.4  2208.6   226.8  2161.6   253.6 2143.03   279.1 2120.88   322.7 2102.16
   338.7 2090.41   353.2 2089.66     362 2085.72  376.64 2073.89   379.4 2068.24
   385.6  2067.5     580 2067.53     585 2067.84  587.92    2073   616.7 2078.68
   633.7 2079.17   648.9 2079.52   670.2  2085.3   710.8 2085.23   782.7 2084.46
   807.6 2087.54   837.2 2102.37   867.6 2112.29   937.7 2126.55    1005 2135.88
#Mann= 9 ,-1,0
       0      .1       0   338.7    .016       0   353.2      .1       0
  376.64    .035       0  587.92     .06       0   633.7    .016       0
   648.9     .08       0   710.8     .06       0   807.6      .1       0
#Block Obstruct= 2 ,-1
  782.75  817.78 2106.58  873.89   916.5 2137.09
Bank Sta=376.64,587.92
XS Rating Curve= 0 ,0
Exp/Cntr=0.3,0.1

Type RM Length L Ch R = 1 ,86090   ,510.8,488.5,425.7
BEGIN DESCRIPTION:
channel burned 5.67':
lidar invert = 2072.44
interpolated invert = 2066.77
END DESCRIPTION:
Node Name=H
XS GIS Cut Line= 2
     2217952.122      423521.526     2217961.796      424431.496
#Sta/Elev= 30
       0 2390.85    27.7  2370.7    47.2 2353.11    83.7 2324.16   143.7 2271.08
   163.7 2249.66   175.7 2233.48   191.7 2215.59   203.7 2207.11   237.2 2176.82
   268.9 2151.09   307.7 2113.53   323.7 2096.01   336.2 2089.37   351.4  2088.7
   359.7 2086.16   375.7 2074.49   375.7 2074.47   383.6 2066.77   523.7 2066.85
   530.1 2072.79   583.7 2076.17   601.3 2076.53   611.7 2077.06   623.7 2083.01
     633 2085.14   727.7 2082.67   783.4 2085.69   823.7 2088.88     910 2100.46
#Mann= 8 ,-1,0
       0      .1       0   336.2    .016       0   351.4      .1       0
   375.7    .035       0   530.1     .06       0   583.7    .016       0
   601.3      .1       0   783.4     .06       0
#Block Obstruct= 2 , 0
                          872.27         2114.79
Bank Sta=375.7,530.1
XS Rating Curve= 0 ,0
Exp/Cntr=0.3,0.1

Type RM Length L Ch R = 1 ,85602   ,500.1,506,517
BEGIN DESCRIPTION:
channel burned 3.60':
lidar invert = 2072.06
interpolated invert = 2068.46
c/e coefficient added to correct drawdown
END DESCRIPTION:
XS GIS Cut Line= 2
2217400.42389299423743.5985047522217608.87224393424604.522024481
#Sta/Elev= 30
       0 2293.76    30.4 2268.21    44.2 2258.13    55.1 2246.61    71.6 2231.99
    97.2 2212.11   125.1 2186.89   141.6 2168.94   146.9 2162.09   170.4 2128.55
   182.7 2106.05   185.9 2101.76   195.1 2092.04   199.2 2088.82   203.3 2087.59
   213.2 2086.75   219.8 2084.91244.09922073.123   248.6 2068.48   252.7 2068.46
   392.6 2068.49400.59872073.093   440.9 2076.41   451.7 2076.96   471.6 2080.21
   734.2 2089.85   789.7 2093.73   816.5 2094.84   845.3 2101.86   885.8  2106.7
#Mann= 8 ,-1,0
       0      .1       0   203.3    .016       0   213.2      .1       0
244.0992    .035       0400.5987     .06       0   440.9    .016       0
   451.7     .06       0   789.7      .1       0
#Block Obstruct= 2 ,-1
  647.54  692.14 2104.91  765.72  807.93 2110.92
Bank Sta=244.0992,400.5987
XS Rating Curve= 0 ,0
Exp/Cntr=0.7,0.5

Type RM Length L Ch R = 1 ,85096   ,445.7,470.7,521.4
BEGIN DESCRIPTION:
channel burned 6.66':
lidar invert = 2071.56
interpolated invert = 2064.90
END DESCRIPTION:
XS GIS Cut Line= 3
2216982.60460119423811.7004362722216956.86972214424027.540379274
     2217073.317      424633.874
#Sta/Elev= 30
       0 2263.85     9.5 2256.71    43.1 2239.88      78 2227.31   110.3 2206.36
   134.4 2187.45   176.3 2157.08   198.9 2135.12   206.9 2124.23     215 2116.15
   228.4 2097.01   239.4 2089.37   243.5 2088.49   252.3 2088.22   259.8 2086.43
   269.4 2078.46   280.1 2073.15   288.3 2064.92   295.9  2064.9   512.3 2064.97
   516.4 2072.42   517.7 2073.33   524.5 2077.13   531.8 2077.72   544.9 2077.78
   565.3 2080.56     716 2085.91   744.6 2089.08   805.6 2100.02   834.8 2106.73
#Mann= 8 ,-1,0
       0      .1       0   243.5    .016       0   252.3      .1       0
   280.1    .035       0   517.7     .06       0   531.8    .016       0
   544.9     .06       0   744.6      .1       0
#Block Obstruct= 1 ,-1
  687.08  713.29 2099.29
Bank Sta=280.1,517.7
XS Rating Curve= 0 ,0
Exp/Cntr=0.3,0.1

Type RM Length L Ch R = 1 ,84625   ,433.6,535.5,551.7
BEGIN DESCRIPTION:
channel burned 6.48':
lidar invert = 2070.88
effective invert = 2064.40
END DESCRIPTION:
XS GIS Cut Line= 3
2216627.62773062 423784.481294352216528.43671621423967.055719612
2216501.78804797424759.084730622
#Sta/Elev= 30
       0 2207.31    73.9 2178.68   132.8 2145.91   169.2 2129.56   187.4 2118.24
   213.8 2090.33     218 2088.91   229.4 2088.77   253.9 2078.68   277.9 2077.14
   289.9 2077.75     306 2072.27     310 2064.59     314  2064.4     605 2064.62
   607.4 2065.01   608.9 2072.43   618.1 2077.54   624.4 2078.36     636 2078.43
   654.2 2081.14   678.2 2082.14   746.2 2082.73   790.2 2081.29   806.1 2082.44
   830.3 2083.36   846.3 2086.35   866.3 2093.96   922.3 2119.69  1000.3 2153.22
#Mann= 8 ,-1,0
       0      .1       0     218    .016       0   229.4      .1       0
     306    .035       0   608.9     .06       0   624.4    .016       0
     636     .06       0   806.1      .1       0
#Block Obstruct= 1 ,-1
  761.57  800.85 2096.05
Bank Sta=306,608.9
XS Rating Curve= 0 ,0
Exp/Cntr=0.3,0.1