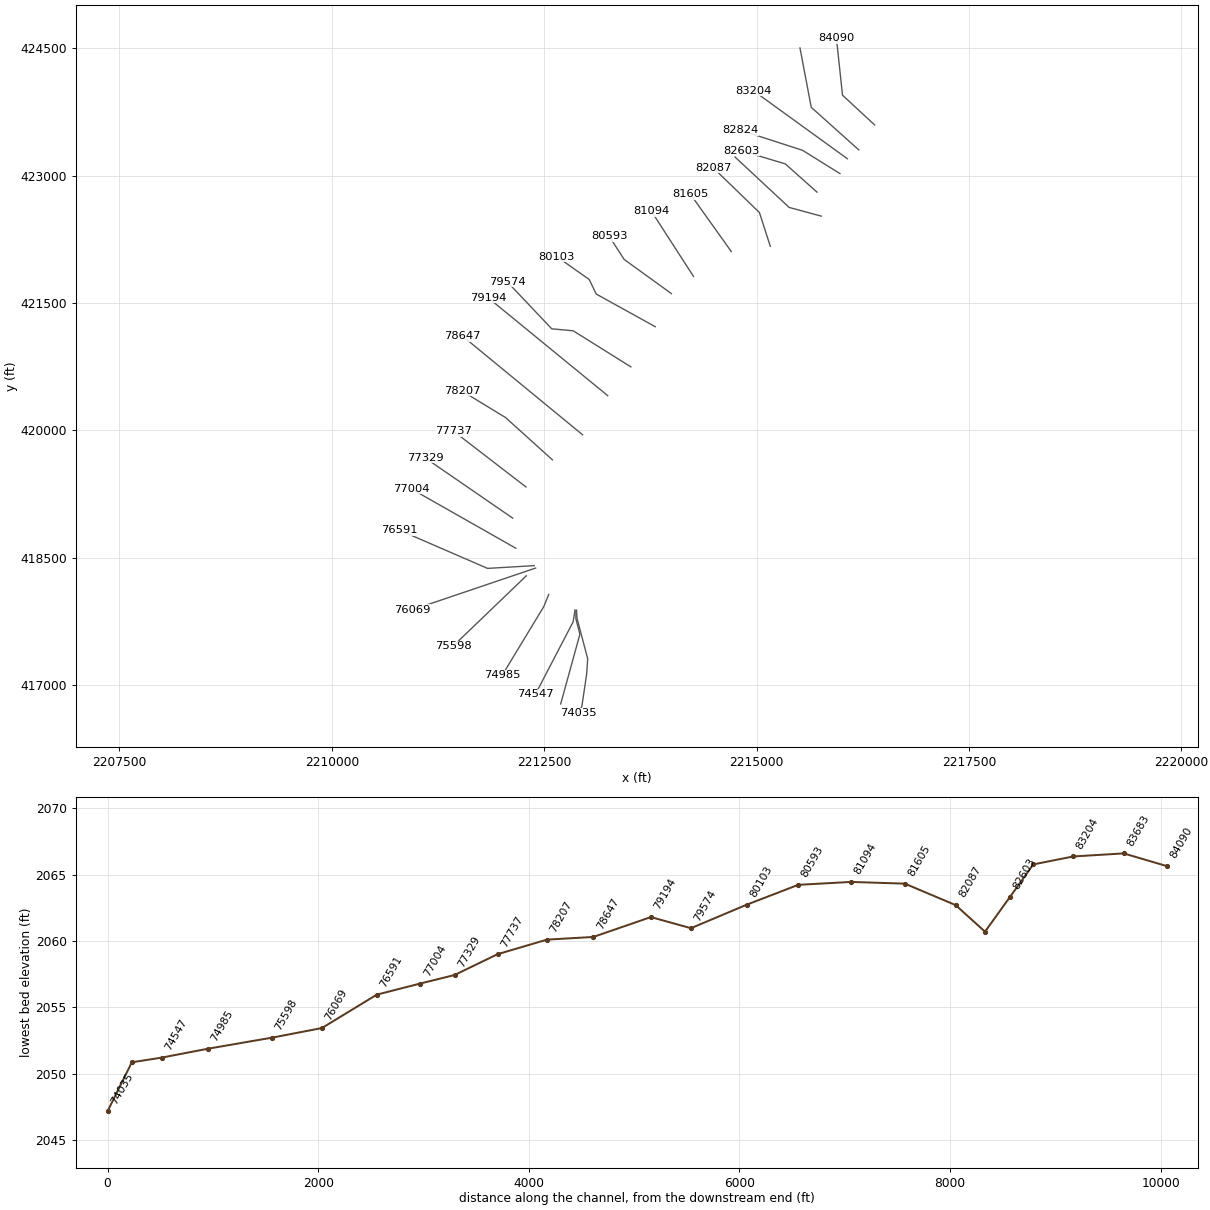
HEC-RAS study GRNBRRRV.prj: GRNBRRRV

--- GRNBRRRV.g01 (geometry) --- (continued)

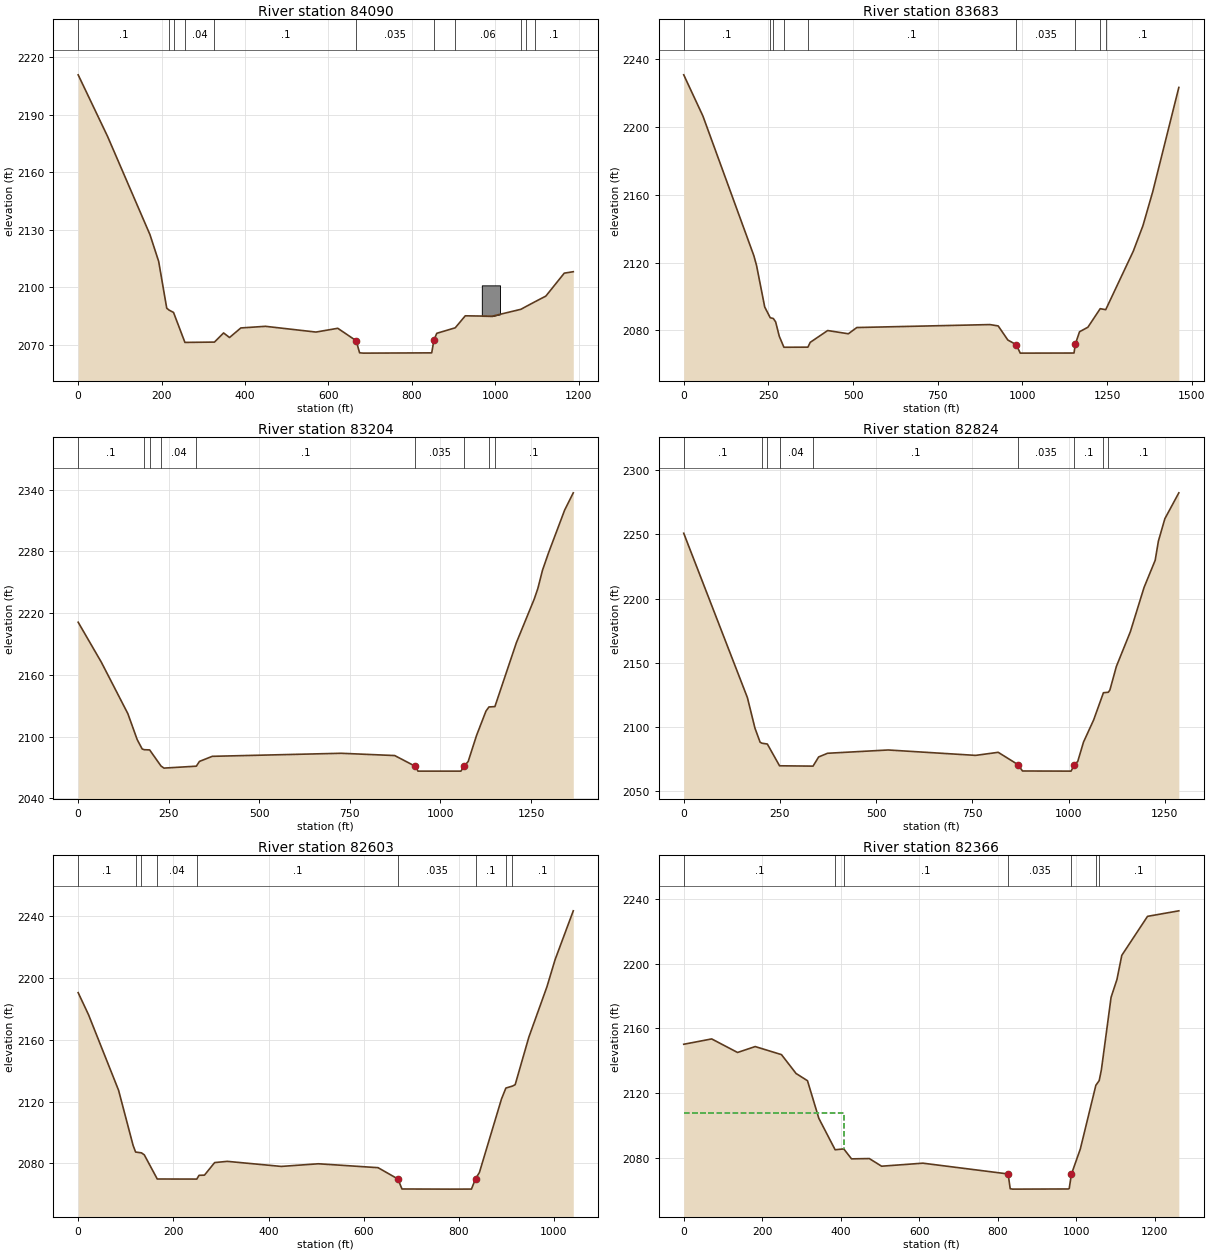
Type RM Length L Ch R = 1 ,84090   ,353.1,406.8,423.6
BEGIN DESCRIPTION:
channel burned 4.57':
lidar invert = 2070.22
interpolated invert = 2065.65
END DESCRIPTION:
XS GIS Cut Line= 3
2216387.96353418423596.2891984172216010.95685021423945.214036957
     2215939.539      424614.576
#Sta/Elev= 30
       0 2210.86    70.6 2178.67   172.1 2127.48     193 2113.49   212.3 2089.11
   217.7 2088.13   228.6 2086.88   255.9 2071.24   326.7 2071.41   348.6 2076.19
   362.8 2073.79     390 2078.79   448.9 2079.64     570 2076.64   622.3 2078.61
   666.5 2072.12   674.6 2065.83   683.4 2065.65   847.5 2065.79   852.8 2072.36
   859.6 2075.99   903.9 2078.86     928 2085.12   992.4 2084.91  1061.4 2088.52
  1073.4 2089.95  1094.1 2092.35  1121.1  2095.4  1165.3 2107.38  1186.9 2108.13
#Mann= 11 ,-1,0
       0      .1       0   217.7    .016       0   228.6      .1       0
   255.9     .04       0   326.7      .1       0   666.5    .035       0
   852.8      .1       0   903.9     .06       0  1061.4    .016       0
  1073.4     .06       0  1094.1      .1       0
#Block Obstruct= 1 ,-1
  967.64 1011.33 2101.01
Bank Sta=666.5,852.8
XS Rating Curve= 0 ,0
Exp/Cntr=0.3,0.1

Type RM Length L Ch R = 1 ,83683   ,212.7,479,559.6
BEGIN DESCRIPTION:
channel burned 3.09':
lidar invert = 2069.69
effective invert = 2066.6
END DESCRIPTION:
XS GIS Cut Line= 3
2216202.49160581423301.7244633362215643.00850394423802.403034978
2215510.27827857424501.336879955
#Sta/Elev= 30
       0 2230.68    56.8 2206.32   207.1 2124.06   215.1 2118.26   239.2 2093.81
   255.4 2087.48   264.7 2086.99   271.5 2084.99   282.2 2076.53   295.9 2070.06
   366.7 2070.12   373.5 2072.94   425.1 2079.92   486.2 2078.01   511.2 2081.69
   904.3 2083.43   928.7 2082.64   957.2 2074.33   981.9 2071.61   993.8  2066.6
  1152.6 2066.66  1156.7 2071.98  1168.9  2079.2  1193.6 2081.87    1230  2092.8
  1246.3 2092.23  1327.7 2126.71  1356.2 2141.76  1385.2 2161.84  1462.2 2223.25
#Mann= 9 ,-1,0
       0      .1       0   255.4    .016       0   264.7      .1       0
   295.9     .04       0   366.7      .1       0   981.9    .035       0
  1156.7      .1       0    1230    .016       0  1246.3      .1       0
Bank Sta=981.9,1156.7
XS Rating Curve= 0 ,0
Exp/Cntr(USF)=0,0
Exp/Cntr=0.3,0.1

Type RM Length L Ch R = 1 ,83204   ,224.3,379.5,402.4
BEGIN DESCRIPTION:
channel burned 2.66':
lidar invert = 2069.03
interpolated invert = 2066.37
END DESCRIPTION:
Node Name=G
XS GIS Cut Line= 2
  2216068.081251423197.5564383642214960.87595331423998.978178878
#Sta/Elev= 30
       0 2211.13    64.1 2172.19   137.2 2122.22   162.9 2097.07   176.7 2087.89
   182.6  2087.2   197.3    2087   228.8 2071.29   236.9 2069.31   326.2 2071.18
   334.8 2075.81   370.2 2080.76   725.8 2083.72   873.9 2081.51     931    2071
   938.1 2066.37  1056.7 2066.37  1065.3 2071.03  1076.7 2075.77  1099.6  2100.9
  1125.7  2124.7    1134 2128.76  1150.4  2129.1  1209.7 2191.23    1259 2233.67
  1268.9 2243.85  1281.9 2261.79  1298.5 2278.61    1343 2320.18  1366.8 2336.94
#Mann= 9 ,-1,0
       0      .1       0   182.6    .016       0   197.3      .1       0
   228.8     .04       0   326.2      .1       0     931    .035       0
  1065.3      .1       0    1134    .016       0  1150.4      .1       0
Bank Sta=931,1065.3
XS Rating Curve= 0 ,0
Exp/Cntr(USF)=0,0
Exp/Cntr=0.3,0.1

Type RM Length L Ch R = 1 ,82824   ,279.9,221,223.4
BEGIN DESCRIPTION:
channel burned 2.70':
lidaar invert = 2068.47
interpolated invert = 2065.77
END DESCRIPTION:
XS GIS Cut Line= 3
2215980.71452038423022.822977119 2215540.5206084423296.684075031
2214809.66430416423533.582325372
#Sta/Elev= 30
       0 2250.84   165.5 2122.94   185.1 2099.23   198.5 2088.27   203.2  2087.5
   217.3 2086.86     249 2069.92   336.1 2069.66   350.6 2076.79   373.8 2079.66
   531.4 2082.22   758.5 2078.02   817.3  2080.4   868.4 2070.88   880.4 2065.88
  1006.6 2065.77    1015 2070.65    1024 2073.31  1038.9 2088.33  1065.3 2105.59
  1090.7 2126.75  1103.4 2127.13  1107.5 2128.83  1124.3 2147.15  1160.6 2174.13
  1196.3 2208.66  1225.2 2229.78  1233.6 2244.71  1250.4 2262.16  1286.7 2282.27
#Mann= 9 ,-1,0
       0      .1       0   203.2    .016       0   217.3      .1       0
     249     .04       0   336.1      .1       0   868.4    .035       0
    1015      .1       0  1090.7    .016       0  1103.4      .1       0
Bank Sta=868.4,1015
XS Rating Curve= 0 ,0
Exp/Cntr(USF)=0,0
Exp/Cntr=0.3,0.1

Type RM Length L Ch R = 1 ,82603   ,350.8,237.4,206.7
BEGIN DESCRIPTION:
channel burned 4.96':
lidar invert = 2068.28
interpolated invert = 2063.32
END DESCRIPTION:
XS GIS Cut Line= 3
2215710.31292051422804.7147371732215337.22494676423137.071778702
2214819.17001446423292.515281864
#Sta/Elev= 30
       0 2190.59    21.7 2176.35    84.9 2127.38   115.4 2091.68   120.7 2087.34
     133 2086.82     139 2085.51   166.2 2069.88   249.3 2069.83     254 2072.27
   265.4 2072.38   286.8 2080.52   313.4 2081.31   426.8 2078.03   504.9 2079.74
   630.2 2077.22     672 2069.89   680.5 2063.41   781.5 2063.32   826.5 2063.35
   835.2 2070.12   843.2 2074.08   889.7 2121.79   898.9 2128.81   912.7 2130.08
   918.4    2131   947.1 2161.77   985.2 2194.46  1002.2 2211.91  1040.5 2243.61
#Mann= 9 ,-1,0
       0      .1       0   120.7    .016       0     133      .1       0
   166.2     .04       0   249.3      .1       0     672    .035       0
   835.2      .1       0   898.9    .016       0   912.7      .1       0
Bank Sta=672,835.2
XS Rating Curve= 0 ,0
Exp/Cntr=0.3,0.1

Type RM Length L Ch R = 1 ,82366   ,294,278.8,278.1
BEGIN DESCRIPTION:
channel burned 7.30':
lidar invert = 2068
effective invert = 2060.7
END DESCRIPTION:
XS GIS Cut Line= 3
2215760.61756439422522.1444054772215382.58844151422624.632301014
2214745.81938563423217.717991584
#Sta/Elev= 30
       0 2150.25    71.3 2153.55   137.2 2145.18   182.2 2148.83   249.1 2143.85
   286.4 2132.17   315.4 2127.72   344.4 2104.45   385.9 2085.03   407.9 2085.57
   427.7 2079.41     473  2079.6   504.3 2074.87   609.6 2076.74   826.8 2070.08
   826.8 2070.06   832.1 2060.96   838.1  2060.7   979.9  2060.8   982.5 2061.06
   988.1 2069.92  1010.8  2085.5  1050.4 2124.87  1058.9 2127.79  1064.5 2134.46
  1089.2 2179.28  1104.2 2190.32  1116.5 2205.22  1182.1 2229.33  1261.9 2232.74
#Mann= 7 ,-1,0
       0      .1       0   385.9    .016       0   407.9      .1       0
   826.8    .035       0   988.1      .1       0  1050.4    .016       0
  1058.9      .1       0
#XS Ineff= 2 , 0
          407.23 2107.85
Permanent Ineff=
       F       F
Bank Sta=826.8,988.1
XS Rating Curve= 0 ,0
Exp/Cntr(USF)=0,0
Exp/Cntr=0.3,0.1

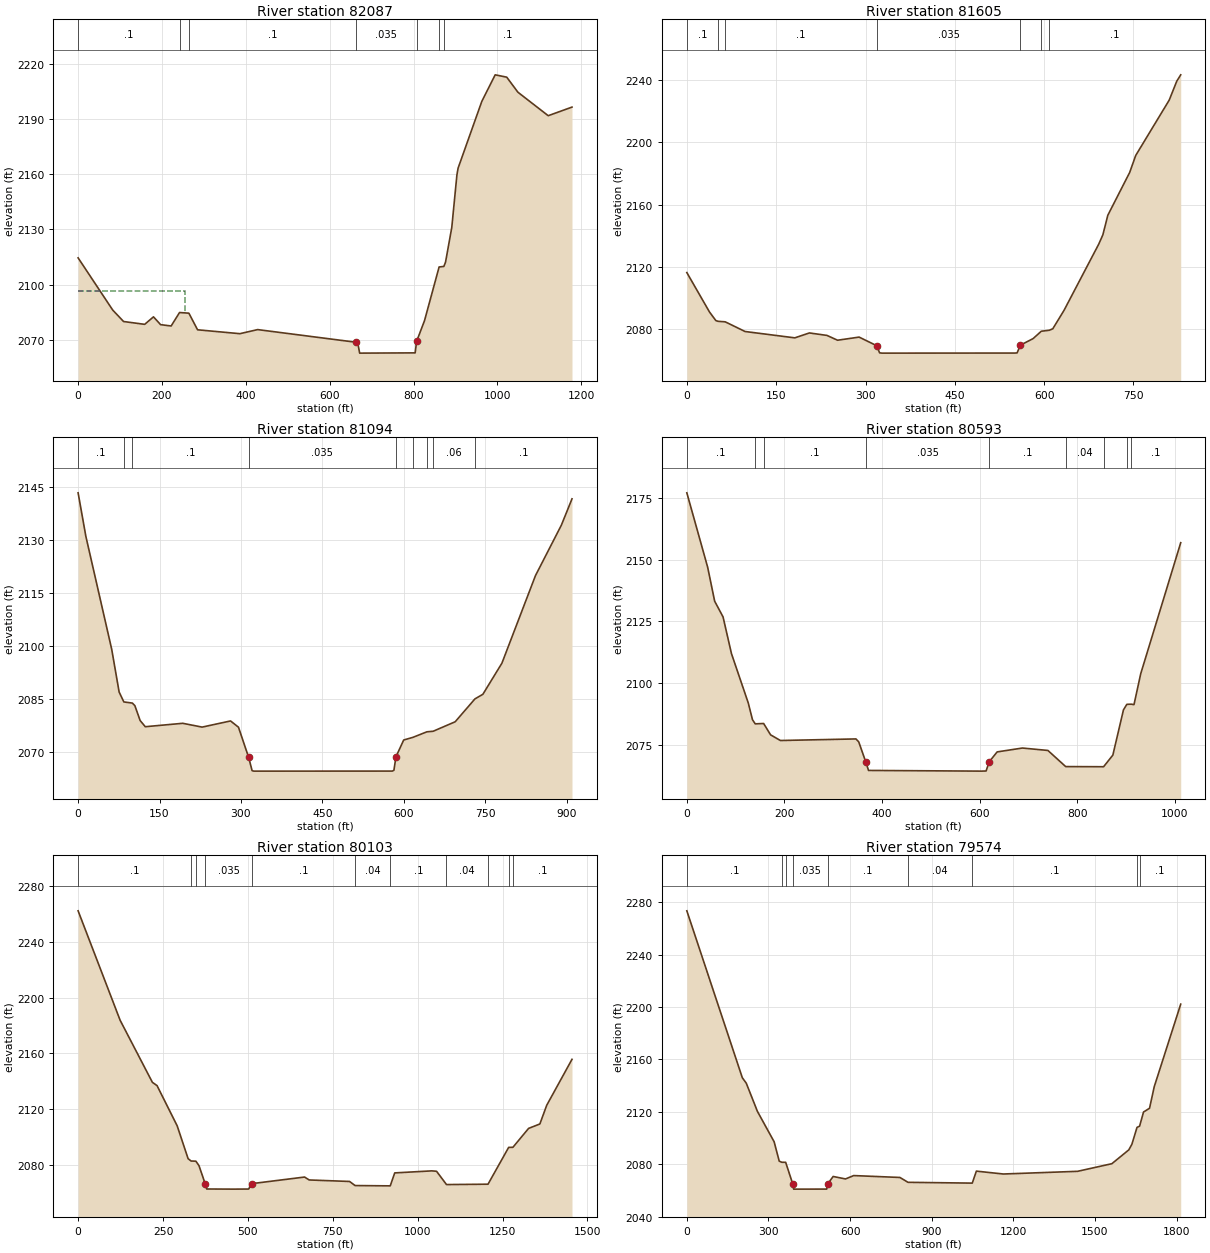
Type RM Length L Ch R = 1 ,82087   ,530.7,482.2,464.9
BEGIN DESCRIPTION:
channel burned 5.09':
lidar invert = 2067.79
interpolated invert = 2062.70
END DESCRIPTION:
XS GIS Cut Line= 3
2215161.50690605422166.0147016932215033.12151902422564.147641353
     2214487.561      423092.627
#Sta/Elev= 30
       0 2114.53    82.5 2086.15   108.4  2079.9   158.8 2078.36   179.8 2082.44
   196.7 2078.19   221.9 2077.47   241.9 2084.79   264.2 2084.44   284.9 2075.39
   385.8 2073.28   428.2  2075.5     663 2068.61     667 2068.18   671.5  2062.7
   803.9 2062.84   807.3 2069.05   826.2  2080.4     861 2109.57   872.3 2109.87
   876.3  2112.2   891.2 2131.05   903.4 2159.58   906.3 2163.37   962.8 2199.66
   994.7 2214.12  1022.3 2212.84  1048.9 2204.66  1121.2 2191.88  1177.9 2196.56
#Mann= 7 ,-1,0
       0      .1       0   241.9    .016       0   264.2      .1       0
     663    .035       0   807.3      .1       0     861    .016       0
   872.3      .1       0
#XS Ineff= 2 , 0
          256.11 2096.39
Permanent Ineff=
       F       F
Bank Sta=663,807.3
XS Rating Curve= 0 ,0
Exp/Cntr=0.3,0.1

Type RM Length L Ch R = 1 ,81605   ,524.7,511.6,507.3
BEGIN DESCRIPTION:
channel burned 3.12':
lidar invert = 2067.44
interpolated invert = 2064.32
END DESCRIPTION:
XS GIS Cut Line= 2
     2214701.609      422105.5492214220.32104797422780.853987514
#Sta/Elev= 30
       0 2116.21      38 2090.84    48.7 2085.29    52.4 2084.82    64.5 2084.47
    97.8 2078.24   181.3 2074.16   205.8 2077.32   235.3 2075.73   253.1 2072.63
   289.3 2074.64   318.8 2069.12   323.7 2064.49   327.7 2064.32   551.4 2064.37
   554.6 2064.48     560 2069.45   581.4 2073.66   595.2 2078.43   608.6 2079.04
   614.5 2080.02   633.2 2091.76   691.7 2134.56   698.6 2140.54   706.9 2153.12
   743.6 2180.69   753.7 2191.61     810 2227.29   822.6 2239.43   829.3 2243.57
#Mann= 7 ,-1,0
       0      .1       0    52.4    .016       0    64.5      .1       0
   318.8    .035       0     560      .1       0   595.2    .016       0
   608.6      .1       0
Bank Sta=318.8,560
XS Rating Curve= 0 ,0
Exp/Cntr=0.3,0.1

Type RM Length L Ch R = 1 ,81094   ,405.4,501,583.5
BEGIN DESCRIPTION:
channel burned 2.61':
lidar invert = 2067.06
interpolated invert = 2064.45
END DESCRIPTION:
XS GIS Cut Line= 3
     2214256.745      421813.199     2214009.927      422195.437
      2213763.11      422577.676
#Sta/Elev= 30
       0 2143.48    14.3 2131.11    61.9 2099.06    75.6 2086.91    84.3  2084.1
     100 2083.77   104.6 2083.04   114.3 2078.81   123.8 2077.06   192.8 2078.03
   228.5 2076.95   280.9  2078.7   295.5 2076.92   314.2 2068.37   320.6 2064.58
   323.8 2064.45     579 2064.46   581.9 2064.69   585.6  2068.5   599.9 2073.29
   616.7 2074.03   642.6 2075.61   654.3 2075.78   694.8 2078.47   731.1 2084.95
   745.8 2086.27   780.9 2095.11   842.7 2119.97   890.4 2134.29     910 2141.77
#Mann= 9 ,-1,0
       0      .1       0    84.3    .016       0     100      .1       0
   314.2    .035       0   585.6     .07       0   616.7     .06       0
   642.6    .016       0   654.3     .06       0   731.1      .1       0
Bank Sta=314.2,585.6
XS Rating Curve= 0 ,0
Exp/Cntr=0.3,0.1

Type RM Length L Ch R = 1 ,80593   ,479.3,489.9,518.2
BEGIN DESCRIPTION:
channel burned 1.46':
lidar invert = 2065.69
interpolated invert = 2064.23
END DESCRIPTION:
XS GIS Cut Line= 3
     2213997.025      421610.3972213440.74808315422012.391857839
2213264.75146774422286.030903189
#Sta/Elev= 30
       0 2177.03    42.7 2146.85      57 2133.11    74.2 2126.73    91.4 2111.88
   125.8 2091.88   134.5 2085.06   140.1 2083.39   157.3 2083.54   171.6 2078.93
   191.7 2076.64   346.4 2077.28   352.1  2076.1   366.4 2068.05   372.2 2064.51
   603.1 2064.23     613 2064.28   619.4 2068.03   635.7 2072.02   687.4 2073.59
   739.6 2072.61   776.1 2066.07   853.7 2066.01   872.7 2070.73   894.4 2089.05
   901.3  2091.3   910.2 2091.36     916 2091.19   929.8 2103.73  1011.7 2156.81
#Mann= 9 ,-1,0
       0      .1       0   140.1    .016       0   157.3      .1       0
   366.4    .035       0   619.4      .1       0   776.1     .04       0
   853.7      .1       0   901.3    .016       0   910.2      .1       0
Bank Sta=366.4,619.4
XS Rating Curve= 0 ,0
Exp/Cntr=0.3,0.1

Type RM Length L Ch R = 1 ,80103   ,534.3,528.9,572
BEGIN DESCRIPTION:
channel burned 2.05':
lidar invert = 2064.78
interpolated invert = 2062.73
END DESCRIPTION:
XS GIS Cut Line= 4
     2213807.594      421220.4322213111.52471375421605.564172303
2213030.14856582421776.2550617162212645.91093217422046.755010801
#Sta/Elev= 30
       0 2262.25   123.7 2183.82   218.8 2139.28   232.5 2136.94   291.9 2108.04
   323.9  2084.6   332.7 2082.87   346.8 2082.78   355.9  2079.6   374.2 2066.64
   378.8 2062.82   457.1 2062.73   502.2 2062.79512.78252066.704   666.8 2071.39
   680.5  2069.3   799.5 2068.22   815.7 2065.29   919.2 2065.07   932.5 2074.36
  1041.8 2075.82  1055.6 2075.53  1084.9    2066  1207.2 2066.26    1268 2092.65
  1280.5 2092.72  1326.7 2106.27  1359.9 2109.44    1380 2122.81  1454.5 2155.79
#Mann= 11 ,-1,0
       0      .1       0   332.7    .016       0   346.8      .1       0
   374.2    .035       0512.7825      .1       0   815.7     .04       0
   919.2      .1       0  1084.9     .04       0  1207.2      .1       0
    1268    .016       0  1280.5      .1       0
Bank Sta=374.2,512.7825
XS Rating Curve= 0 ,0
Exp/Cntr=0.3,0.1

Type RM Length L Ch R = 1 ,79574   ,394.5,380.1,275.6
BEGIN DESCRIPTION:
channel burned 3.08':
lidar invert = 2064.04
interpolated invert = 2060.96
END DESCRIPTION:
Node Name=F
XS GIS Cut Line= 4
     2213520.183      420748.1642212840.42270359421172.985534124
 2212589.0309682421195.7710590212212065.72251591421748.440091361
#Sta/Elev= 30
       0 2273.55   203.9 2146.07   218.5 2141.86   259.4 2120.35   320.8 2097.15
   339.6 2082.32   349.1 2081.47   363.2 2081.45389.1935 2064.95   392.6 2060.96
   514.2 2060.98517.89142064.953   537.7 2070.62   583.1 2068.74   613.3 2071.31
     783 2069.87     813 2066.16    1049 2065.55  1064.1 2074.71  1163.1 2072.51
    1436 2074.56  1562.1 2080.39  1624.3 2090.94  1635.7 2095.26  1654.5 2108.14
    1664 2109.07  1678.4 2119.86  1700.5 2122.72  1717.7 2139.15  1815.1 2202.27
#Mann= 9 ,-1,0
       0      .1       0   349.1    .016       0   363.2      .1       0
389.1935    .035       0517.8914      .1       0     813     .04       0
    1049      .1       0  1654.5    .016       0    1664      .1       0
Bank Sta=389.1935,517.8914
XS Rating Curve= 0 ,0
Exp/Cntr=0.3,0.1

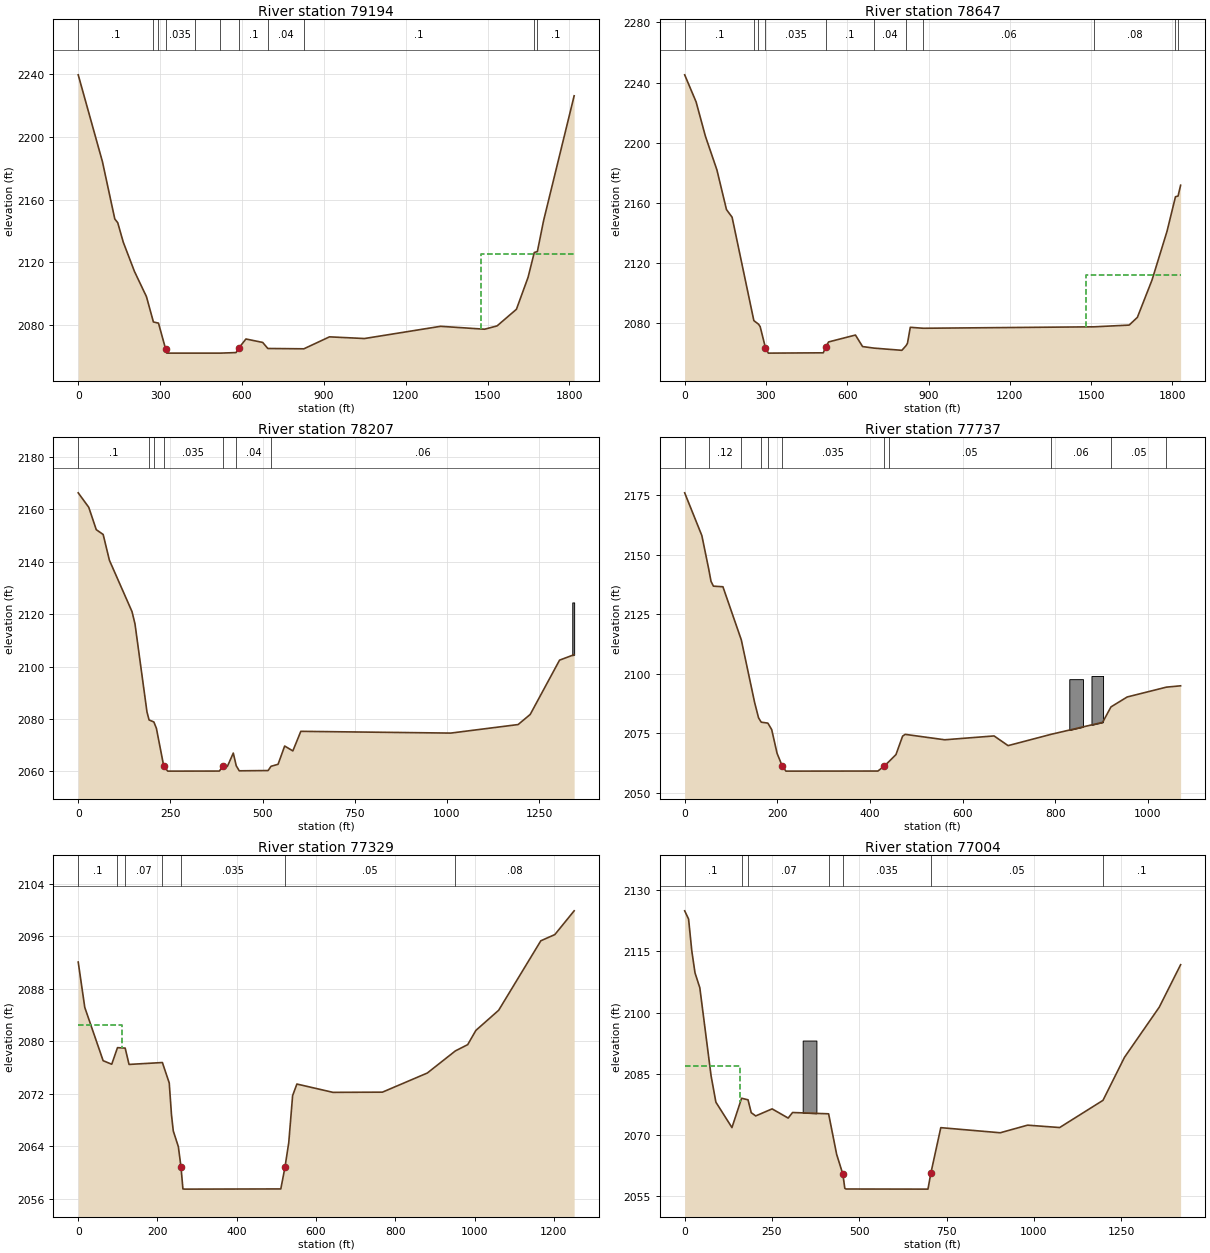
Type RM Length L Ch R = 1 ,79194   ,549.7,547.1,545.7
BEGIN DESCRIPTION:
channel burned 1.46':
lidar invert = 2063.26
effective invert = 2061.80
END DESCRIPTION:
XS GIS Cut Line= 2
2213247.84433321420409.0090760042211841.51376906421560.208874087
#Sta/Elev= 30
       0 2239.75    88.7 2184.27     134 2147.64   144.9 2145.17     165 2132.79
   206.3 2113.97     250 2097.95   275.6 2081.72   294.2 2080.97   320.1 2064.58
   325.2  2061.8   428.4  2061.8   521.3  2061.8   578.5 2062.15   588.9 2065.16
   614.7 2070.84     676 2068.64   694.9 2064.77     827 2064.56   920.8 2072.21
  1048.9 2071.13  1328.1 2078.95  1489.3 2077.09  1534.8 2079.19  1605.9 2089.84
  1648.5 2110.25  1671.3 2126.16  1682.6 2126.74  1705.4 2146.53  1817.4 2226.33
#Mann= 11 ,-1,0
       0      .1       0   275.6    .016       0   294.2      .1       0
   320.1    .035       0   428.4     .08       0   521.3    .035       0
   588.9      .1       0   694.9     .04       0     827      .1       0
  1671.3    .016       0  1682.6      .1       0
#XS Ineff= 2 , 0
                         1474.65         2125.15
Permanent Ineff=
       F       F
Bank Sta=320.1,588.9
XS Rating Curve= 0 ,0
Exp/Cntr(USF)=0,0
Exp/Cntr=0.3,0.1

Type RM Length L Ch R = 1 ,78647   ,444.3,439.1,424.7
BEGIN DESCRIPTION:
channel burned 1.46':
lidar invert = 2061.76
effective invert = 2060.3
END DESCRIPTION:
XS GIS Cut Line= 2
2212951.35349194 419949.019379022211537.47818567 421111.13464498
#Sta/Elev= 30
       0 2245.19    42.2 2227.19    76.6 2204.35   118.9 2182.06   154.3 2155.65
     175 2150.61   255.3 2081.89   272.4 2079.55   278.5 2077.94   297.9    2064
   308.9  2060.3   511.5 2060.51  520.062064.142     531 2067.73   630.2 2072.32
   656.5 2064.66   698.6 2063.63   801.5 2062.16     817 2065.27   822.2 2066.85
   832.6 2077.45   880.5 2076.82  1511.4 2077.78  1640.3 2078.93  1670.6 2084.05
  1724.6 2108.84  1780.1  2141.3  1811.2 2164.19  1820.8 2164.67  1830.2 2171.85
#Mann= 11 ,-1,0
       0      .1       0   255.3    .016       0   272.4    .045       0
   297.9    .035       0  520.06      .1       0   698.6     .04       0
     817      .1       0   880.5     .06       0  1511.4     .08       0
  1811.2    .016       0  1820.8      .1       0
#XS Ineff= 2 , 0
                          1480.8         2111.89
Permanent Ineff=
       F       F
Bank Sta=297.9,520.06
XS Rating Curve= 0 ,0
Exp/Cntr=0.3,0.1

Type RM Length L Ch R = 1 ,78207   ,460.8,470.1,505.5
BEGIN DESCRIPTION:
channel burned 0.06':
lidar invert = 2060.16
effective invert = 2060.1
END DESCRIPTION:
XS GIS Cut Line= 3
2212596.53489789419653.9879471712212044.78868836420151.804076072
 2211530.3786885420465.013390505
#Sta/Elev= 30
       0 2166.33    28.6  2160.8      49 2152.26    67.7 2150.43    84.6  2140.6
   145.9 2121.01     154 2116.34   186.6 2082.65   192.3 2079.62   205.2 2078.87
   212.1 2076.45   232.1 2061.97   242.9  2060.1     383 2060.13   392.9 2062.04
   404.7 2061.91   420.7 2066.99   428.7 2062.15   436.9 2060.22   515.1 2060.32
   523.1 2061.94   542.2 2062.71   560.1 2069.68   582.3 2067.82   603.9 2075.29
  1010.8 2074.62  1193.4 2077.88  1226.2 2081.74  1305.8 2102.46  1345.4 2104.55
#Mann= 7 ,-1,0
       0      .1       0   192.3    .016       0   205.2      .1       0
   232.1    .035       0   392.9      .1       0   428.7     .04       0
   523.1     .06       0
#Block Obstruct= 1 ,-1
  1340.3 1345.39 2124.49
Bank Sta=232.1,392.9
XS Rating Curve= 0 ,0
Exp/Cntr(USF)=0,0
Exp/Cntr=0.3,0.1

Type RM Length L Ch R = 1 ,77737   ,414.5,408.1,425
BEGIN DESCRIPTION:
channel burned 0.62':
lidar invert = 2059.62
effective invert = 2059.0
END DESCRIPTION:
XS GIS Cut Line= 2
2212285.39981733419334.5559311262211437.03816433419987.939600308
#Sta/Elev= 30
       0 2176.11    37.1 2158.11      52 2143.95    56.9 2138.83    62.1 2136.84
    82.6 2136.58   122.3 2114.21   151.1 2087.82   159.6 2081.37   165.3  2079.6
   179.6  2079.2   187.9 2076.48   199.5 2066.49   210.82061.086   218.6    2059
   417.3 2059.04   430.6  2061.1   440.8 2062.97   456.2 2065.96   470.5 2073.72
   476.1 2074.47   561.5 2072.19     668 2073.81   698.3 2069.73     791 2074.48
   902.4 2079.53   920.4 2086.02   955.4  2090.2  1040.1 2094.34  1070.8  2094.9
#Mann= 11 ,-1,0
       0      .1       0      52     .12       0   122.3    .025       0
   165.3    .016       0   179.6      .1       0   210.8    .035       0
   430.6      .1       0   440.8     .05       0     791     .06       0
   920.4     .05       0  1040.1     .06       0
#Block Obstruct= 2 ,-1
  830.42  859.96  2097.7  878.34  903.35 2099.03
Bank Sta=210.8,430.6
XS Rating Curve= 0 ,0
Exp/Cntr(USF)=0,0
Exp/Cntr=0.3,0.1

Type RM Length L Ch R = 1 ,77329   ,326,324.9,344.9
BEGIN DESCRIPTION:
channel burned 1.73':
lidar invert = 2059.16
interpolated invert = 2057.43
END DESCRIPTION:
XS GIS Cut Line= 2
2212129.83227705418967.4165360612211098.93804345419676.804519745
#Sta/Elev= 30
       0 2092.07    16.6 2085.14    62.9 2077.02    84.6 2076.48    99.1 2079.01
   118.5 2078.94   128.3 2076.45   212.4 2076.74   229.7 2073.62   235.4 2068.74
   239.9  2066.3   252.7  2063.9   259.4 2060.78   264.2 2057.46   269.1 2057.43
   511.2 2057.46   521.6 2060.73   531.3 2064.54     541 2071.69   551.8 2073.46
   642.9 2072.19   767.6 2072.22   880.9 2075.14   951.6 2078.51   982.8 2079.47
  1003.4 2081.64  1060.9 2084.71  1167.3 2095.31  1202.7 2096.26  1251.4 2099.88
#Mann= 7 ,-1,0
       0      .1       0    99.1    .016       0   118.5     .07       0
   212.4      .1       0   259.4    .035       0   521.6     .05       0
   951.6     .08       0
#XS Ineff= 2 , 0
          110.84 2082.44
Permanent Ineff=
       F       F
Bank Sta=259.4,521.6
XS Rating Curve= 0 ,0
Exp/Cntr(USF)=0,0
Exp/Cntr=0.3,0.1

Type RM Length L Ch R = 1 ,77004   ,366.1,413.5,435.6
BEGIN DESCRIPTION:
channel burned 1.99':
lidar invert = 2058.78
interpolated invert = 2056.79
END DESCRIPTION:
XS GIS Cut Line= 2
2212165.92918546418613.5952903662210931.00124203419315.133564484
#Sta/Elev= 30
       0 2124.93    11.2 2122.91    20.4 2115.11    29.6 2109.74    43.4 2106.08
    75.6 2084.54    89.4 2078.08   135.4 2071.86     163 2079.04   181.4 2078.66
   190.6 2075.51   203.4 2074.71   250.4 2076.44   296.4 2074.19     309 2075.55
   412.2 2075.23   435.2 2065.31   453.1 2060.42   458.6 2056.98   462.1 2056.82
   696.7 2056.79   705.1 2060.73   733.5 2071.84   903.7 2070.59   981.9 2072.45
  1073.9 2071.87    1198 2078.53  1259.6 2089.07  1359.1 2101.34  1420.3 2111.74
#Mann= 7 ,-1,0
       0      .1       0     163    .016       0   181.4     .07       0
   412.2      .1       0   453.1    .035       0   705.1     .05       0
    1198      .1       0
#XS Ineff= 2 , 0
          159.72 2086.88
Permanent Ineff=
       F       F
#Block Obstruct= 1 ,-1
  337.93  377.25 2093.17
Bank Sta=453.1,705.1
XS Rating Curve= 0 ,0
Exp/Cntr=0.3,0.1

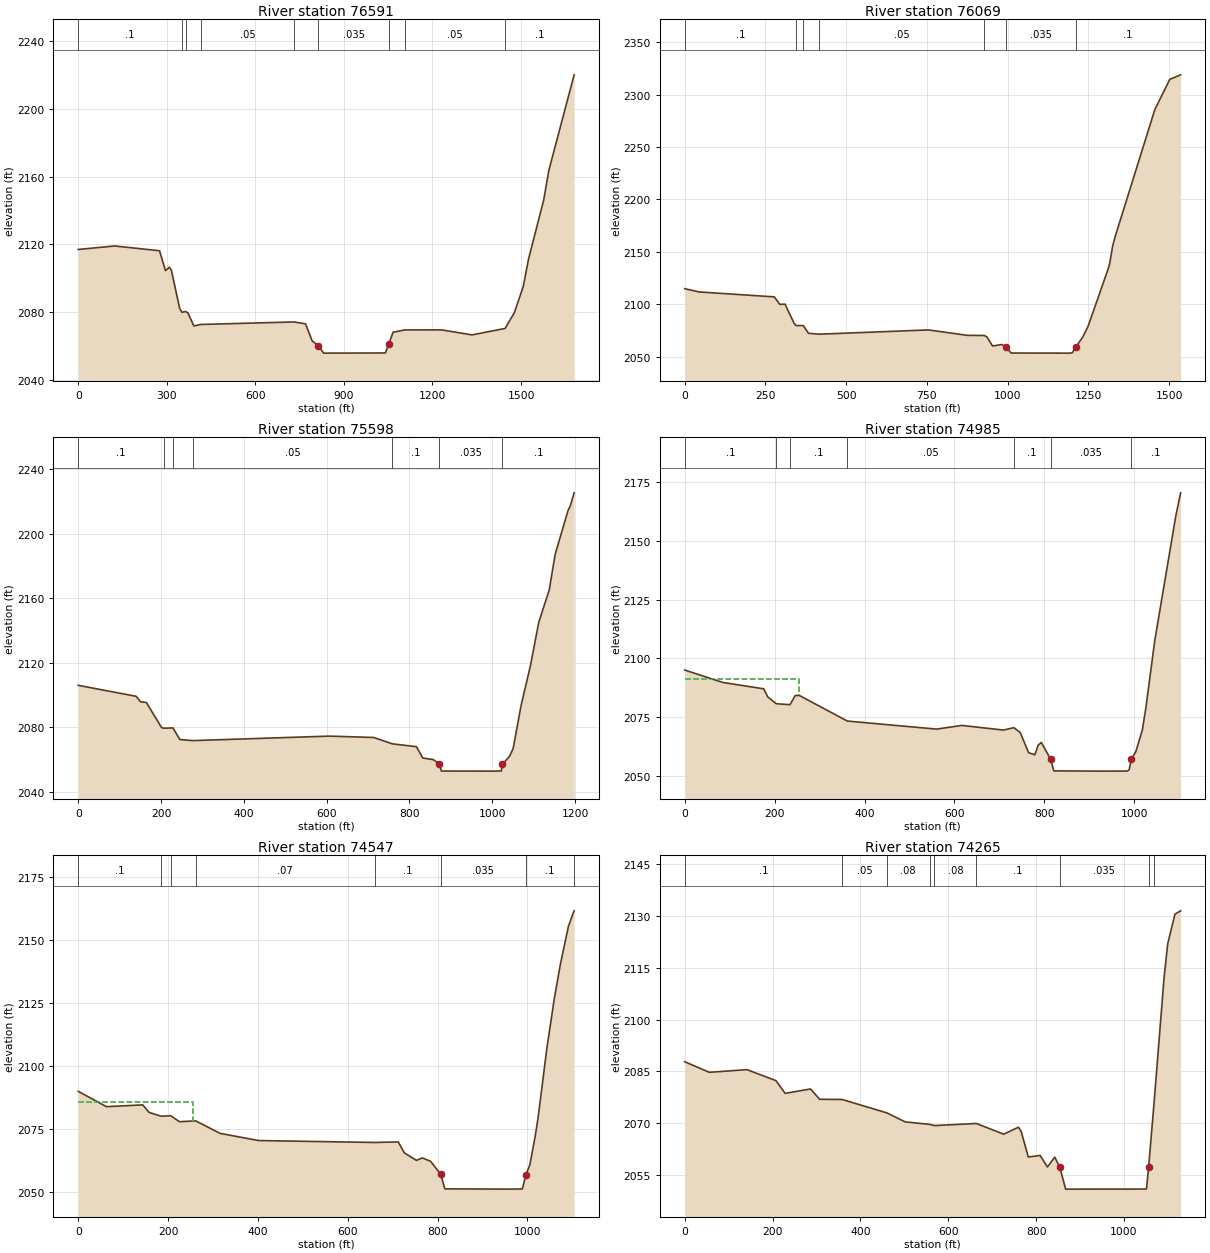
Type RM Length L Ch R = 1 ,76591   ,157.7,521.5,638.5
BEGIN DESCRIPTION:
channel burned 2.05':
lidar invert = 2058
interpolated invert = 2055.95
END DESCRIPTION:
XS GIS Cut Line= 3
2212383.18025794418408.5650161132211833.21683358418376.259882991
2210797.58636298418825.496629003
#Sta/Elev= 30
       0 2117.02   123.2 2119.08   275.5 2116.26   295.5 2104.55   308.8 2106.54
   315.5 2104.85   343.6 2082.33   351.6 2079.98   363.6 2080.48   371.6 2079.65
   391.7 2071.99   415.7 2072.84   730.8 2074.32   770.1 2073.19   792.6 2063.07
   813.7 2060.37   831.1 2055.95  1040.4 2056.04  1051.7 2061.21  1066.3 2068.21
  1105.9 2069.63  1230.5 2069.65  1333.9  2066.7  1445.9 2070.49  1476.9 2079.64
  1507.3 2095.13  1525.5 2111.51  1576.7 2146.19  1594.1 2163.63  1679.8 2219.91
#Mann= 9 ,-1,0
       0      .1       0   351.6    .016       0   363.6      .1       0
   415.7     .05       0   730.8      .1       0   813.7    .035       0
  1051.7      .1       0  1105.9     .05       0  1445.9      .1       0
Bank Sta=813.7,1051.7
XS Rating Curve= 0 ,0
Exp/Cntr=0.3,0.1

Type RM Length L Ch R = 1 ,76069   ,234.3,471.8,524.9
BEGIN DESCRIPTION:
channel burned 3.57':
lidar invert = 2057
interpolated invert = 2053.43
END DESCRIPTION:
Node Name=E
XS GIS Cut Line= 2
2212399.14354824418380.1229354142210944.50363709417887.550024203
#Sta/Elev= 30
       0  2114.9    45.4 2111.78   277.6  2107.1   294.5 2099.97   310.7 2100.19
   339.1 2081.75   345.2 2079.68   367.5 2079.69   383.2 2072.38     417 2071.49
   754.8 2075.57   875.4 2070.39     928 2070.27   936.4 2068.76   953.3 2060.24
   982.9 2061.65   994.4 2059.09    1011 2053.52  1194.1 2053.43  1200.3 2053.75
  1210.9 2059.04  1232.1 2068.43    1249 2078.81  1312.3 2134.53  1316.5 2139.47
    1325 2155.12  1332.8 2164.31  1455.9 2285.69  1502.3 2314.61  1535.8 2318.92
#Mann= 7 ,-1,0
       0      .1       0   345.2    .016       0   367.5      .1       0
     417     .05       0     928      .1       0   994.4    .035       0
  1210.9      .1       0
Bank Sta=994.4,1210.9
XS Rating Curve= 0 ,0
Exp/Cntr=0.3,0.1

Type RM Length L Ch R = 1 ,75598   ,488.5,612.5,635.7
BEGIN DESCRIPTION:
channel burned 3.46':
lidar invert = 2056.17
interpolated invert = 2052.71
END DESCRIPTION:
XS GIS Cut Line= 2
2212289.25609668418288.7794192672211425.38241124417459.099499966
#Sta/Elev= 30
       0 2105.94   140.1 2099.11   150.4 2095.75   164.6 2095.29   201.3 2079.72
     207 2079.32   228.9 2079.51   245.5 2072.31   276.6 2071.64   605.9 2074.43
   713.4 2073.59   758.7 2069.64   816.8 2067.86   832.2 2060.86   857.7 2059.85
   872.2 2057.17   877.2 2052.77  1001.9 2052.71  1021.8  2052.8  1024.6 2057.06
  1041.6 2061.86  1050.4 2066.64  1069.8 2093.63  1092.5 2118.44  1112.3 2144.96
  1137.7 2165.18  1151.9 2187.13    1183 2214.31    1189 2217.58  1197.8 2225.33
#Mann= 7 ,-1,0
       0      .1       0     207    .016       0   228.9      .1       0
   276.6     .05       0   758.7      .1       0   872.2    .035       0
  1024.6      .1       0
Bank Sta=872.2,1024.6
XS Rating Curve= 0 ,0
Exp/Cntr=0.3,0.1

Type RM Length L Ch R = 1 ,74985   ,425.5,438.1,446.4
BEGIN DESCRIPTION:
channel burned 3.41':
lidar invert = 2055.28
interpolated invert = 2051.87
END DESCRIPTION:
XS GIS Cut Line= 3
 2212553.6902218418070.4786928692212495.32781171417926.927204466
2212004.03370752417116.012700592
#Sta/Elev= 30
       0 2094.99      85 2089.69   175.7 2086.98   185.1 2083.47   203.8 2080.61
   234.3 2080.22   245.9  2084.1   254.6 2084.19   361.8 2073.23   560.4 2069.79
   616.5 2071.37   708.9 2069.38   732.2 2070.41   746.3 2068.36     765 2059.74
   778.9 2058.82   786.3 2062.97   793.4  2064.1813.79822056.971   821.1 2051.98
   928.7 2051.87   984.8 2051.89  988.65 2052.48993.39822056.895  1003.5 2060.18
  1017.9 2069.39  1025.6 2078.59  1045.6 2107.52  1092.4 2160.74  1103.1 2170.58
#Mann= 7 ,-1,0
       0      .1       0   203.8    .016       0   234.3      .1       0
   361.8     .05       0   732.2      .1       0813.7982    .035       0
993.3982      .1       0
#XS Ineff= 2 , 0
          254.38 2090.99
Permanent Ineff=
       F       F
Bank Sta=813.7982,993.3982
XS Rating Curve= 0 ,0
Exp/Cntr(USF)=0,0
Exp/Cntr=0.3,0.1

Type RM Length L Ch R = 1 ,74547   ,227.5,281.9,305.1
BEGIN DESCRIPTION:
channel burned 3.77':
lidar invert = 2054.97
effective invert = 2051.20
END DESCRIPTION:
XS GIS Cut Line= 3
2212862.35987121417887.3959238152212840.89535518417747.956639902
2212396.06390903 416893.86225307
#Sta/Elev= 30
       0 2090.02    62.9 2083.93   143.7 2084.64   157.7 2081.66   184.8 2080.14
     206 2080.34   225.4 2077.95   261.5  2078.3   315.8 2073.33   401.7 2070.48
   659.7 2069.72   712.5 2069.94     726 2065.59   753.1 2062.61   766.1 2063.58
   784.6 2062.24   807.2 2057.03   816.2 2051.31   960.5  2051.2   988.8 2051.28
   996.6 2056.77  1005.6 2060.97  1017.2 2071.98  1023.7 2079.39  1043.2 2106.86
  1059.7 2126.56  1073.3 2140.28  1091.3 2155.48  1103.8 2161.62  1104.1 2161.66
#Mann= 8 ,-1,0
       0      .1       0   184.8    .016       0     206      .1       0
   261.5     .07       0   659.7      .1       0   807.2    .035       0
   996.6      .1       0  1103.8      .1       0
#XS Ineff= 2 , 0
          255.55 2085.83
Permanent Ineff=
       F       F
Bank Sta=807.2,996.6
XS Rating Curve= 0 ,0
Exp/Cntr(USF)=0,0
Exp/Cntr=0.3,0.1

Type RM Length L Ch R = 1 ,74265   ,215.8,230.5,246.4
BEGIN DESCRIPTION:
xs 4 - channel burned 3.88':
lidar invert = 2054.73
interpolated invert = 2050.85
END DESCRIPTION:
XS GIS Cut Line= 4
2212872.90673913417873.3088946382212872.90673913417783.878814313
2212920.25207577417601.5115916892212694.04657847416780.859089879
#Sta/Elev= 30
       0 2087.78    56.1  2084.7   141.8 2085.47   207.9 2082.29   228.6  2078.6
   286.5 2079.87   307.4 2076.88   358.4 2076.83   460.3 2072.94   502.2 2070.33
   557.9 2069.61   568.6 2069.26   664.1 2069.87   726.3 2066.77   759.8 2068.79
   766.1 2067.56   782.3 2060.15   809.3 2060.62   825.9 2057.26   842.5 2060.11
   853.9 2057.19   867.4 2050.85  1049.9 2050.87  1051.5 2051.03 1056.34  2057.3
  1068.6 2075.79  1091.4 2112.04  1099.7 2121.96  1116.3 2130.55  1129.1 2131.49
#Mann= 9 ,-1,0
       0      .1       0   358.4     .05       0   460.3     .08       0
   557.9     .05       0   568.6     .08       0   664.1      .1       0
   853.9    .035       0 1056.34    .025       0  1068.6      .1       0
Bank Sta=853.9,1056.34
XS Rating Curve= 0 ,0
Exp/Cntr(USF)=0,0
Exp/Cntr=0.5,0.3

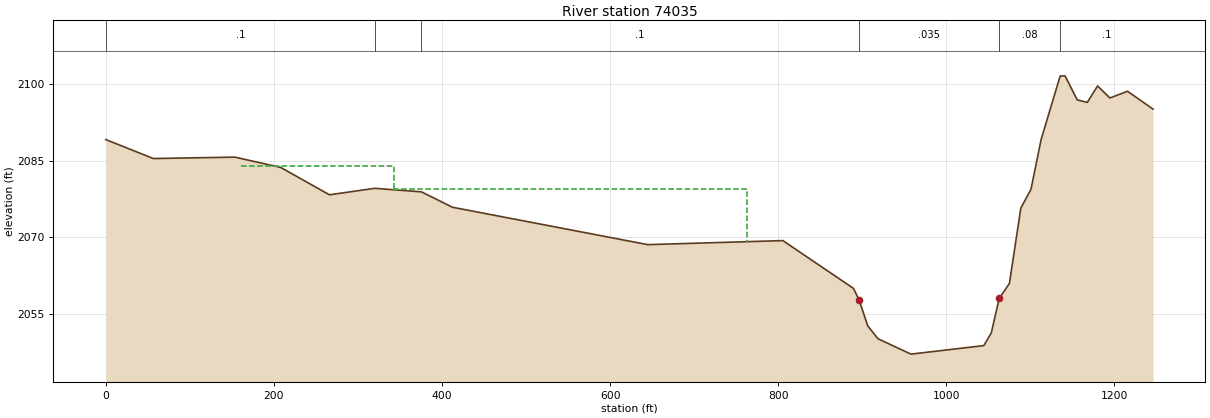
Type RM Length L Ch R = 1 ,74035   ,100,93.7,91.4
BEGIN DESCRIPTION:
structure xs 3
channel burned per survey points
END DESCRIPTION:
XS GIS Cut Line= 6
  2212879.829386417885.3480720332212886.95089782 417786.01576846
2213012.11136855417312.0278013472212999.04369516417127.213563492
2212943.03938066416751.9846563332212902.83889449416669.917308523
#Sta/Elev= 30
       0 2089.18    56.6 2085.46   153.5 2085.74   208.1 2083.72   266.1 2078.36
     320 2079.63   375.5 2078.94   412.5 2075.92   644.8  2068.6   805.5 2069.39
  889.37 2060.05     896 2057.85  906.52 2052.69  918.73 2050.16  957.92 2047.16
 1044.57 2048.83 1053.49 2051.33 1062.84 2058.06 1075.03    2061  1088.6 2075.75
  1100.7 2079.45  1112.8 2089.23  1135.4 2101.62  1141.2 2101.66  1155.7 2096.94
  1167.7 2096.46  1179.9 2099.68  1194.6 2097.32  1215.5 2098.64  1245.9 2095.14
#Mann= 6 ,-1,0
       0      .1       0     320    .016       0   375.5      .1       0
     896    .035       0 1062.84     .08       0  1135.4      .1       0
#XS Ineff= 3 ,-1
   160.9  342.31 2084.06  342.31     763 2079.48  1105.9  1245.9 2080.21
Permanent Ineff=
       F       F       F
Bank Sta=896,1062.84
XS Rating Curve= 0 ,0
Exp/Cntr(USF)=0,0
Exp/Cntr=0.5,0.3