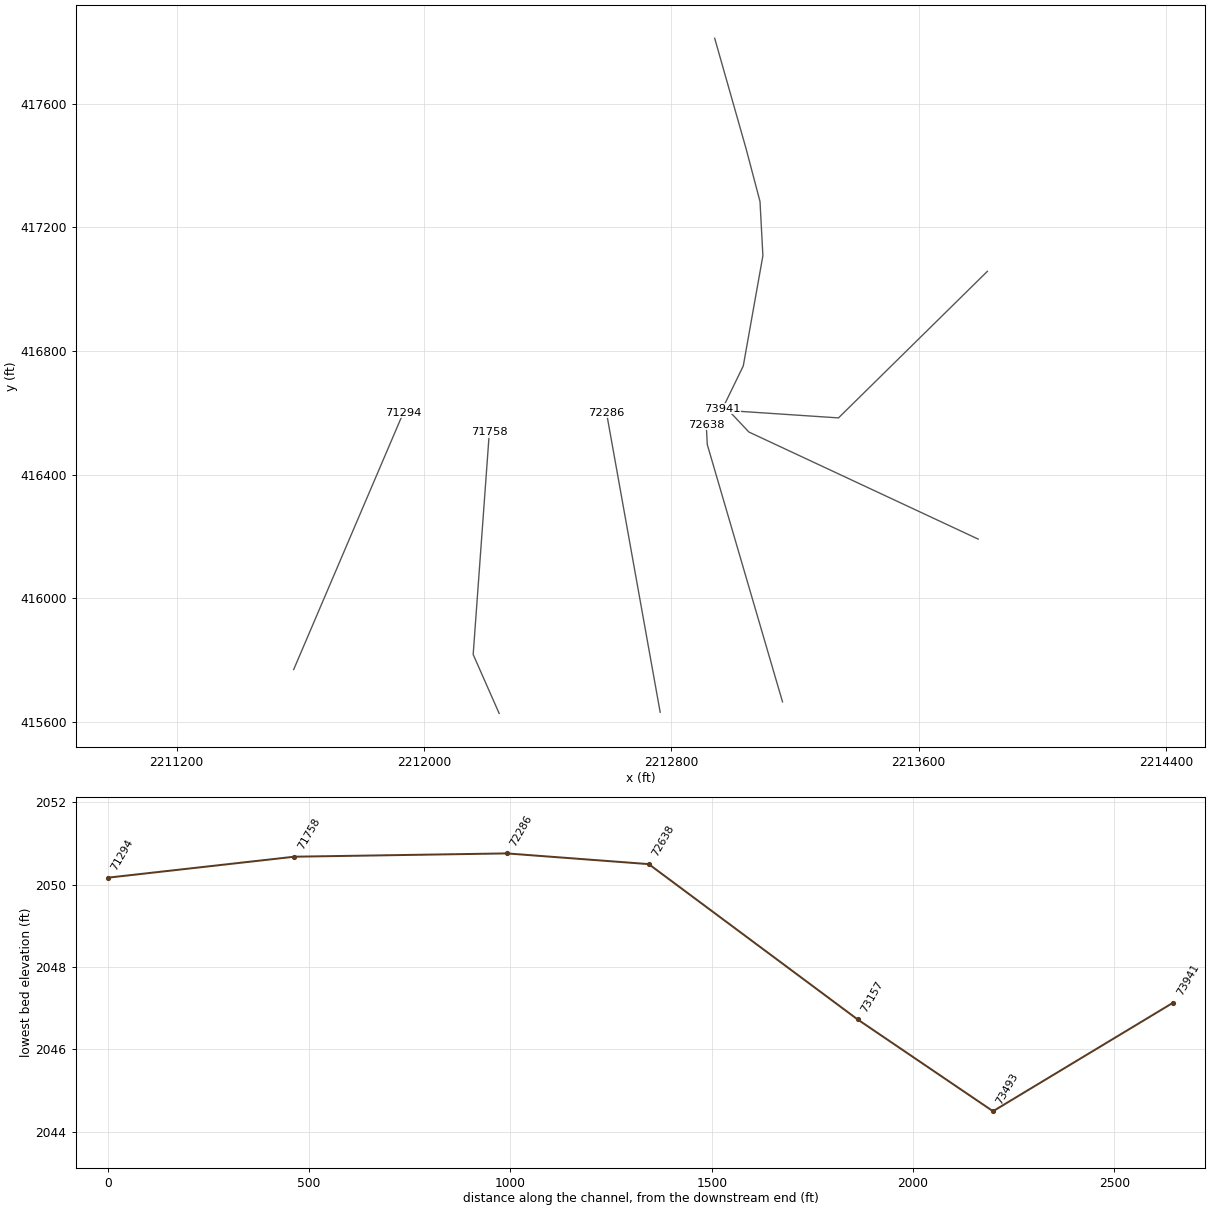
HEC-RAS study GRNBRRRV.prj: GRNBRRRV

--- GRNBRRRV.g01 (geometry) --- (continued)

Type RM Length L Ch R = 3 ,74000   ,,,
BEGIN DESCRIPTION:
Bridge No.: 54075GRL030 Greenbrier River Trail
JV notes: road deck updated per surveyed XS data points
channel burned per surveyed cross sections
structure opening based on survey data, photos, and aerial imagery
square nose pier per photos provided by survey and data provided in survey data viewer
surveyed inverts are 7-8' below inverts from lidar:
 surveyed invert US is 2047.23
 surveyed invert DS is 2047.14
END DESCRIPTION:
Bridge Culvert--1,0,-1,-1, 0
Deck Dist Width WeirC Skew NumUp NumDn MinLoCord MaxHiCord MaxSubmerge Is_Ogee
31,12,2.6,0, 375, 375, , , 0.98, 0, 0,0,,
   61.25  62.433  64.878  66.698  69.131  70.595  71.685  73.454   75.83  76.312
  79.171  81.658  82.528  84.888  87.747  89.227  91.632  93.464  95.925  96.618
  99.181  102.04 102.624 104.898 106.592 107.757 109.322 111.578 113.474 116.021
 119.191 122.719 124.909 126.538 127.767 129.418 131.525 133.485 136.117 139.202
 142.815 144.919 146.485 147.778 149.514 150.636 153.495 156.212 159.212 161.445
 162.911 164.929 167.788 169.609 171.419 173.505 176.405 179.222 181.392 183.006
  184.94 186.484 189.021 190.606 192.252 193.434 194.572 196.263 200.123 201.921
  203.79  204.75 205.674 207.579 209.559 210.408 211.225 213.237 215.328 216.066
 216.777 221.097 224.553 227.879 230.211 232.634 235.869 238.403 241.527 244.532
 247.185 249.941 252.842  255.71   258.5 261.478 264.158 267.301  269.85 271.717
 272.718 274.119 275.585 276.633 278.453 281.001 281.548 284.188 286.464 287.883
  292.79 294.764 296.295 298.525 300.122 301.646  304.26 308.528 309.995 311.042
 312.862  315.41 318.597 322.292 325.789  335.62 338.669 341.536 344.432 347.407
 350.382 351.565 353.357 356.332 358.756  360.39 362.281 365.256 369.215 371.206
 372.218  374.18 375.324  378.04  380.13 381.193 386.865 389.054 395.691 397.979
 399.142 404.516 406.903 409.878 411.842 413.341 417.061 418.883 421.356 421.995
 423.718 425.107  428.22 429.888 431.332 435.227 440.669 443.781 446.735 453.118
 455.484 458.243 459.342 462.455 465.567 468.282 469.751 471.792 478.016 481.128
 484.241 485.346 487.478  490.64 494.479 499.243 503.543 505.125 508.765 510.354
  514.52 516.446 518.687 519.672 522.773  527.02  529.35 531.187 532.576 535.354
 537.336  539.52 542.253 543.687 547.854 548.705  551.93 555.156 556.187 560.354
  564.52 565.908 568.059 571.611 574.052 576.731  580.75 584.769 588.788 591.866
 593.582 597.244 600.845 601.519 608.883 612.902 616.921  623.04 626.538 628.978
 632.997 637.016 641.019 644.683 645.342 649.022 653.154 661.088 664.871 669.028
 676.589 681.031 684.401 689.034 693.035 697.036   702.1 703.931 709.995 713.046
 720.582 724.777 725.316 730.318  732.25  759.23  797.23  797.23     798  924.59
  970.22  1071.9  1071.9 1072.47 1104.97 1136.661139.8041143.9311147.6851151.151
1152.6181156.9621160.3061163.3581165.6491169.4621175.5651178.6171181.6691184.721
1186.3681187.772  1193.9 1198.99 1199.981201.4321203.0011208.3361210.218 1211.96
 1213.751214.9461217.3671217.9321220.9181222.6731223.9051226.8911229.8771232.863
1235.4311236.6681238.8361241.8221244.8091247.7951250.7811253.4941253.9021256.754
 1259.741262.5261263.1181265.7121268.6991271.5571274.6711280.589 1283.631285.132
1286.6161289.6211292.5891295.5751298.6521301.5481302.9781307.2011310.5061311.901
1316.7151320.8241324.9011328.1611330.7961333.849 1335.941339.5381341.0831343.988
1345.226 1348.071350.9141356.7121359.4471361.6591365.1361366.8031369.4361370.824
1371.9461373.6681375.7981379.357 1382.161385.0561390.765 1393.621396.475 1399.33
1402.0021405.0391407.3451410.7491413.6041415.2331416.4591419.3141422.4111425.023
1427.8781432.4551433.5881437.4771438.601
2080.5712080.5582080.5882080.6312080.6572080.6352080.6492080.6322080.6362080.625
2080.6332080.6752080.6822080.6452080.6632080.6892080.6852080.6712080.706  2080.7
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                                                 2076.98 2076.98 2076.98  2076.9
 2076.87  2076.8  2076.8
      15  16.183  18.628  20.448  22.881  24.345  25.435  27.204   29.58  30.062
  32.921  35.408  36.278  38.638  41.497  42.977  45.382  47.214  49.675  50.368
  52.931   55.79  56.374  58.648  60.342  61.507  63.072  65.328  67.224  69.771
  72.941  76.469  78.659  80.288  81.517  83.168  85.275  87.235  89.867  92.952
  96.565  98.669 100.235 101.528 103.264 104.386 107.245 109.962 112.962 115.195
 116.661 118.679 121.538 123.359 125.169 127.255 130.155 132.972 135.142 136.756
  138.69 140.234 142.771 144.356 146.002 147.184 148.322 150.013 153.873 155.671
  157.54   158.5 159.424 161.329 163.309 164.158 164.975 166.987 169.078 169.816
 170.527 174.847 178.303 181.629 183.961 186.384 189.619 192.153 195.277 198.282
 200.935 203.691 206.592  209.46  212.25 215.228 217.908 221.051   223.6 225.467
 226.468 227.869 229.335 230.383 232.203 234.751 235.298 237.938 240.214 241.633
  246.54 248.514 250.045 252.275 253.872 255.396  258.01 262.278 263.745 264.792
 266.612  269.16 272.347 276.042 279.539  289.37 292.419 295.286 298.182 301.157
 304.132 305.315 307.107 310.082 312.506  314.14 316.031 319.006 322.965 324.956
 325.968  327.93 329.074  331.79  333.88 334.943 340.615 342.804 349.441 351.729
 352.892 358.266 360.653 363.628 365.592 367.091 370.811 372.633 375.106 375.745
 377.468 378.857  381.97 383.638 385.082 388.977 394.419 397.531 400.485 406.868
 409.234 411.993 413.092 416.205 419.317 422.032 423.501 425.542 431.766 434.878
 437.991 439.096 441.228  444.39 448.229 452.993 457.293 458.875 462.515 464.104
  468.27 470.196 472.437 473.422 476.523  480.77   483.1 484.937 486.326 489.104
 491.086  493.27 496.003 497.437 501.604 502.455  505.68 508.906 509.937 514.104
  518.27 519.658 521.809 525.361 527.802 530.481   534.5 538.519 542.538 545.616
 547.332 550.994 554.595 555.269 562.633 566.652 570.671  576.79 580.288 582.728
 586.747 590.766 594.769 598.433 599.092 602.772 606.904 614.838 618.621 622.778
 630.339 634.781 638.151 642.784 646.785 650.786  655.85 657.681 663.745 666.796
 674.332 678.527 679.066 684.068     686  712.98  750.98  750.98  751.75  878.34
  923.97 1025.65 1025.65 1026.22 1058.72 1090.411093.5541097.6811101.4351104.901
1106.3681110.7121114.0561117.1081119.3991123.2121129.3151132.3671135.4191138.471
1140.1181141.522 1147.65 1152.74 1153.731155.1821156.7511162.0861163.968 1165.71
  1167.51168.6961171.1171171.6821174.6681176.4231177.6551180.6411183.6271186.613
1189.1811190.4181192.5861195.5721198.5591201.5451204.5311207.2441207.6521210.504
 1213.491216.2761216.8681219.4621222.4491225.3071228.4211234.339 1237.381238.882
1240.3661243.3711246.3391249.3251252.4021255.2981256.7281260.9511264.2561265.651
1270.4651274.5741278.6511281.9111284.5461287.599 1289.691293.2881294.8331297.738
1298.976 1301.821304.6641310.4621313.1971315.4091318.8861320.5531323.1861324.574
1325.6961327.4181329.5481333.107 1335.911338.8061344.515 1347.371350.225 1353.08
1355.7521358.7891361.0951364.4991367.3541368.9831370.2091373.0641376.1611378.773
1381.6281386.2051387.3381391.2271392.351
2080.5712080.5582080.5882080.6312080.6572080.6352080.6492080.6322080.6362080.625
2080.6332080.6752080.6822080.6452080.6632080.6892080.6852080.6712080.706  2080.7
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                                                 2076.98 2076.98 2076.98  2076.9
 2076.87  2076.8  2076.8
Pier Skew, UpSta & Num, DnSta & Num=  ,938.34, 2 ,893.34, 2 , 0 , 0 , 0 ,,
       9       9
       0    2077
       9       9
       0    2077
BR Coef=-1 ,-1 , 0 ,, 0 ,,,0.8,0,2,0,
WSPro=,,,, 1 ,,,, 0 ,,,, 0 ,,,,-1 ,-1 ,-1 , 0 , 0 , 0 , 0 , 0
BR U #Sta/Elev= 398
       0 2089.18     4.2 2088.47     8.4 2087.99    12.2 2087.73    20.2 2087.49
    28.2 2087.12    32.3    2087    36.3 2086.63    40.3 2086.46    44.3 2086.23
    48.3  2085.9    52.3 2085.62    56.6 2085.46    60.4 2085.47    64.6 2085.62
    68.3 2085.51    72.4 2085.28    81.9 2085.16    82.8 2085.18    84.4 2085.14
    88.4 2084.94    92.4 2085.05    96.4 2085.22   100.5 2085.25   107.8 2085.16
   112.9 2085.24   117.6 2085.17   125.3 2085.34   133.6 2085.29   133.9  2085.3
   135.1 2085.32   137.2 2085.39   141.9 2085.39     147 2085.58   153.5 2085.74
   154.3 2085.73   158.4 2085.46     167 2085.19   169.8 2085.07     175 2084.97
   179.6  2084.7   187.4 2084.42   192.7 2083.92   195.7 2083.73   199.9 2083.76
   208.1 2083.72   212.3  2083.5   215.5 2083.11   216.4 2083.05   222.1 2082.99
   224.7    2083   228.9 2082.83   231.8 2082.31   241.6  2080.9   244.9 2080.27
   245.4 2080.15   248.2 2079.69   249.6 2079.39   253.7 2078.85     262 2078.49
   264.5 2078.44   266.1 2078.36     269 2078.36   270.3 2078.35   274.3 2078.63
   282.7 2079.07   284.1 2079.05   286.8 2079.05     291 2079.09   291.6 2079.12
   293.9 2079.24   295.1  2079.3     303 2079.18   303.4 2079.18   307.6 2079.15
   310.2 2079.19   315.8 2079.35     320 2079.63   323.3 2079.72   324.1 2079.76
   325.6  2079.8   332.4 2079.92   340.7 2079.94   349.4 2079.84   350.9 2079.82
   353.1 2079.77   353.9 2079.75   361.4 2079.63   362.4 2079.56   365.3 2079.52
   365.5  2079.5   365.7  2079.5   366.3 2079.48     369 2079.34   375.5 2078.94
   376.6 2078.91     378 2078.84   381.7 2078.58   382.1 2078.55   385.3 2078.24
   390.4 2078.12   391.8 2078.01   395.1 2077.65   397.1 2077.36   398.3  2077.2
   398.7 2077.16   399.3 2077.12   402.8  2076.9   404.9  2076.7   404.9 2076.69
     407 2076.43   408.1 2076.34   410.6 2076.05   411.1    2076   411.4 2075.99
   412.5 2075.92   417.9 2075.84   423.5 2075.56     431 2075.48   431.8 2075.45
   433.3 2075.36   434.2 2075.32     436 2075.19   437.5 2075.14   438.9 2075.07
   440.1 2075.02   443.3 2074.96   452.5 2075.05   456.7 2074.89   457.1 2074.88
   469.1 2074.61   472.7 2074.81   473.2 2074.83   473.5 2074.83   474.7  2074.8
   477.3 2074.69   480.1 2074.53   481.4 2074.46   483.4 2074.41   483.7 2074.41
   485.6 2074.39   489.7 2074.25   496.6 2073.91   497.9 2073.83   502.1 2073.72
   509.8 2073.39   511.2 2073.34   513.1 2073.28   516.4 2073.17   519.7 2073.08
   522.2 2073.03   522.7 2073.01     523    2073   524.1 2072.94   526.3 2072.83
   526.8 2072.82   530.9 2072.53   532.9 2072.44     535 2072.33   542.8 2072.09
   552.7 2071.68   555.2 2071.58   555.7 2071.55   557.1 2071.45   559.8 2071.27
   560.7 2071.24   562.6 2071.15     568 2071.03   569.1    2071   572.4 2070.87
   573.6 2070.82   575.7 2070.73   576.3  2070.7   577.2 2070.65     579  2070.5
   588.9 2070.14   589.8 2070.07   592.4 2069.89   592.7 2069.88     593 2069.87
   596.2 2069.83   596.7 2069.82   599.9 2069.86   600.7 2069.86   601.6 2069.84
   603.7 2069.81   610.2 2069.56   611.2  2069.5   612.7 2069.41   637.4 2068.85
   640.4 2068.85   640.8 2068.84   641.1 2068.83   644.8  2068.6   644.9  2068.6
   645.6 2068.59   648.8 2068.57   649.1 2068.57   652.8 2068.68   653.4 2068.69
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BR U #Mann= 6
       0      .1     320    .016   375.5      .1     896     .03 1062.84     .08
  1135.4      .1
BR D #Sta/Elev= 454
       0 2086.62     6.9 2086.54    19.4 2087.48    23.5  2087.9    27.7 2087.93
      36 2087.47    40.1 2087.42    44.3 2087.53    47.4 2087.45    52.6 2087.39
    58.3 2087.49    60.4 2087.49    66.8 2087.33    73.4 2087.22    81.7 2086.95
    85.9 2086.87    94.2 2086.34    99.2 2086.24   106.7 2085.95   123.3 2085.72
   131.6 2085.38   141.3 2084.81   148.3  2084.3   152.4 2084.22   156.6 2084.31
   157.5 2084.29   169.1 2083.85   173.7 2083.58   177.4  2083.5   181.5 2083.37
   185.7 2083.35     194 2082.89   202.3 2082.92   206.5 2082.31   210.6 2081.63
   214.8 2081.23     219 2080.91   222.3 2080.42   223.1 2080.34   227.3 2080.11
     232 2080.02   233.8 2080.04   238.4 2079.99   243.9 2079.88   248.1 2079.62
   252.2 2079.49   254.6 2079.63   256.4 2079.71   260.5 2079.54   264.3 2079.33
   264.7 2079.32   265.4 2079.29   267.6 2079.19   268.9 2079.14     273 2078.89
     277 2078.81   277.3  2078.8   280.5 2078.78   281.3  2078.8   282.8 2078.72
   283.8 2078.66   285.5  2078.6     287 2078.37   289.7 2078.04   293.5 2077.66
     298 2077.08   300.2 2076.87   303.2 2076.61     306 2076.27   306.3 2076.25
   306.4 2076.23     307 2076.17   309.7 2075.96   310.5 2075.88   311.8 2075.84
   312.9 2075.85   314.6 2075.75   316.2 2075.73   317.6 2075.53   318.8 2075.46
   321.6 2075.16   322.6 2075.14   325.9  2074.9   331.2 2074.38   332.3 2074.32
   335.1 2074.13   335.4 2074.11   338.8 2074.25   343.7 2074.22   345.3 2074.18
   346.7 2074.11   352.5 2074.02   356.2 2074.06   358.2 2074.18   358.3 2074.18
   360.4 2074.33   364.1 2074.44   364.5 2074.45   368.7 2074.12   372.8 2074.16
   377.7 2073.91   380.7 2073.83   381.1 2073.81   384.3 2073.68   385.2 2073.63
   389.4 2073.72   394.1 2073.99   397.6 2074.14   401.8 2074.07   403.7 2073.94
   403.9 2073.92   405.9 2073.79   418.3 2073.52   422.5 2073.32   426.6 2072.97
   426.8 2072.97   430.1 2073.07   430.7 2073.05   431.8    2073   433.4 2072.98
   434.9 2072.88   436.7 2072.89   437.4 2072.92   443.2 2073.04   446.5 2073.21
   447.3 2073.18   449.8 2072.94   451.4 2072.81   455.6  2072.4   456.3  2072.4
   459.1 2072.23   459.6 2072.22   459.7 2072.21   471.1 2072.49   472.1 2072.51
   472.7  2072.5   474.8 2072.46   475.9 2072.44   476.2 2072.43   476.8 2072.44
   479.2  2072.5   480.4 2072.52   484.5 2073.08   488.7 2073.55     489 2073.49
   492.8 2073.09   496.9 2072.36   501.1 2071.95   504.9 2071.99   505.2 2071.99
   505.4 2072.01   506.2 2072.05   508.7 2072.11   513.5  2072.4   521.8 2072.09
     525 2071.78   525.9 2071.72   528.3 2071.26     530    2071   531.6 2070.73
   534.2 2070.32   534.9 2070.24   537.5 2069.81   538.1 2069.71   538.3 2069.69
   542.4  2069.4   544.2 2069.46   546.6 2069.56   547.8 2069.77     548  2069.8
   554.6 2071.12   555.6 2071.11   557.8  2070.9   558.6 2070.88   559.4 2070.72
     562 2069.92   563.2 2069.73   566.2  2069.4   566.6 2069.36     567 2069.38
   570.5 2069.64   570.6 2069.65   570.8 2069.66     574 2069.85   574.6 2069.89
   574.7 2069.89   578.7 2069.44   582.2 2068.98   582.7 2068.92   583.1 2068.88
     586 2068.56   590.7 2068.12   591.6 2068.14   593.6 2068.26   594.7 2068.28
   595.8 2068.53   597.4 2068.92   598.7  2069.2   600.1 2069.24   601.2 2069.25
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BR D #Mann= 4
       0      .1   809.1     .03  1012.6     .08  1094.1      .1
BC Design=,, 0 ,, 0 ,,,,,,
BC Use User HTab Curves=0
BC User HTab FreeFlow(D)= 0

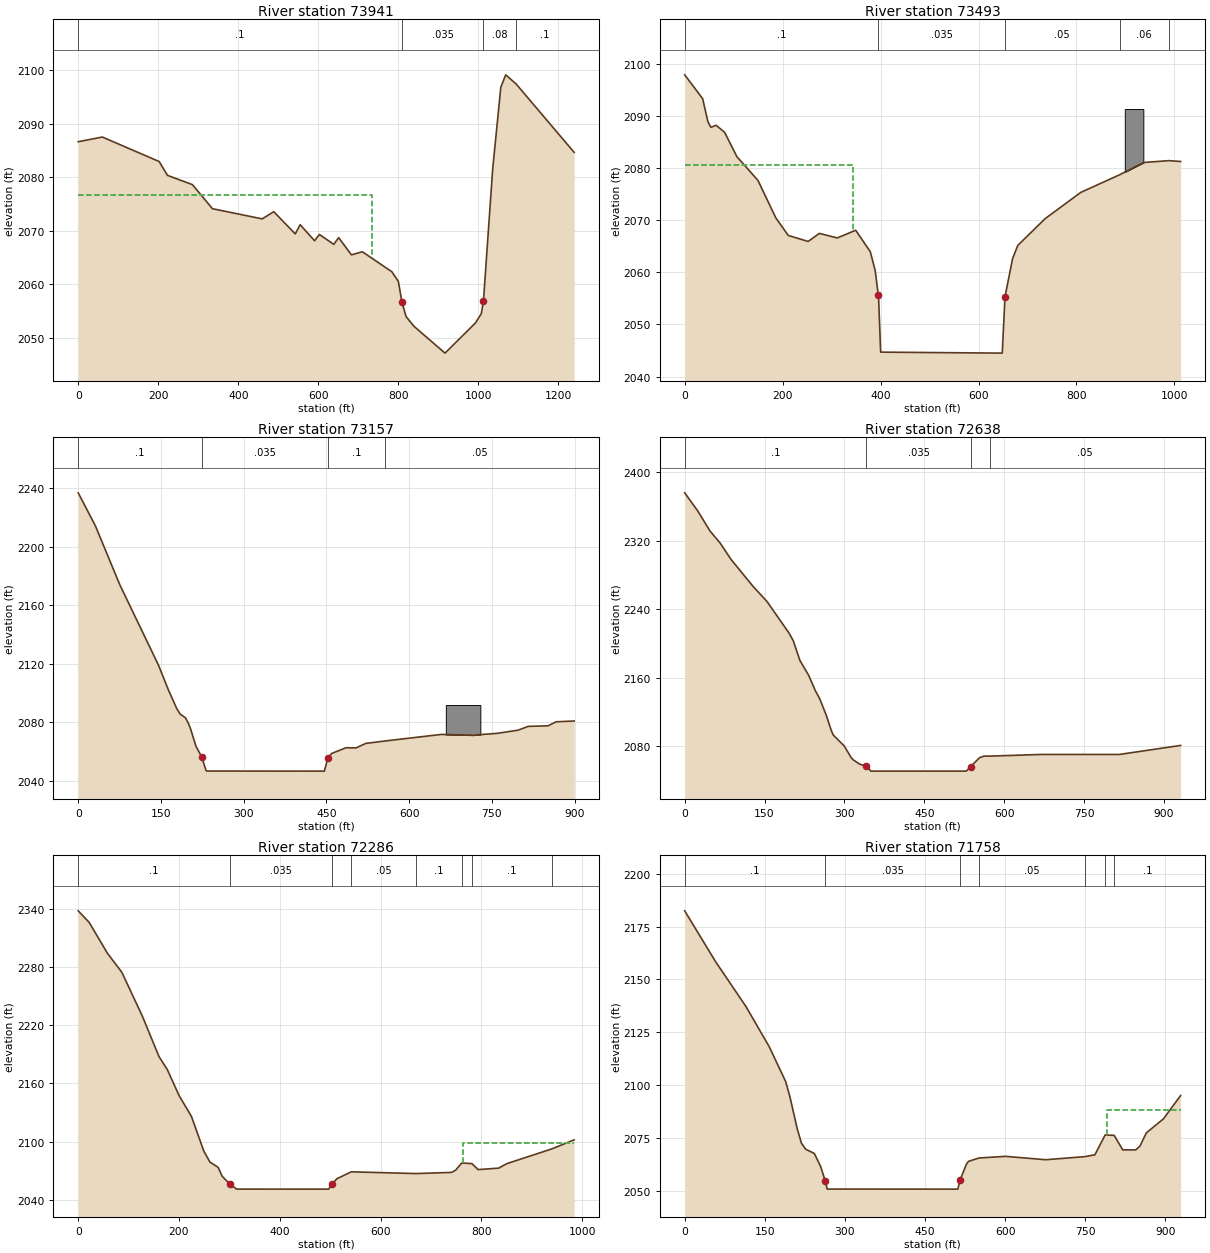
Type RM Length L Ch R = 1 ,73941   ,555.1,448,352.7
BEGIN DESCRIPTION:
structure xs 2
channel burned per survey points
END DESCRIPTION:
XS GIS Cut Line= 6
2212940.23714062417811.7973229652213041.98033628417453.905398084
2213086.78378788417284.025644096 2213096.1178403417108.545458658
2213032.64628387416751.9846563332212965.44110646416613.840680563
#Sta/Elev= 30
       0 2086.62    60.4 2087.49   202.3 2082.92   223.1 2080.34   285.5  2078.6
   335.4 2074.11   459.7 2072.21   488.7 2073.55   542.4  2069.4   554.6 2071.12
   590.7 2068.12   602.7  2069.3   638.7 2067.45   650.8 2068.71   682.8 2065.49
   710.1 2066.07   783.8 2062.34     800 2060.54   809.1 2056.61  819.49 2053.94
  839.21 2052.14  916.61 2047.14  993.01 2052.81  1007.2  2054.5  1012.6 2056.79
  1035.7  2081.5    1056 2096.76  1068.2 2099.11  1094.1 2097.42  1239.3 2084.63
#Mann= 4 ,-1,0
       0      .1       0   809.1    .035       0  1012.6     .08       0
  1094.1      .1       0
#XS Ineff= 2 , 0
           733.6  2076.6    1043          2079.9
Permanent Ineff=
       F       F
Bank Sta=809.1,1012.6
XS Rating Curve= 0 ,0
Exp/Cntr(USF)=0,0
Exp/Cntr=0.5,0.3

Type RM Length L Ch R = 1 ,73493   ,549.8,336.3,137.4
BEGIN DESCRIPTION:
xs 1 - channel burned 9.73':
lidar invert = 2054.23
effective invert = 2044.50
END DESCRIPTION:
XS GIS Cut Line= 3
2213822.30711833417058.1415756072213340.67001362416583.971712829
2213004.64412661416606.373438629
#Sta/Elev= 30
       0 2097.85    36.7 2093.28    47.4 2088.87    53.5 2087.78    64.1 2088.18
    81.4 2086.85   106.8 2082.14   149.6 2077.62     186 2070.45   211.5 2067.06
   252.2 2065.91     275 2067.45   311.7 2066.58   349.2 2068.06   379.1 2063.93
   389.1  2060.3   395.4  2055.6   395.9 2055.33  400.01 2045.05   400.5 2044.69
   648.5  2044.5   654.1 2055.31   669.7 2062.66   680.4 2065.17   736.5 2070.31
     809 2075.32   887.9 2078.68   937.1 2081.04   988.7  2081.4  1012.7 2081.24
#Mann= 5 ,-1,0
       0      .1       0   395.4    .035       0   654.1     .05       0
   887.9     .06       0   988.7      .1       0
#XS Ineff= 2 , 0
          344.11 2080.55
Permanent Ineff=
       F       F
#Block Obstruct= 1 ,-1
  898.68  936.59 2091.29
Bank Sta=395.4,654.1
XS Rating Curve= 0 ,0
Exp/Cntr(USF)=0,0
Exp/Cntr=0.3,0.1

Type RM Length L Ch R = 1 ,73157   ,627.5,518.5,287.4
BEGIN DESCRIPTION:
channel burned 7.33':
lidar invert = 2054.06
interpolated invert = 2046.73
END DESCRIPTION:
Node Name=D
XS GIS Cut Line= 3
 2213792.4381506416191.9415113192213050.84600112 416538.25631377
2212995.69543642416596.883045016
#Sta/Elev= 30
       0 2236.77    31.2 2214.18    75.3 2174.08   145.6 2119.02   163.6 2102.12
   178.7 2089.38   184.7 2085.74   194.5 2083.12   199.7 2079.37   203.4 2075.96
   213.3 2063.89223.89992056.335   231.8 2047.08   232.8  2046.8   420.4 2046.73
   446.2 2046.73452.69982055.868   459.4 2058.79   485.6  2062.7   503.6 2062.57
   521.2 2065.65   556.5 2067.33   658.1 2071.79   715.5 2071.26   759.6 2072.54
     797 2074.65   815.9 2077.29   851.6 2077.67   866.4 2080.41     899 2080.95
#Mann= 4 ,-1,0
       0      .1       0223.8999    .035       0452.6998      .1       0
   556.5     .05       0
#Block Obstruct= 1 ,-1
  666.35  728.93 2091.87
Bank Sta=223.8999,452.6998
XS Rating Curve= 0 ,0
Exp/Cntr(USF)=0,0
Exp/Cntr=0.3,0.1

Type RM Length L Ch R = 1 ,72638   ,361.5,352.6,325.4
BEGIN DESCRIPTION:
channel burned 3.25':
lidar invert = 2053.75
effective invert = 2050.50
END DESCRIPTION:
XS GIS Cut Line= 3
2213159.58939674415665.5009550062212916.29028666416497.535505445
2212912.88139126416561.895348612
#Sta/Elev= 30
       0 2376.14    24.7 2354.83    47.6 2331.46      67 2317.03    87.2 2298.08
   128.3 2266.76   154.7 2248.93     196 2211.99   203.9 2203.13   216.4 2179.96
     233 2162.38   245.5  2144.5   253.9 2134.76   266.4 2115.05   274.7  2099.1
   278.9 2092.82   299.7  2079.9   312.2 2066.75   316.4 2063.77   328.2 2058.78
341.19942056.157   349.7  2050.5   528.9  2050.5 536.9992055.828   553.9 2066.31
   562.3 2068.09   573.2 2068.04   670.6 2070.04   816.5 2070.03   931.3 2080.57
#Mann= 4 ,-1,0
       0      .1       0341.1994    .035       0 536.999      .1       0
   573.2     .05       0
Bank Sta=341.1994,536.999
XS Rating Curve= 0 ,0
Exp/Cntr(USF)=0,0
Exp/Cntr=0.3,0.1

Type RM Length L Ch R = 1 ,72286   ,554.5,527.2,453.2
BEGIN DESCRIPTION:
channel burned 2.71':
lidar invert = 2053.47
interpolated invert = 2050.76
END DESCRIPTION:
XS GIS Cut Line= 2
2212763.82557426415631.898366305 2212590.2121993416600.773007179
#Sta/Elev= 30
       0 2338.57    21.6 2326.72    58.2 2294.56    86.6 2275.02   127.3 2229.68
   160.4 2187.76   176.6 2174.65   200.4 2147.32   224.8 2125.91   249.2 2090.21
   261.4 2078.75   277.6 2073.34   285.8 2064.06   300.6  2056.2   314.2 2050.79
   407.7 2050.76   497.1 2050.76   503.9 2055.91   513.3 2061.45   541.8 2068.66
   670.4 2066.86   740.9 2068.04     749 2070.32   761.2 2077.79   781.5 2077.11
   793.7 2070.95   834.4 2072.48   850.6  2077.1     940 2092.36   984.3 2101.74
#Mann= 8 ,-1,0
       0      .1       0   300.6    .035       0   503.9      .1       0
   541.8     .05       0   670.4      .1       0   761.2    .016       0
   781.5      .1       0     940     .05       0
#XS Ineff= 2 , 0
                          764.51         2098.17
Permanent Ineff=
       F       F
Bank Sta=300.6,503.9
XS Rating Curve= 0 ,0
Exp/Cntr(USF)=0,0
Exp/Cntr=0.3,0.1

Type RM Length L Ch R = 1 ,71758   ,511.1,463.8,351.6
BEGIN DESCRIPTION:
channel burned 2.38':
lidar invert = 2053.06
interpolated invert = 2050.68
END DESCRIPTION:
XS GIS Cut Line= 3
 2212242.9854494415628.1647453382212158.97897764415818.579414643
2212211.24967118416537.301450744
#Sta/Elev= 30
       0  2182.5    57.9 2158.42   114.8 2137.16   158.5 2118.07   189.1 2101.65
   197.1 2094.42   210.7 2079.33   218.7 2072.42   226.6 2069.59   242.8 2067.58
   254.8 2061.29   262.9 2054.74   266.9 2050.71   511.5 2050.68   515.5 2054.84
   527.6 2062.51   531.6 2063.85   551.3 2065.43   600.5 2066.21     676 2064.61
     750 2066.08   768.2 2066.96   787.4 2076.35   804.3 2076.15   820.3 2069.29
   844.4 2069.25   852.4 2070.98   864.5 2077.32   896.5 2083.95   928.7 2095.01
#Mann= 7 ,-1,0
       0      .1       0   262.9    .035       0   515.5      .1       0
   551.3     .05       0     750      .1       0   787.4    .016       0
   804.3      .1       0
#XS Ineff= 2 , 0
                          790.99         2088.27
Permanent Ineff=
       F       F
Bank Sta=262.9,515.5
XS Rating Curve= 0 ,0
Exp/Cntr(USF)=0,0
Exp/Cntr=0.3,0.1

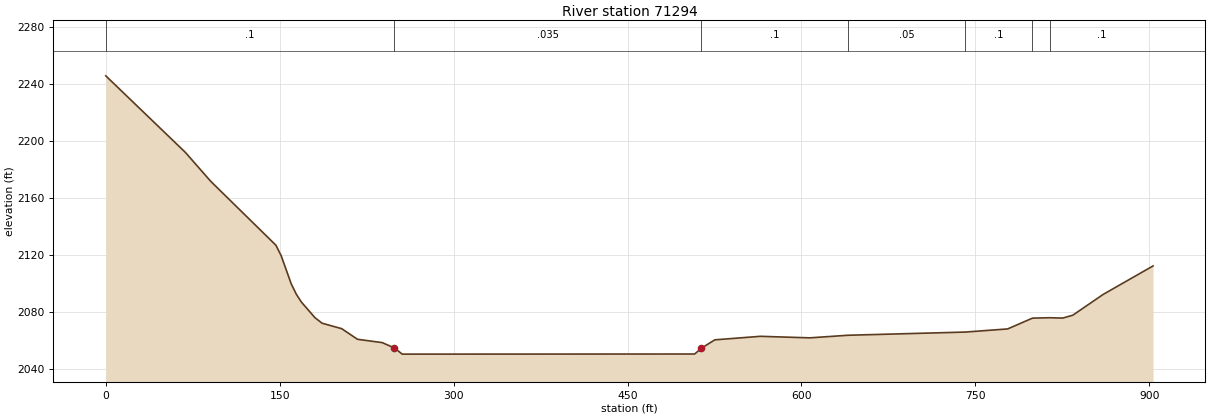
Type RM Length L Ch R = 1 ,71294   ,492.2,491.7,417.5
BEGIN DESCRIPTION:
channel burned 2.49':
lidar invert = 2052.66
interpolated invert = 2050.17
END DESCRIPTION:
XS GIS Cut Line= 2
2211578.40091731415770.0423420752211933.09490915416600.773007179
#Sta/Elev= 30
       0 2245.78    68.7 2191.93    90.4 2171.74   146.8 2126.67   151.3 2119.29
     160 2099.48   164.3 2092.34   168.7 2086.77   180.5 2075.73   186.6 2071.89
   203.5 2068.06   217.1  2060.6   238.4 2058.27     249 2054.49   255.7 2050.17
   507.9 2050.25   513.8 2054.36   525.3 2060.21   564.6 2062.69   607.2 2061.61
   640.1 2063.43   741.3 2065.67   777.9 2067.88   799.3 2075.46   799.3 2075.47
   814.5 2075.75   825.4  2075.5   834.1 2077.53   860.2  2092.1   903.3 2112.15
#Mann= 7 ,-1,0
       0      .1       0     249    .035       0   513.8      .1       0
   640.1     .05       0   741.3      .1       0   799.3    .016       0
   814.5      .1       0
Bank Sta=249,513.8
XS Rating Curve= 0 ,0
Exp/Cntr(USF)=0,0
Exp/Cntr=0.3,0.1