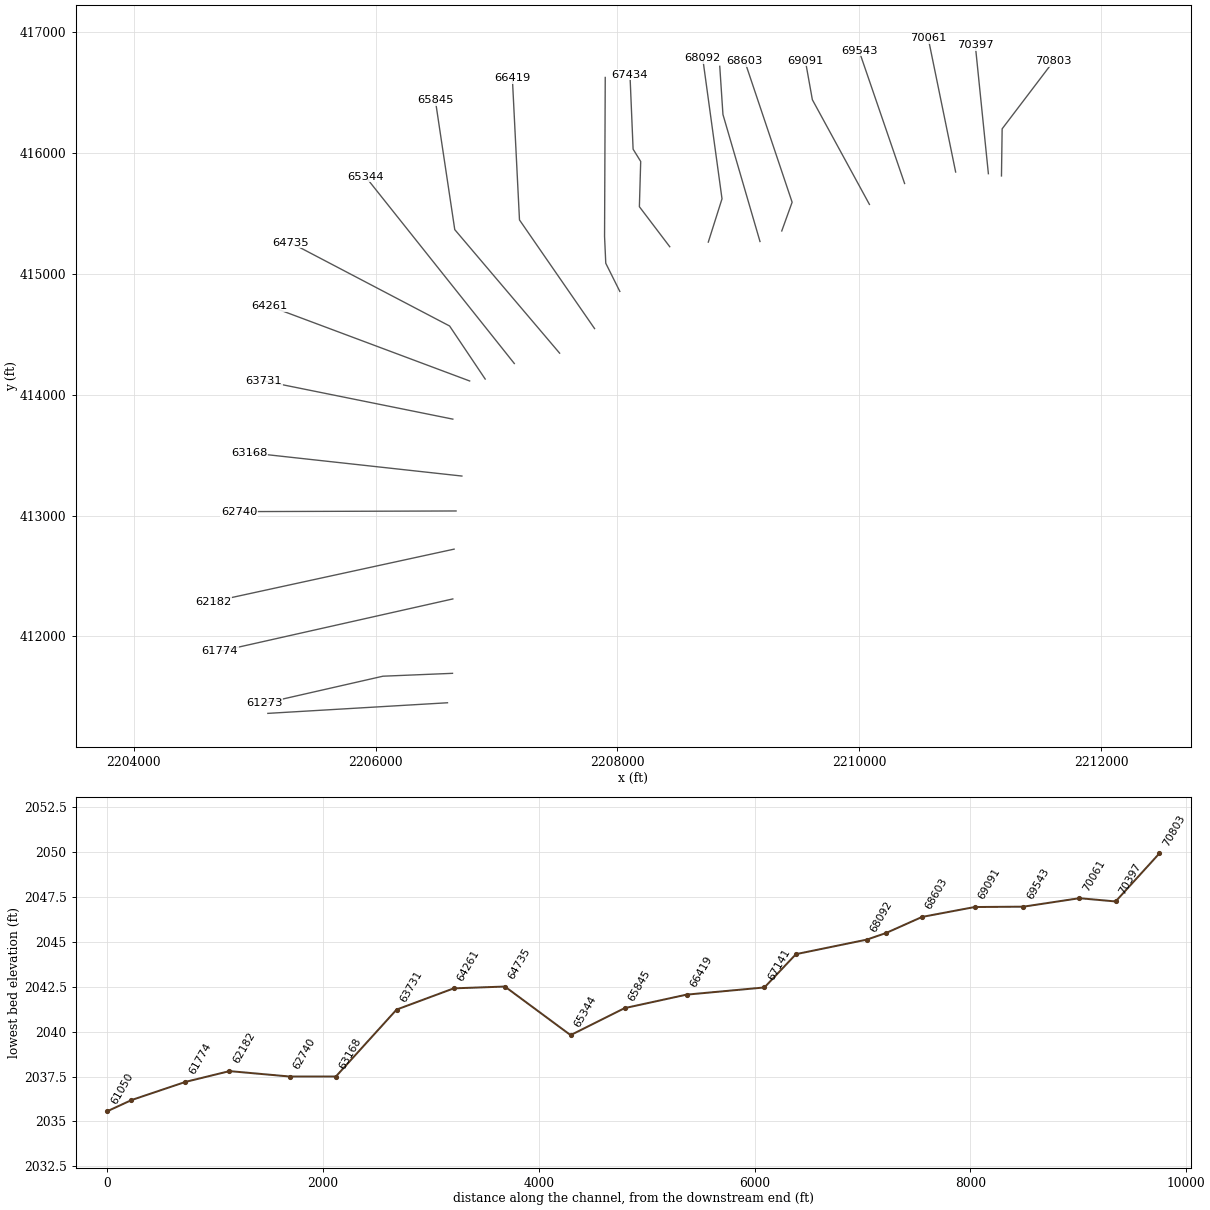
HEC-RAS study GRNBRRRV.prj: GRNBRRRV

--- GRNBRRRV.g01 (geometry) --- (continued)

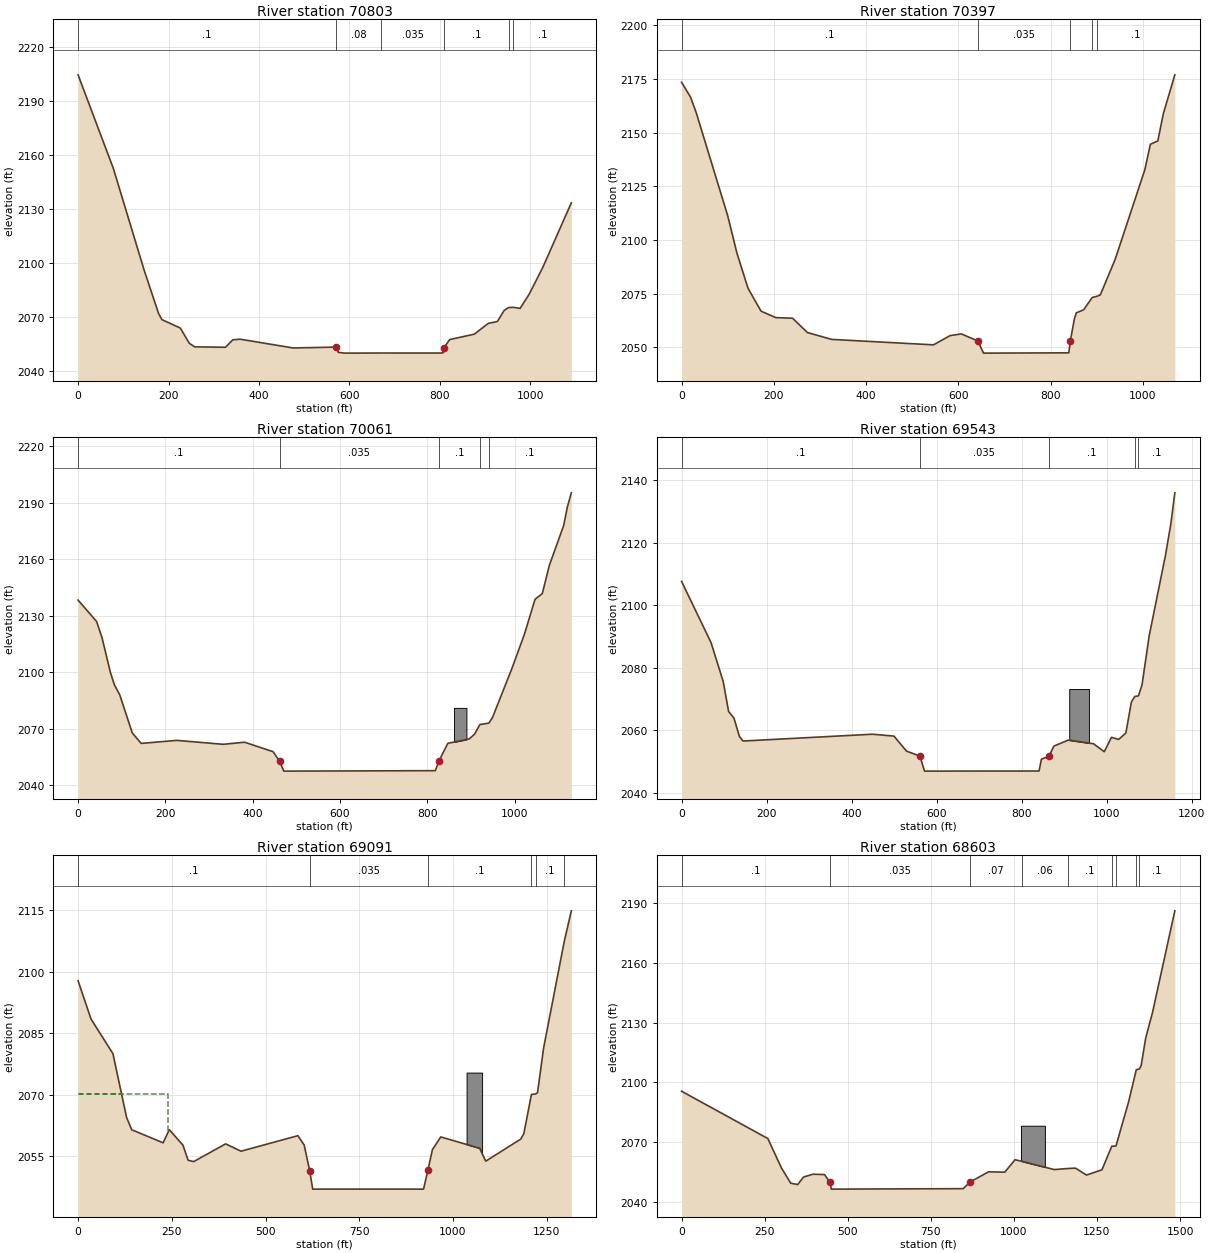
Type RM Length L Ch R = 1 ,70803   ,134.9,405.6,504.2
BEGIN DESCRIPTION:
channel burned 2.32':
lidar invert = 2052.22
effective invert = 2049.90
END DESCRIPTION:
XS GIS Cut Line= 3
2211177.03666339 415811.112172712211182.63709484416201.275563736
2211606.40307456416759.451898266
#Sta/Elev= 30
       0 2204.51    78.1 2152.45   146.1 2096.02   178.1 2071.89   185.6 2068.48
   226.1 2063.84   246.1 2055.34   258.1 2053.39   326.1 2053.15   342.1 2057.26
   358.1 2057.66   475.5 2052.77   570.9 2053.25   575.9 2050.28     591  2049.9
   670.6 2049.96   805.2 2049.95  807.98 2050.28   809.5 2053.02     822 2057.43
   876.5 2060.44   907.4 2066.44   927.5 2067.47   942.5 2073.65   952.6 2075.24
   962.6 2075.35   977.7 2074.75   997.8 2082.64  1027.9 2097.53    1091 2133.42
#Mann= 6 ,-1,0
       0      .1       0   570.9     .08       0   670.6    .035       0
   809.5      .1       0   952.6    .016       0   962.6      .1       0
Bank Sta=570.9,809.5
XS Rating Curve= 0 ,0
Exp/Cntr(USF)=0,0
Exp/Cntr=0.3,0.1

Type RM Length L Ch R = 1 ,70397   ,287.7,335.9,354.7
BEGIN DESCRIPTION:
channel burned 4.31':
lidar invert = 2051.54
interpolated invert = 2047.23
END DESCRIPTION:
XS GIS Cut Line= 2
2211068.76165535415829.7802775432210960.48664731 416893.86225307
#Sta/Elev= 30
       0 2173.48    19.5 2166.57    31.6 2159.43    99.9 2111.37     120 2093.87
   144.1 2077.45   172.3 2066.79   204.4 2063.78   240.6 2063.51   272.8 2056.84
   325.4 2053.63   546.2 2051.09   582.4  2055.4   606.5 2056.21   642.3  2052.9
   654.8 2047.23   839.7 2047.37     843 2052.92   851.8 2063.21   855.8 2065.98
   871.9 2067.45   890.4 2073.16   901.4 2073.77   908.1 2074.42   940.2 2090.94
  1004.6 2132.76  1016.6 2144.63  1032.7 2146.15  1044.8 2158.98  1069.6 2176.98
#Mann= 5 ,-1,0
       0      .1       0   642.3    .035       0     843      .1       0
   890.4    .016       0   901.4      .1       0
Bank Sta=642.3,843
XS Rating Curve= 0 ,0
Exp/Cntr(USF)=0,0
Exp/Cntr=0.3,0.1

Type RM Length L Ch R = 1 ,70061   ,461.9,518.5,557.6
BEGIN DESCRIPTION:
channel burned 3.58':
lidar invert = 2050.99
interpolated invert = 2047.41
END DESCRIPTION:
Node Name=C
XS GIS Cut Line= 2
2210797.99367338415843.614173445 2210571.2694113416950.306379033
#Sta/Elev= 30
       0 2138.28    42.4 2126.91    54.7 2118.46      74 2099.88    83.3 2093.18
    95.5 2087.93   124.1 2067.74   144.5 2062.14   226.2 2063.74   332.3 2061.66
   381.3 2062.77   446.7 2057.74   461.8 2052.56   471.2 2047.41   818.2 2047.65
   826.2 2052.63   846.8 2062.16   895.8 2064.53     908 2067.02   920.3 2072.15
   940.7 2072.91   948.9 2075.74   993.8 2102.04  1022.4 2120.22  1046.6  2138.7
  1063.2 2141.73  1079.5 2156.83  1112.2 2177.91  1120.4 2187.54  1129.7 2195.27
#Mann= 5 ,-1,0
       0      .1       0   461.8    .035       0   826.2      .1       0
   920.3    .016       0   940.7      .1       0
#Block Obstruct= 1 ,-1
  860.84  889.44 2081.02
Bank Sta=461.8,826.2
XS Rating Curve= 0 ,0
Exp/Cntr=0.3,0.1

Type RM Length L Ch R = 1 ,69543   ,386,451.7,486.5
BEGIN DESCRIPTION:
channel burned 3.58':
lidar invert = 2050.52
interpolated invert = 2046.94
END DESCRIPTION:
XS GIS Cut Line= 2
2210375.69153628415748.592415378 2209999.4088226416846.225725801
#Sta/Elev= 30
       0 2107.61    69.4    2088    97.9  2075.6   110.6    2066   123.2  2063.9
   135.9 2058.07   144.4 2056.56   448.8 2058.74   499.6 2058.14   529.2 2053.33
   560.6 2051.76   571.5 2046.94   840.9 2046.98  846.51 2050.78   863.9 2051.64
   875.9 2054.95   909.8 2056.87   968.9  2055.7   994.3 2053.15  1011.2 2057.75
  1028.1 2057.08  1045.1 2059.12  1058.1 2069.05  1066.2 2070.81  1074.7 2071.01
  1083.1 2074.51    1100 2090.23  1138.1 2115.83  1150.8  2125.9  1160.3 2135.93
#Mann= 5 ,-1,0
       0      .1       0   560.6    .035       0   863.9      .1       0
  1066.2    .016       0  1074.7      .1       0
#Block Obstruct= 1 ,-1
  911.85  958.14 2073.21
Bank Sta=560.6,863.9
XS Rating Curve= 0 ,0
Exp/Cntr=0.3,0.1

Type RM Length L Ch R = 1 ,69091   ,544.9,488,451.9
BEGIN DESCRIPTION:
channel burned 2.74'
lidar invert = 2049.66
interpolated invert = 2046.92
END DESCRIPTION:
XS GIS Cut Line= 3
  2210084.694629415575.5176048952209612.64947831416442.094116092
2209554.59710483416765.885806404
#Sta/Elev= 30
       0 2097.81    34.5 2088.46      93    2080   129.4 2064.43   143.1 2061.42
   226.9 2058.23   243.3 2061.44   279.7 2057.67   293.5 2053.97   308.3 2053.64
   393.6 2057.97   434.6 2056.18   586.4 2059.97   603.1 2057.69   617.9  2051.4
   625.9 2046.92   921.6 2046.92   933.3 2051.59   945.2 2056.56   967.5 2059.66
  1071.2 2056.91  1087.5 2053.75  1180.9 2059.14  1189.1 2060.46  1209.4 2070.05
  1220.7 2070.16  1225.6 2070.47  1241.9  2081.4    1297 2107.43  1315.8 2114.88
#Mann= 6 ,-1,0
       0      .1       0   617.9    .035       0   933.3      .1       0
  1209.4    .016       0  1220.7      .1       0    1297     .06       0
#XS Ineff= 2 , 0
             240 2070.23
Permanent Ineff=
       F       F
#Block Obstruct= 1 ,-1
 1036.38 1077.74 2075.38
Bank Sta=617.9,933.3
XS Rating Curve= 0 ,0
Exp/Cntr=0.3,0.1

Type RM Length L Ch R = 1 ,68603   ,349,332.5,284.9
BEGIN DESCRIPTION:
channel burned 2.21':
lidar invert = 2048.58
interpolated effective invert = 2046.37
END DESCRIPTION:
XS GIS Cut Line= 3
2209359.49598359415355.7134059752209445.23928549415593.527546993
2209053.30500144416761.134325226
#Sta/Elev= 30
       0 2095.58   259.7 2071.79   300.7 2056.94   328.4 2049.37   349.5 2048.66
   367.1 2052.47   395.5 2053.87   430.3 2053.68   446.5 2049.81   450.7 2046.37
   847.4  2046.6   868.5 2049.98   923.8 2055.07   972.6  2054.9  1003.5 2061.14
  1025.4 2060.29  1121.6  2056.2  1163.1 2056.74  1185.3 2056.93  1218.7 2053.45
  1265.1 2056.09  1294.6 2067.94  1307.3 2068.05  1345.2 2090.22  1368.4 2106.38
    1378  2106.8  1383.2 2108.62  1396.9 2122.47    1417 2135.03  1484.4 2186.28
#Mann= 9 ,-1,0
       0      .1       0   446.5    .035       0   868.5     .07       0
  1025.4     .06       0  1163.1      .1       0  1294.6    .016       0
  1307.3      .1       0  1368.4    .016       0    1378      .1       0
#Block Obstruct= 1 ,-1
 1021.58 1093.32 2078.25
Bank Sta=446.5,868.5
XS Rating Curve= 0 ,0
Exp/Cntr=0.3,0.1

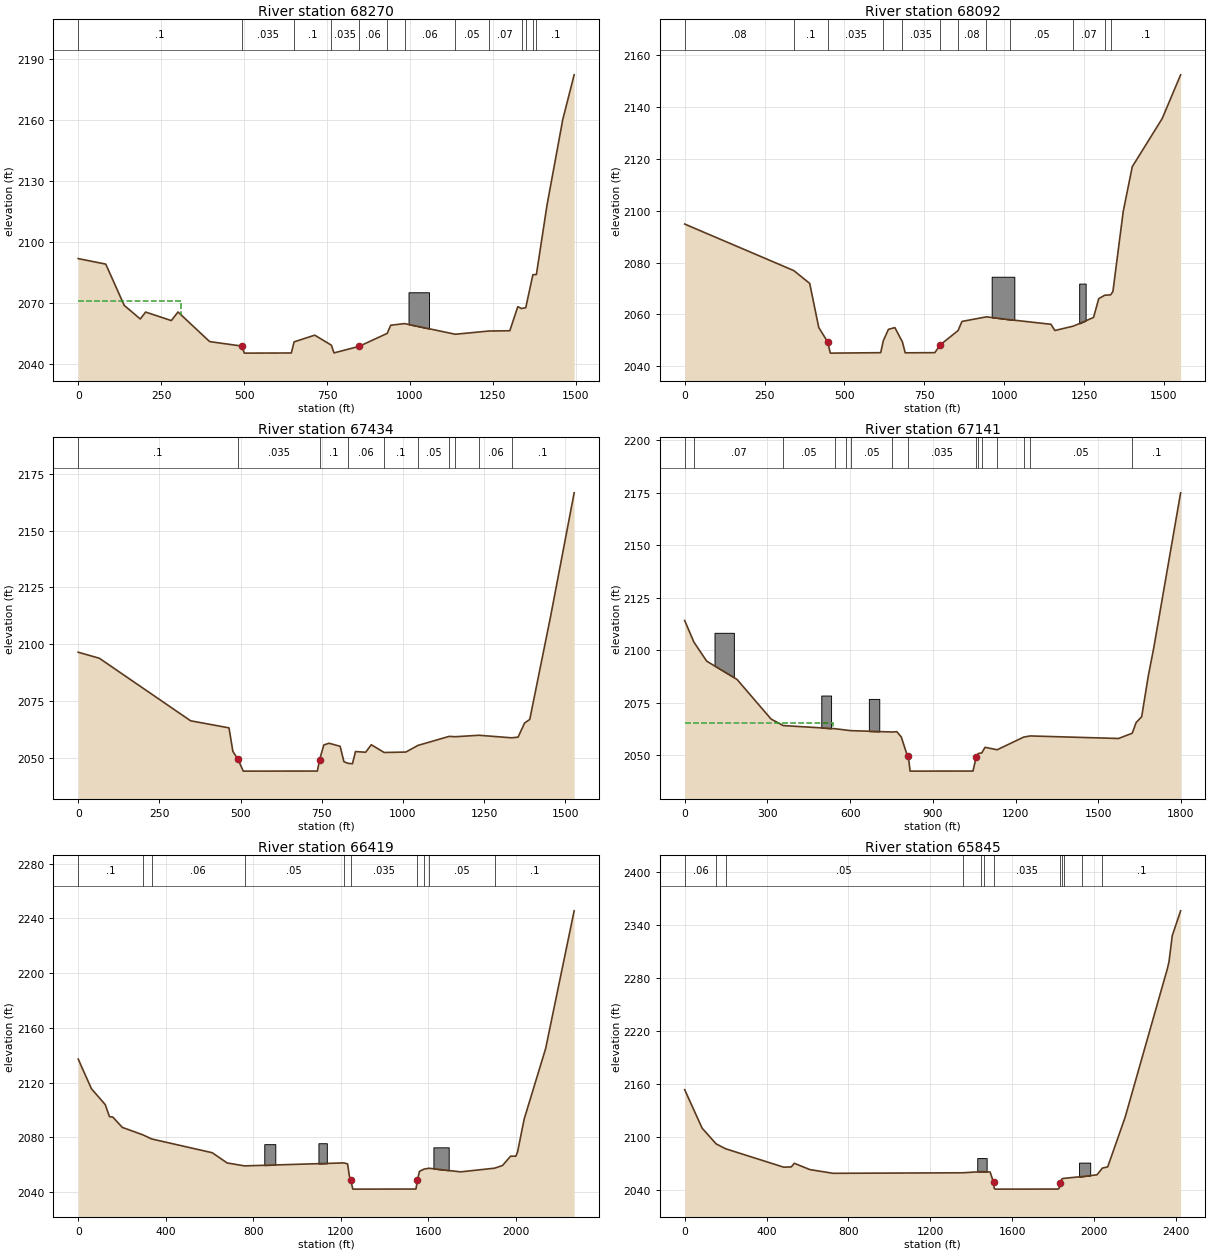
Type RM Length L Ch R = 1 ,68270   ,208.5,178.6,110.8
BEGIN DESCRIPTION:
channel burned 2.33':
lidar invert = 2047.81
interpolated effective invert = 2045.48
END DESCRIPTION:
XS GIS Cut Line= 3
 2209179.3951161415268.4199613012208872.96152506416319.801985021
2208846.51628224416718.651489928
#Sta/Elev= 30
       0  2091.9      83  2089.2   138.7 2068.93   187.1 2062.26   203.2 2065.65
   280.7 2061.46   300.8 2065.68   396.2 2051.14   492.4 2048.96   500.8 2045.48
   642.4 2045.55   650.8 2051.01     713  2054.3   763.2 2049.37     771 2045.59
   846.6  2048.8   931.3 2055.17     942 2059.17   983.6 2059.99  1136.6 2054.75
  1236.8 2056.32    1301 2056.48    1325  2068.3  1336.2 2067.39    1349 2067.78
  1370.5 2083.98  1381.1 2084.09    1413 2118.05  1460.7 2160.29  1494.9 2182.15
#Mann= 13 ,-1,0
       0      .1       0   492.4    .035       0   650.8      .1       0
   763.2    .035       0   846.6     .06       0   931.3     .05       0
   983.6     .06       0  1136.6     .05       0  1236.8     .07       0
  1336.2    .016       0    1349      .1       0  1370.5    .016       0
  1381.1      .1       0
#XS Ineff= 2 , 0
          310.04 2070.84
Permanent Ineff=
       F       F
#Block Obstruct= 1 ,-1
  995.64 1057.19 2075.36
Bank Sta=492.4,846.6
XS Rating Curve= 0 ,0
Exp/Cntr=0.3,0.1

Type RM Length L Ch R = 1 ,68092   ,679.4,658.3,647.9
BEGIN DESCRIPTION:
channel burned 2.30':
lidar invert = 2047.41
interpolated effective invert = 2045.11
END DESCRIPTION:
XS GIS Cut Line= 3
2208751.76849297415263.5488799212208865.19865978415621.885088695
2208705.36524291416787.122256794
#Sta/Elev= 30
       0 2094.84   341.6  2076.9   391.3 2071.96   419.6 2054.98   447.2 2049.49
   455.9 2045.11   613.4 2045.28   621.8 2049.96   637.6 2054.26   657.8 2054.94
   681.5 2049.39   690.1 2045.23   782.9 2045.29  799.49 2048.27   855.5 2053.79
   867.7 2057.32   944.4 2059.09  1017.1    2058  1146.3 2056.22  1158.4 2053.82
  1216.1 2055.51  1279.5 2058.85  1295.7 2066.07  1314.4 2067.41  1333.1 2067.56
  1340.1 2068.84  1372.4 2099.69  1400.7 2116.93  1494.5 2135.52    1552 2152.33
#Mann= 12 ,-1,0
       0     .08       0   341.6      .1       0   447.2    .035       0
   621.8      .1       0   681.5    .035       0  799.49     .06       0
   855.5     .08       0   944.4     .06       0  1017.1     .05       0
  1216.1     .07       0  1314.4    .016       0  1333.1      .1       0
#Block Obstruct= 2 ,-1
  960.72 1031.62 2074.54 1234.55 1254.75  2071.9
Bank Sta=447.2,799.49
XS Rating Curve= 0 ,0
Exp/Cntr(USF)=0,0
Exp/Cntr=0.3,0.1

Type RM Length L Ch R = 1 ,67434   ,304.6,292.3,224.2
BEGIN DESCRIPTION:
channel burned 2.67':
lidar invert = 2046.97
interpolated effective invert = 2044.30
END DESCRIPTION:
XS GIS Cut Line= 5
 2208432.8014794415225.2693369032208181.67852327415556.491856627
2208192.50278862415931.0114377532208129.72204959416032.759532047
2208103.74381275416649.742657023
#Sta/Elev= 30
       0 2096.55    65.1  2093.9   346.2 2066.42   464.4 2063.31   476.4 2052.94
   492.1 2049.48   508.4  2044.3   736.5 2044.33   743.5 2049.39   756.5 2055.81
   772.5 2056.55   806.7 2055.22   818.3 2048.45   830.5 2047.76   844.6 2047.54
     854 2052.91   885.2 2052.59   902.6 2055.91   942.3 2052.49    1009 2052.68
  1046.2 2055.59  1142.3 2059.57  1161.5 2059.42  1234.5 2060.06  1334.7 2058.94
  1354.7 2059.23  1374.7 2065.44  1390.7 2067.01  1454.8 2112.24  1527.4 2166.59
#Mann= 10 ,-1,0
       0      .1       0   492.1    .035       0   743.5      .1       0
   830.5     .06       0   942.3      .1       0  1046.2     .05       0
  1142.3     .06       0  1161.5     .05       0  1234.5     .06       0
  1334.7      .1       0
Bank Sta=492.1,743.5
XS Rating Curve= 0 ,0
Exp/Cntr(USF)=0,0
Exp/Cntr=0.3,0.1

Type RM Length L Ch R = 1 ,67141   ,628.7,722.3,756.6
BEGIN DESCRIPTION:
channel burned 4.39':
lidar invert = 2046.84
interpolated effective invert = 2042.45
END DESCRIPTION:
XS GIS Cut Line= 4
2208019.86215373414855.2369687682207903.62020026415088.247713038
2207893.55476783415310.5441101612207899.23186176416626.463599761
#Sta/Elev= 30
       0  2114.1    33.5 2103.82    79.9 2094.77   189.9 2086.08   313.4 2067.22
   357.4 2064.13   545.6 2062.62   585.6 2061.97   601.6 2061.72   753.6 2061.06
   769.6 2061.21   785.6 2058.72  808.56 2049.44   813.6 2047.13   817.6 2042.45
  1045.8 2042.49  1057.6 2049.19  1065.5 2050.86  1077.5 2051.09  1089.6 2053.78
  1133.4 2052.61  1229.6 2058.64  1253.6 2059.19  1573.6 2057.98  1623.3 2060.47
  1637.6 2065.57  1657.6 2068.31  1681.6 2087.71  1701.6 2101.18  1798.9 2174.85
#Mann= 15 ,-1,0
       0     .06       0    33.5     .07       0   357.4     .05       0
   545.6     .06       0   585.6    .016       0   601.6     .05       0
   753.6      .1       0  808.56    .035       0  1057.6     .06       0
  1065.5    .016       0  1077.5     .08       0  1133.4     .05       0
  1229.6    .016       0  1253.6     .05       0  1623.3      .1       0
#XS Ineff= 2 , 0
          539.19 2065.18
Permanent Ineff=
       F       F
#Block Obstruct= 3 ,-1
  108.21  178.39 2108.26  495.47  531.04 2078.41  668.06  705.82 2076.81
Bank Sta=808.56,1057.6
XS Rating Curve= 0 ,0
Exp/Cntr(USF)=0,0
Exp/Cntr=0.3,0.1

Type RM Length L Ch R = 1 ,66419   ,440.8,574.2,614.5
BEGIN DESCRIPTION:
channel burned 4.48':
lidar invert = 2046.53
interpolated effective invert = 2042.05
END DESCRIPTION:
XS GIS Cut Line= 3
2207810.86545032414547.5057629792207189.80606962415446.971072959
2207130.91250766 416619.48835204
#Sta/Elev= 30
       0 2137.14    60.4 2115.49   123.6 2103.84     143 2095.06   158.4 2094.71
   201.3 2087.22   296.4  2081.7   335.6 2078.74   612.7 2068.67   680.6  2061.2
   760.3 2059.05  1214.9 2061.22  1231.4 2060.47  1239.4 2051.74  1245.4 2048.64
  1255.5 2042.05  1543.8 2042.11  1550.5 2048.48  1559.8 2055.04    1581 2056.72
    1604 2057.31  1748.1 2054.68  1903.3 2057.36  1939.5 2059.33  1976.4 2066.14
  2000.4 2066.12  2008.4 2069.26  2038.6 2093.31  2136.6 2144.81    2267 2245.54
#Mann= 10 ,-1,0
       0      .1       0   296.4     .08       0   335.6     .06       0
   760.3     .05       0  1214.9      .1       0  1245.4    .035       0
  1550.5     .06       0    1581    .016       0    1604     .05       0
  1903.3      .1       0
#Block Obstruct= 3 ,-1
  850.52  900.88 2074.93 1098.11 1136.43 2075.61 1623.67 1693.49 2072.61
Bank Sta=1245.4,1550.5
XS Rating Curve= 0 ,0
Exp/Cntr(USF)=0,0
Exp/Cntr=0.3,0.1

Type RM Length L Ch R = 1 ,65845   ,322.5,500.6,600.5
BEGIN DESCRIPTION:
channel burned 4.98':
lidar invert = 2046.28
interpolated effective invert = 2041.30
END DESCRIPTION:
XS GIS Cut Line= 3
2207521.75160068414344.0552761982206654.41005178415366.661670282
2206493.79124642416437.453705972
#Sta/Elev= 30
       0 2153.78    85.4 2110.22   153.6 2092.49   200.3 2086.93   484.4 2066.11
   521.3 2066.45   535.5 2070.54   612.1 2063.38   725.3 2059.19  1359.6 2059.78
  1448.6 2061.07  1463.8 2061.02  1492.8 2060.67  1509.3 2049.02  1513.3 2041.95
  1517.4  2041.3  1824.8 2041.36  1830.4 2042.39  1832.9  2048.4  1844.5 2053.05
  1855.1 2053.53  1942.1 2055.52  2014.9 2057.46  2041.5  2065.1  2067.5 2066.51
  2152.4 2122.47  2358.7 2290.42  2366.8 2298.33  2382.9 2328.03  2423.7 2356.07
#Mann= 12 ,-1,0
       0     .06       0   153.6      .1       0   200.3     .05       0
  1359.6     .06       0  1448.6     .05       0  1463.8     .06       0
  1509.3    .035       0  1832.9     .06       0  1844.5    .016       0
  1855.1     .06       0  1942.1     .05       0  2041.5      .1       0
#Block Obstruct= 2 ,-1
 1429.84 1475.68 2076.41 1927.46 1981.82 2071.28
Bank Sta=1509.3,1832.9
XS Rating Curve= 0 ,0
Exp/Cntr(USF)=0,0
Exp/Cntr=0.3,0.1

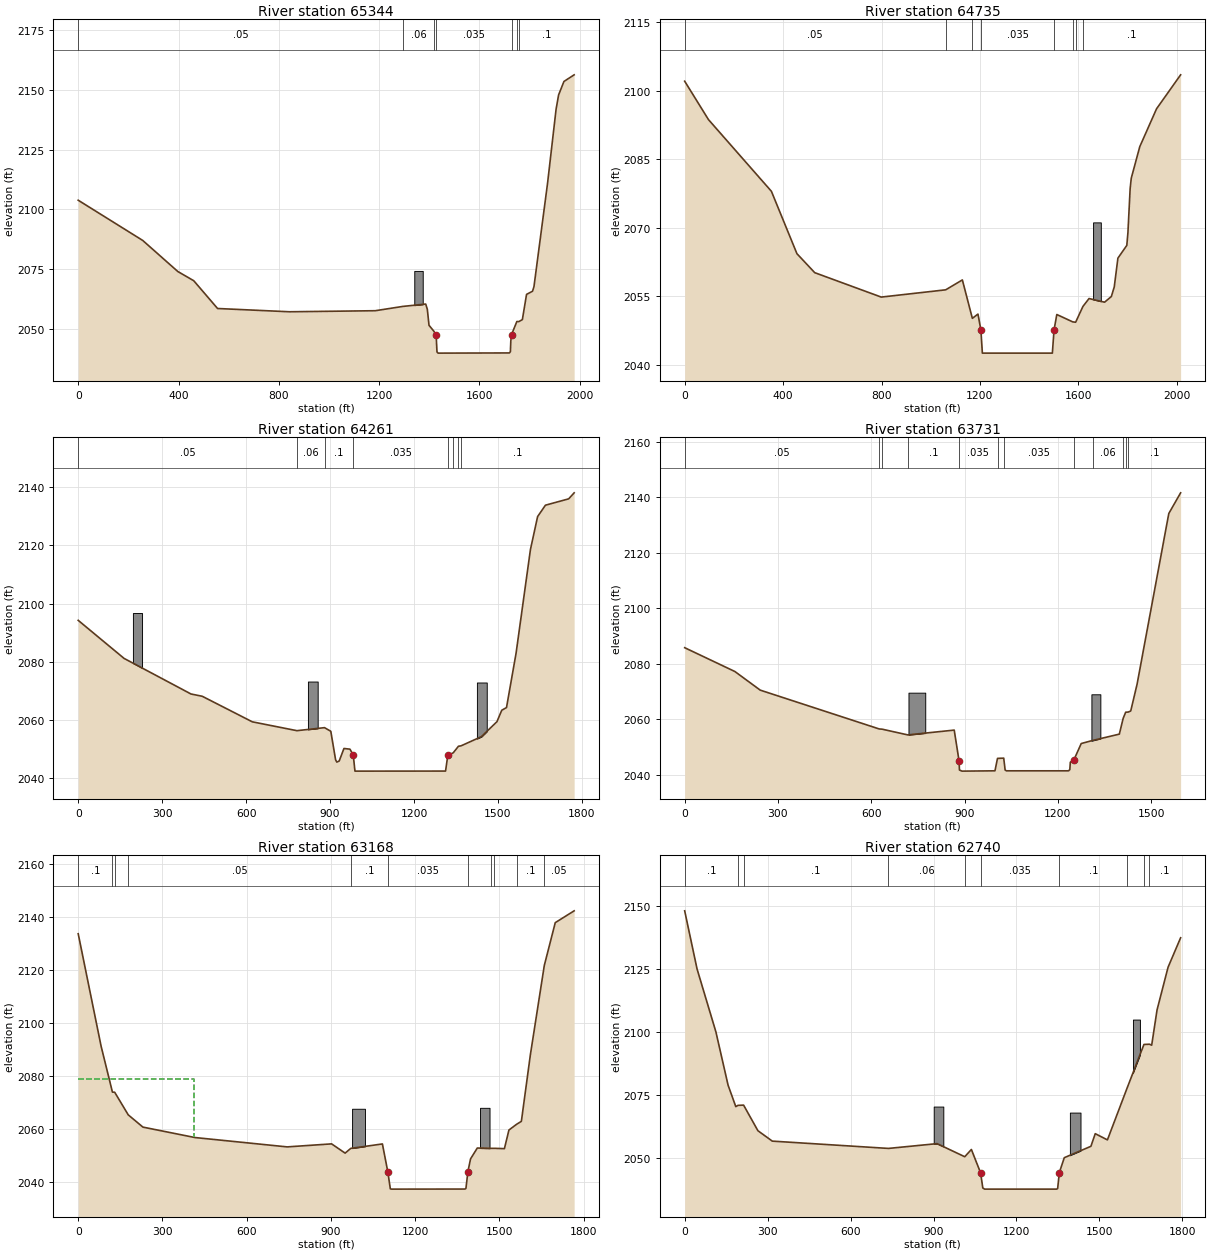
Type RM Length L Ch R = 1 ,65344   ,324.6,608.9,691.6
BEGIN DESCRIPTION:
channel burned 6.29':
lidar invert = 2046.09
interpolated effective invert = 2039.80
END DESCRIPTION:
XS GIS Cut Line= 2
2207146.97438819414258.3919133432205915.56354715415805.686404915
#Sta/Elev= 30
       0 2103.84   257.3 2086.99   397.2 2073.98   460.6 2070.13   555.7 2058.49
     842 2057.12  1184.5 2057.56  1295.6 2059.38  1385.6 2060.35    1392 2058.21
  1398.8 2051.45  1417.7 2049.04  1427.3 2047.34  1430.5 2040.32    1435  2039.8
  1719.6 2039.88  1723.3 2040.41 1724.91 2044.83  1727.7  2047.5    1749 2053.03
    1757 2053.01    1771 2053.83  1787.7 2064.41  1811.6 2065.72  1817.3 2067.67
  1871.4 2110.89  1905.5 2141.98  1915.5 2147.94  1936.8 2153.58  1977.5 2156.36
#Mann= 7 ,-1,0
       0     .05       0  1295.6     .06       0  1417.7      .1       0
  1427.3    .035       0  1727.7      .1       0    1749    .016       0
    1757      .1       0
#Block Obstruct= 1 ,-1
 1340.01 1373.75 2074.23
Bank Sta=1427.3,1727.7
XS Rating Curve= 0 ,0
Exp/Cntr(USF)=0,0
Exp/Cntr=0.3,0.1

Type RM Length L Ch R = 1 ,64735   ,443.3,474.2,505
BEGIN DESCRIPTION:
channel burned 3.34':
lidar invert = 2045.84
interpolated effective invert = 2042.50
END DESCRIPTION:
Node Name=B
XS GIS Cut Line= 3
2206906.04618016 414129.896869062206611.57837035414568.921603693
2205294.50416645415259.582466713
#Sta/Elev= 30
       0 2102.08    96.7 2093.67   352.5 2077.96   456.3 2064.29   528.6 2060.13
     799 2054.78  1060.9 2056.37  1128.7 2058.54  1169.3 2050.12  1192.1 2051.06
  1203.9 2047.62    1210  2042.5  1494.5  2042.5 1501.36 2047.59  1512.6 2050.96
  1577.2 2049.35  1589.1 2049.27  1618.7 2052.73  1643.6 2054.46  1706.8 2053.66
  1734.3 2054.91  1746.1 2057.01  1760.9 2063.31  1797.1 2066.11  1801.6 2068.89
  1810.7 2078.58  1815.2 2080.83  1849.8 2087.74    1918 2096.04  2015.8 2103.48
#Mann= 8 ,-1,0
       0     .05       0  1060.9     .06       0  1169.3      .1       0
  1203.9    .035       0 1501.36      .1       0  1577.2    .016       0
  1589.1     .08       0  1618.7      .1       0
#Block Obstruct= 1 ,-1
 1659.97 1691.45 2071.15
Bank Sta=1203.9,1501.36
XS Rating Curve= 0 ,0
Exp/Cntr(USF)=0,0
Exp/Cntr=0.3,0.1

Type RM Length L Ch R = 1 ,64261   ,447.5,529.7,560
BEGIN DESCRIPTION:
channel burned 3.24':
lidar invert = 2045.64
interpolated effective invert = 2042.40
END DESCRIPTION:
XS GIS Cut Line= 2
2206777.55113588414113.8349885252205117.82348056414734.894369225
#Sta/Elev= 30
       0 2094.21   163.8 2081.14   402.9 2068.91   443.3 2068.12   622.1 2059.34
   781.5  2056.3   880.1 2057.34   902.6 2056.09   919.7 2046.28     924  2045.5
   932.5 2045.87   949.6 2050.18     971 2049.95   982.7 2047.98   988.9  2042.4
  1312.6 2042.42  1320.6 2047.79  1340.1  2048.7  1358.7 2050.95    1368 2051.09
  1440.8 2054.25  1496.3  2059.4  1513.4 2063.32  1530.4 2064.24  1564.6 2082.93
  1615.9 2118.54  1641.5 2129.86  1669.5 2133.78  1752.5 2135.96  1772.1 2138.03
#Mann= 8 ,-1,0
       0     .05       0   781.5     .06       0   880.1      .1       0
   982.7    .035       0  1320.6     .06       0  1340.1      .1       0
  1358.7    .016       0    1368      .1       0
#Block Obstruct= 3 ,-1
  195.47  228.12 2096.72  820.81  855.67 2073.19 1424.62  1459.8 2072.86
Bank Sta=982.7,1320.6
XS Rating Curve= 0 ,0
Exp/Cntr(USF)=0,0
Exp/Cntr=0.3,0.1

Type RM Length L Ch R = 1 ,63731   ,516.9,563,580
BEGIN DESCRIPTION:
channel burned 2.42':
lidar invert = 2043.64
interpolated effective invert = 2041.22
END DESCRIPTION:
XS GIS Cut Line= 2
2206638.34817124413797.9513379962205074.99179913414113.834988525
#Sta/Elev= 30
       0 2085.75   161.4 2077.16     243 2070.44   625.8 2056.43   634.7 2056.36
   717.5 2054.29   866.9 2056.02   882.42044.935   883.7 2041.63   891.8 2041.22
   997.9 2041.33  1006.1 2045.82  1026.1  2045.9  1030.6 2041.61  1034.7 2041.33
  1234.6 2041.33  1238.7 2041.78  1240.3 2044.46    1251 2045.08  1275.4 2051.18
  1311.6 2052.27  1397.9 2054.57  1410.1  2060.2  1410.1 2060.22  1418.3 2062.47
  1426.4 2062.53  1434.6 2062.93    1455 2072.59    1557 2134.16    1595 2141.62
#Mann= 12 ,-1,0
       0     .05       0   625.8    .016       0   634.7     .05       0
   717.5      .1       0   882.4    .035       0  1006.1      .1       0
  1026.1    .035       0    1251     .08       0  1311.6     .06       0
  1410.1      .1       0  1418.3    .016       0  1426.4      .1       0
#Block Obstruct= 2 ,-1
  719.75   773.7 2069.53 1308.07 1336.87 2068.94
Bank Sta=882.4,1251
XS Rating Curve= 0 ,0
Exp/Cntr(USF)=0,0
Exp/Cntr=0.3,0.1

Type RM Length L Ch R = 1 ,63168   ,372.9,428.9,453.3
BEGIN DESCRIPTION:
channel burned 5.47':
lidar invert = 2042.97
interpolated effective invert = 2037.50
END DESCRIPTION:
XS GIS Cut Line= 2
2206713.30361374413326.8028422932204957.20467521413519.545408717
#Sta/Elev= 30
       0 2133.77    81.6 2091.36   121.9 2074.07   129.9 2074.03   178.2  2065.5
   230.5 2060.88   415.6 2056.95   744.4 2053.42   902.6 2054.56   950.8 2051.07
   970.9 2052.86  1083.6 2054.53 1102.96 2043.96  1111.8 2037.62  1115.8  2037.5
  1377.4 2037.53  1381.1 2037.74  1388.2 2044.11  1397.5 2048.89  1421.6 2052.99
  1471.7 2052.87    1482 2052.88  1518.2 2052.76  1534.3 2059.78  1561.6 2061.94
  1578.6 2063.06  1610.7 2088.17  1660.3 2121.83  1699.3 2137.95  1766.6 2142.41
#Mann= 11 ,-1,0
       0      .1       0   121.9    .016       0   129.9     .06       0
   178.2     .05       0   970.9      .1       0 1102.96    .035       0
  1388.2     .06       0  1471.7    .016       0    1482     .06       0
  1561.6      .1       0  1660.3     .05       0
#XS Ineff= 2 , 0
          413.08 2079.07
Permanent Ineff=
       F       F
#Block Obstruct= 2 ,-1
  975.56 1021.36  2067.8 1431.39 1465.13 2068.15
Bank Sta=1102.96,1388.2
XS Rating Curve= 0 ,0
Exp/Cntr(USF)=0,0
Exp/Cntr=0.3,0.1

Type RM Length L Ch R = 1 ,62740   ,456.8,557.5,605.5
BEGIN DESCRIPTION:
channel burned 4.88':
lidar invert = 2042.38
interpolated effective invert = 2037.50
END DESCRIPTION:
XS GIS Cut Line= 2
2206665.11797213413037.6889926562204871.54131235413032.335032478
#Sta/Elev= 30
       0 2148.06    44.9 2124.91   112.8 2100.02     157 2078.79   184.9 2070.27
   192.9 2070.78   213.1 2070.87   264.9  2060.7   316.9 2056.57   736.9 2053.67
   912.9 2055.57  1012.9 2050.37  1036.9 2053.26 1070.23 2043.96  1078.2 2037.96
  1084.9  2037.5  1344.9  2037.5  1348.9 2037.71 1354.88 2044.04  1372.9 2049.99
  1469.1 2054.51  1484.9 2059.53  1528.9 2057.06  1600.7 2077.83    1661 2094.97
    1681 2095.06    1689 2094.69  1708.4 2108.72  1748.2 2125.64  1793.6 2137.36
#Mann= 10 ,-1,0
       0      .1       0   192.9    .016       0   213.1      .1       0
   736.9     .06       0  1012.9      .1       0 1070.23    .035       0
 1354.88      .1       0  1600.7     .06       0    1661    .016       0
    1681      .1       0
#Block Obstruct= 3 ,-1
  900.63   935.4  2070.3 1393.13 1431.55 2067.91 1621.19 1646.43 2104.86
Bank Sta=1070.23,1354.88
XS Rating Curve= 0 ,0
Exp/Cntr(USF)=0,0
Exp/Cntr=0.3,0.1

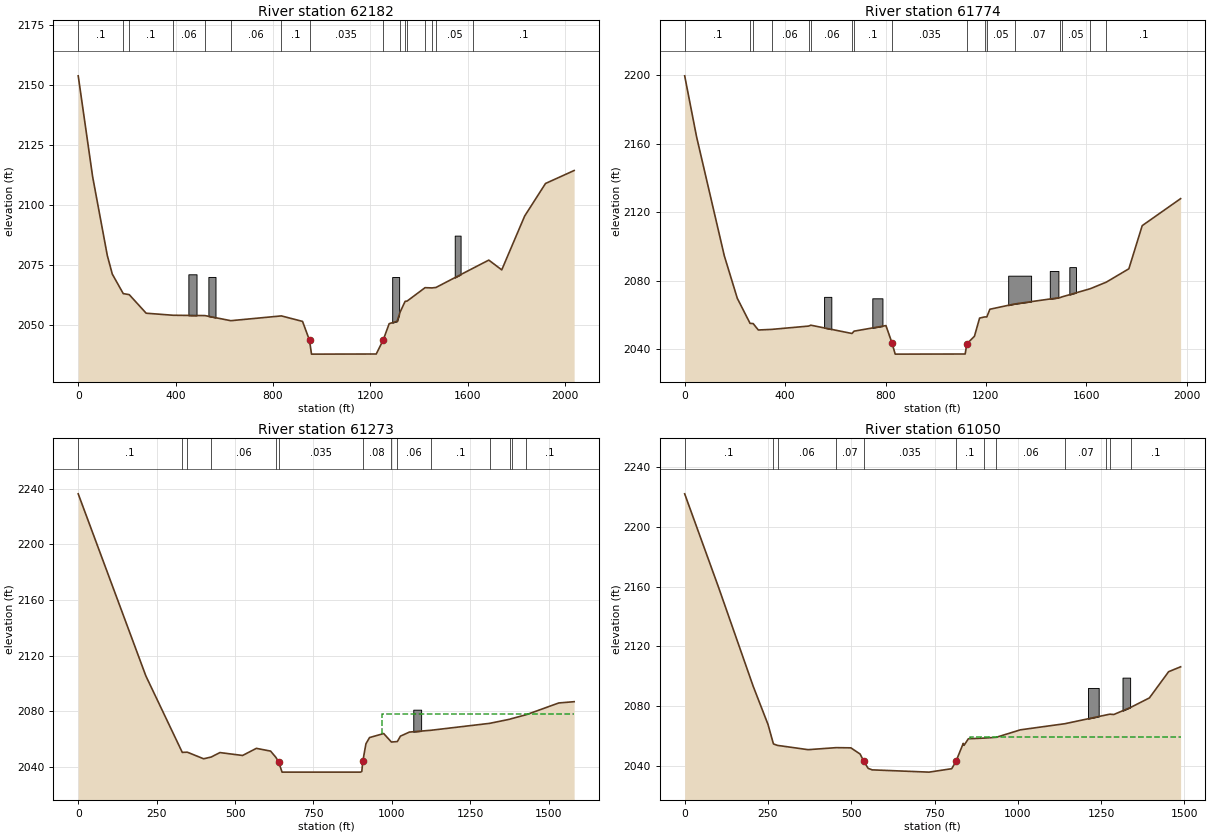
Type RM Length L Ch R = 1 ,62182   ,405,408.3,410.1
BEGIN DESCRIPTION:
channel burned 3.74':
lidar invert = 2041.54
interpolated effective invert = 2037.80
END DESCRIPTION:
XS GIS Cut Line= 2
 2206649.0560916412721.8053421282204657.38290521412288.134567673
#Sta/Elev= 30
       0 2153.64    59.3 2111.63   119.6 2078.86   140.1 2071.11   185.1 2062.99
   209.7 2062.56   279.3 2054.83   389.8 2053.98   520.8 2053.84   627.2 2051.72
     835 2053.71     922 2051.42   950.6 2043.56   958.8  2037.8  1224.9 2037.85
  1253.6 2043.71  1278.1 2050.48  1310.9 2051.47  1322.4 2055.16  1343.6 2059.78
  1351.8 2059.88  1425.5 2065.46  1454.2 2065.36  1470.5 2065.55  1621.6  2073.5
  1687.5 2076.94  1740.7 2072.87  1834.9 2095.28  1920.6 2108.83  2038.3 2114.23
#Mann= 16 ,-1,0
       0      .1       0   185.1    .016       0   209.7      .1       0
   389.8     .06       0   520.8     .07       0   627.2     .06       0
     835      .1       0   950.6    .035       0  1253.6     .07       0
  1322.4     .05       0  1343.6    .016       0  1351.8     .06       0
  1425.5     .07       0  1454.2    .016       0  1470.5     .05       0
  1621.6      .1       0
#Block Obstruct= 4 ,-1
  452.75   486.3 2071.03  535.01  564.23 2069.93 1290.45 1318.99  2069.9
 1547.49 1571.56 2087.13
Bank Sta=950.6,1253.6
XS Rating Curve= 0 ,0
Exp/Cntr(USF)=0,0
Exp/Cntr=0.3,0.1

Type RM Length L Ch R = 1 ,61774   ,515.2,500.5,517.6
BEGIN DESCRIPTION:
channel burned 3.71':
lidar invert = 2040.91
interpolated effective invert = 2037.20
END DESCRIPTION:
XS GIS Cut Line= 2
2206638.34817124412309.550408387  2204710.922507411875.879633932
#Sta/Elev= 30
       0 2199.56    47.3 2164.06     158  2094.5   209.6 2069.78   260.5 2055.14
   272.8 2055.03   293.3 2051.28   346.6 2051.63   493.7 2053.57   502.4 2054.08
   666.4 2049.24   674.6 2050.59   801.7 2053.85   826.3 2043.56   838.6  2037.2
  1117.4 2037.27  1123.9 2043.18  1154.3 2047.63  1174.8 2058.23  1195.3 2058.91
  1203.5 2058.89  1215.8 2063.38  1314.1 2066.46  1495.9 2070.19  1502.8 2070.59
  1615.9 2075.37  1679.1 2079.16  1769.4 2086.98  1822.6 2112.16  1975.6 2127.91
#Mann= 17 ,-1,0
       0      .1       0   260.5    .016       0   272.8      .1       0
   346.6     .06       0   493.7    .016       0   502.4     .06       0
   666.4    .016       0   674.6      .1       0   826.3    .035       0
  1123.9     .08       0  1195.3    .016       0  1203.5     .05       0
  1314.1     .07       0  1495.9    .016       0  1502.8     .05       0
  1615.9     .06       0  1679.1      .1       0
#Block Obstruct= 5 ,-1
   555.3  584.19 2070.61  747.46  787.84 2069.76 1288.67    1380 2082.97
 1454.43 1488.73 2085.71  1532.3 1558.67 2087.96
Bank Sta=826.3,1123.9
XS Rating Curve= 0 ,0
Exp/Cntr(USF)=0,0
Exp/Cntr=0.3,0.1

Type RM Length L Ch R = 1 ,61273   ,250.6,223.4,197.1
BEGIN DESCRIPTION:
structure xs 4 - channel burned 4.12':
lidar invert = 2040.31
interpolated effective invert = 2036.19
END DESCRIPTION:
XS GIS Cut Line= 3
2206635.69616405411693.6484684412206060.34523783411669.845410933
2205080.09358779411446.426173911
#Sta/Elev= 30
       0 2236.26   215.7 2105.35   331.8 2050.38   347.8 2050.53   399.9 2045.78
   423.9 2047.04   451.9 2050.25     524 2048.16     568 2053.28   613.3 2051.31
   629.4 2047.05   638.9 2043.71   649.9 2036.19   900.1 2036.19   904.2 2036.65
   907.3 2043.88   917.3 2056.54   928.8 2061.04     974 2063.92   998.6 2057.82
  1017.6 2058.18  1027.3 2062.05    1056 2064.99  1124.5 2066.28  1311.6 2071.25
  1375.1 2074.18  1382.9 2074.71  1428.5 2077.46  1532.1 2085.91  1581.2 2086.83
#Mann= 14 ,-1,0
       0      .1       0   331.8    .016       0   347.8      .1       0
   423.9     .06       0   629.4      .1       0   638.9    .035       0
   907.3     .08       0   998.6    .016       0  1017.6     .06       0
  1124.5      .1       0  1311.6     .07       0  1375.1    .016       0
  1382.9     .06       0  1428.5      .1       0
#XS Ineff= 2 , 0
                          967.21         2077.85
Permanent Ineff=
       F       F
#Block Obstruct= 1 ,-1
 1068.24 1093.36 2081.08
Bank Sta=638.9,907.3
XS Rating Curve= 0 ,0
Exp/Cntr(USF)=0,0
Exp/Cntr=0.5,0.3

Type RM Length L Ch R = 1 ,61050   ,83.3,86.3,83.4
BEGIN DESCRIPTION:
structure xs 3
END DESCRIPTION:
XS GIS Cut Line= 2
2206594.08162848411449.9389071842205108.19545397411362.120575357
#Sta/Elev= 30
       0 2222.13   102.1  2159.2   205.6 2093.15   250.3 2067.41   266.4 2054.47
   278.7 2053.49   370.6 2050.62   454.7 2051.98   498.8 2051.85  526.54 2047.69
  537.63 2042.84  550.46 2038.15  562.51 2037.09  733.44 2035.57  801.55 2037.86
   814.6 2042.97   836.1 2054.85   838.6 2053.55   851.4 2057.93   899.2 2058.39
   935.5 2058.93  1007.7 2063.93  1141.3 2068.03    1266 2073.95  1276.1 2074.41
  1288.2 2074.21  1340.2 2079.14  1394.8 2085.32  1452.4 2102.87  1488.5 2106.18
#Mann= 12 ,-1,0
       0      .1       0   266.4    .016       0   278.7     .06       0
   454.7     .07       0  537.63    .035       0   814.6      .1       0
   899.2    .016       0   935.5     .06       0  1141.3     .07       0
    1266    .016       0  1276.1      .1       0  1340.2      .1       0
#XS Ineff= 2 , 0
          502.93 2050.69  856.47         2059.06
Permanent Ineff=
       F       F
#Block Obstruct= 2 ,-1
 1210.58 1242.61    2092  1314.1 1336.94 2098.92
Bank Sta=537.63,814.6
XS Rating Curve= 0 ,0
Exp/Cntr(USF)=0,0
Exp/Cntr=0.5,0.3