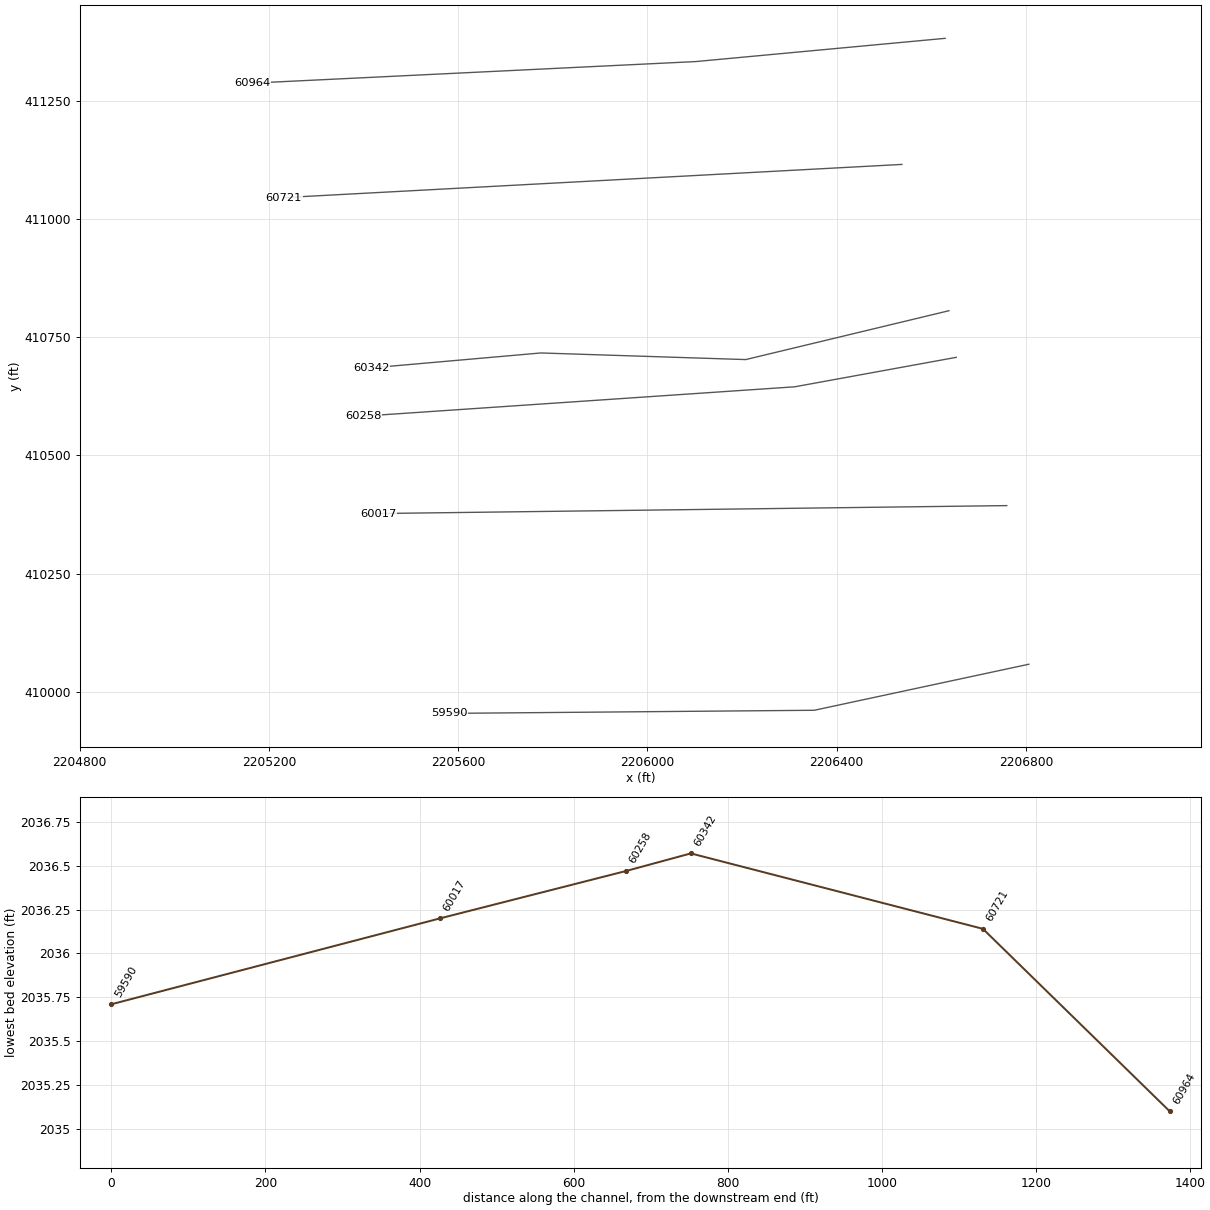
HEC-RAS study GRNBRRRV.prj: GRNBRRRV

--- GRNBRRRV.g01 (geometry) --- (continued)

Type RM Length L Ch R = 3 ,61022   ,,,
BEGIN DESCRIPTION:
Bridge No.: 54075GRL020 Seebert River Rd (Rte 27/3)
JV notes: road deck updated per surveyed XS data points
channel burned per surveyed cross sections
structure opening based on survey data, photos, and aerial imagery
surveyed inverts are 5-6' below inverts from lidar:
 surveyed invert US is 2035.6
 surveyed invert DS is 2035.1
END DESCRIPTION:
Bridge Culvert--1,0,-1,-1, 0
Deck Dist Width WeirC Skew NumUp NumDn MinLoCord MaxHiCord MaxSubmerge Is_Ogee
20,16,2.6,0, 430, 430, , , 0.98, 0, 0,0,,
      -7  -5.263  -4.801  -4.379  -1.066   -.551   3.131   7.106   7.328  10.934
  11.525  14.762  15.723   18.59   19.92  22.419  23.229  24.117  26.247  27.233
  28.314  30.075  31.237  32.511  33.903  35.241  36.709  37.731  39.246   43.25
  45.103  45.388  47.254  51.258  53.044  53.497  55.263  59.267  63.271  64.529
  66.089  67.275  68.357  70.286  71.279  75.284  78.681  79.842  83.292  87.075
  87.498  91.326  95.305  98.983  99.667 102.811 107.317 111.322 115.326  119.33
 121.952 123.334  125.78 129.047 129.609 131.343 135.347 139.351 141.093 141.639
 143.355 144.922 145.836  147.36  148.75 150.033 151.364 155.368 158.427 159.372
 160.234 162.625 163.377 164.063 166.822 167.381 167.891 171.385 175.216 179.413
 183.204 183.611 187.032 187.808  190.86 192.005 194.688  195.41 199.415 200.399
 202.345 203.419 204.597 206.173 207.423 208.794 210.001 211.427 215.432 217.188
 217.658 219.436  223.44 225.314 225.583 227.444 231.448  232.97 233.977 235.453
 236.799 238.174 239.457 240.627 242.371 243.461 244.455 246.569 247.465 248.283
 250.766  251.47 255.474  255.94  259.16 259.768 263.482 263.596 267.486 271.253
 271.491 271.752 275.081 275.949 279.499 283.503 284.343 286.565 291.512 295.516
  299.52 301.878 303.524 307.529 311.533 315.537 319.541 321.019 322.118 323.546
  327.55 331.554 332.504  334.71 338.907 340.161 343.567 347.571 355.579 359.302
  363.13  364.09 366.958 367.592 371.596 375.601 378.443 382.271 385.076 386.099
 387.613 389.273 389.927 391.617 395.622 399.626  403.63  405.24 406.062 407.634
 411.639 414.457 415.643 416.725 420.553 422.851 423.651 427.656 431.245 435.443
  439.64 443.837 447.351 451.681 452.231 455.007 456.444     459  488.54  520.63
  522.93  523.83  582.37  614.91  646.28  675.65  710.13  761.94  774.08  836.47
  836.47   839.6  870.31  915.75 917.411 924.084 928.515 932.523 935.393 936.531
 940.539 942.931 948.555  950.47  954.24 958.009 960.579 964.587 968.595 980.611
 984.395 991.934 993.447 995.703 996.6511000.6591006.2831007.0121008.6751010.562
1014.5511016.6911020.6991024.7071028.7151031.9561033.3981036.7311040.5141044.064
1052.7631056.7711057.6291059.7841063.2761064.8611073.0271076.831 1080.221081.193
1085.2761089.3591090.3871093.4431095.4031097.1651101.6091105.6921107.3311108.342
 1110.721113.858 1119.281120.5571122.1861123.7851126.3511129.2961131.015 1133.47
1134.681 1143.651147.1761149.6121156.0681158.0041159.6711163.8361165.7531168.001
1168.9811172.3591180.4961184.6611186.7131188.3511191.5791192.9911194.8071197.156
1198.0361201.2641204.4921205.4861207.7211209.6511215.4211217.9811220.6341222.146
1224.8951229.7761234.6411236.7751239.9161242.8831251.5371255.0181257.5881259.064
1261.0621264.6191275.2441279.2891282.1961283.3341285.7121287.3671291.3711295.374
1299.3781301.7421303.3811304.8911305.9171307.3841308.7361310.0931311.3881315.391
1318.444 1320.271322.6191324.115 1327.961331.805 1335.651341.523 1343.341343.496
1347.1851347.6721351.4221354.8751356.023 1358.721360.1981364.374 1366.411367.435
1370.2551371.4391372.725  1374.1  1376.91379.4451383.4491387.4521391.4561395.459
1399.4621401.0141401.9531403.4661404.8591406.1281407.4691408.7041410.3041411.473
1415.4761419.4791424.0841427.0061427.9291431.181 1431.491435.6191439.4641443.309
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  2052.72052.7362053.3962053.7632054.1162054.4472054.836 2055.422055.557 2056.26
 2056.26
      13  14.737  15.199  15.621  18.934  19.449  23.131  27.106  27.328  30.934
  31.525  34.762  35.723   38.59   39.92  42.419  43.229  44.117  46.247  47.233
  48.314  50.075  51.237  52.511  53.903  55.241  56.709  57.731  59.246   63.25
  65.103  65.388  67.254  71.258  73.044  73.497  75.263  79.267  83.271  84.529
  86.089  87.275  88.357  90.286  91.279  95.284  98.681  99.842 103.292 107.075
 107.498 111.326 115.305 118.983 119.667 122.811 127.317 131.322 135.326  139.33
 141.952 143.334  145.78 149.047 149.609 151.343 155.347 159.351 161.093 161.639
 163.355 164.922 165.836  167.36  168.75 170.033 171.364 175.368 178.427 179.372
 180.234 182.625 183.377 184.063 186.822 187.381 187.891 191.385 195.216 199.413
 203.204 203.611 207.032 207.808  210.86 212.005 214.688  215.41 219.415 220.399
 222.345 223.419 224.597 226.173 227.423 228.794 230.001 231.427 235.432 237.188
 237.658 239.436  243.44 245.314 245.583 247.444 251.448  252.97 253.977 255.453
 256.799 258.174 259.457 260.627 262.371 263.461 264.455 266.569 267.465 268.283
 270.766  271.47 275.474  275.94  279.16 279.768 283.482 283.596 287.486 291.253
 291.491 291.752 295.081 295.949 299.499 303.503 304.343 306.565 311.512 315.516
  319.52 321.878 323.524 327.529 331.533 335.537 339.541 341.019 342.118 343.546
  347.55 351.554 352.504  354.71 358.907 360.161 363.567 367.571 375.579 379.302
  383.13  384.09 386.958 387.592 391.596 395.601 398.443 402.271 405.076 406.099
 407.613 409.273 409.927 411.617 415.622 419.626  423.63  425.24 426.062 427.634
 431.639 434.457 435.643 436.725 440.553 442.851 443.651 447.656 451.245 455.443
  459.64 463.837 467.351 471.681 472.231 475.007 476.444     479  508.54  540.63
  542.93  543.83  602.37  634.91  666.28  695.65  730.13  781.94  794.08  856.47
  856.47   859.6  890.31  935.75 937.411 944.084 948.515 952.523 955.393 956.531
 960.539 962.931 968.555  970.47  974.24 978.009 980.579 984.587 988.5951000.611
1004.3951011.9341013.4471015.7031016.6511020.6591026.2831027.0121028.6751030.562
1034.5511036.6911040.6991044.7071048.7151051.9561053.3981056.7311060.5141064.064
1072.7631076.7711077.6291079.7841083.2761084.8611093.0271096.831 1100.221101.193
1105.2761109.3591110.3871113.4431115.4031117.1651121.6091125.6921127.3311128.342
 1130.721133.858 1139.281140.5571142.1861143.7851146.3511149.2961151.015 1153.47
1154.681 1163.651167.1761169.6121176.0681178.0041179.6711183.8361185.7531188.001
1188.9811192.3591200.4961204.6611206.7131208.3511211.5791212.9911214.8071217.156
1218.0361221.2641224.4921225.4861227.7211229.6511235.4211237.9811240.6341242.146
1244.8951249.7761254.6411256.7751259.9161262.8831271.5371275.0181277.5881279.064
1281.0621284.6191295.2441299.2891302.1961303.3341305.7121307.3671311.3711315.374
1319.3781321.7421323.3811324.8911325.9171327.3841328.7361330.0931331.3881335.391
1338.444 1340.271342.6191344.115 1347.961351.805 1355.651361.523 1363.341363.496
1367.1851367.6721371.4221374.8751376.023 1378.721380.1981384.374 1386.411387.435
1390.2551391.4391392.725  1394.1  1396.91399.4451403.4491407.4521411.4561415.459
1419.4621421.0141421.9531423.4661424.8591426.1281427.4691428.7041430.3041431.473
1435.4761439.4791444.0841447.0061447.9291451.181 1451.491455.6191459.4641463.309
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  2052.72052.7362053.3962053.7632054.1162054.4472054.836 2055.422055.557 2056.26
 2056.26
Pier Skew, UpSta & Num, DnSta & Num=  ,582.37, 2 ,619.99, 2 , 0 , 0 , 0 ,,
       3       3
       0  2056.5
       3       3
       0  2056.5
Pier Skew, UpSta & Num, DnSta & Num=  ,646.28, 2 ,683.76, 2 , 0 , 0 , 0 ,,
       3       3
       0  2056.5
       3       3
       0  2056.5
Pier Skew, UpSta & Num, DnSta & Num=  ,710.13, 2 ,747.61, 2 , 0 , 0 , 0 ,,
       3       3
       0  2056.5
       3       3
       0  2056.5
Pier Skew, UpSta & Num, DnSta & Num=  ,774.08, 2 ,811.67, 2 , 0 , 0 , 0 ,,
       3       3
       0  2056.5
       3       3
       0  2056.5
BR Coef=-1 ,-1 , 0 ,, 0 ,,,0.8,0,1.2,0,
WSPro=,,,, 1 ,,,, 0 ,,,, 0 ,,,,-1 ,-1 ,-1 , 0 , 0 , 0 , 0 , 0
BR U #Sta/Elev= 442
       0 2222.13     1.9 2221.02     5.9 2218.35    10.1  2215.7    17.9  2210.5
    21.9 2208.15      30    2203      38 2198.26      42 2195.58      50 2190.77
      54  2188.5      62 2183.29    65.1 2181.45      70 2178.44      74 2176.05
    78.2 2173.69      82 2171.45    86.1 2168.72    90.1 2166.27    94.9 2163.42
    99.2 2160.95   102.1  2159.2   106.1 2156.57   110.1 2154.08   114.1 2151.67
   122.1 2146.54   130.1 2141.28   134.1 2138.73   138.1 2136.29   142.2  2133.6
   142.5 2133.35     146 2130.83   150.1  2128.4   154.2 2126.12   157.6  2123.7
   170.2 2115.28   182.2  2107.8   186.2  2105.4   190.2 2102.86   195.5 2099.85
   198.3 2098.21     203 2094.85   205.6 2093.15   210.3 2090.32   218.3 2085.31
   222.3    2083   230.3 2078.25   234.3 2075.96   238.3 2073.91   242.3 2071.98
   250.3 2067.41   254.3 2064.83   258.4 2061.01   262.4 2056.93   266.4 2054.47
   270.4 2053.71   278.7 2053.49   282.3 2053.32   298.4 2052.23   305.2 2052.08
   310.4 2051.91   316.5 2051.62   341.9 2051.11   354.7 2051.05   358.5 2050.97
   362.5  2050.8   366.5 2050.77   370.6 2050.62   382.6 2050.57   384.6 2050.58
   386.6  2050.6   388.4 2050.71   388.8 2050.74   390.6 2050.85   394.6 2051.52
   397.3 2051.84   398.6 2051.98   402.6 2052.18   403.6 2052.17   406.6 2052.19
   410.6 2052.06   414.6 2051.76   418.6 2051.58   418.7 2051.58   419.7 2051.58
   422.5 2051.57   422.6 2051.57   426.3 2051.45   426.6 2051.43   434.7  2051.3
   442.7 2051.36   454.7 2051.98   456.5 2051.99   456.9 2051.98   462.7 2051.92
   474.7 2052.41   478.7 2052.31   482.5  2052.4   486.8 2052.38   490.6 2052.19
   494.8 2052.05   498.1 2051.88   498.8 2051.85   503.7 2051.16   505.7 2050.81
   510.8 2050.12   514.8 2049.38   516.5 2049.07   517.1 2049.02   518.8 2048.69
  526.54 2047.69  537.63 2042.84  543.97 2040.33  550.46 2038.15  562.51 2037.09
   606.1 2036.11  675.42  2035.6  733.44 2035.57  784.67  2037.1  801.55 2037.86
  807.54 2040.32   814.6 2042.97  823.24 2048.08   836.1 2054.85   838.6 2053.55
   839.4 2053.88   840.2 2054.27   842.4 2055.37   843.4 2055.82   848.7 2057.15
   851.4 2057.93     853    2058   853.8 2058.06   855.4 2058.13   857.2 2058.14
   857.6 2058.14   863.4 2058.22   865.7 2058.38   867.4  2058.5     870 2058.45
   874.2 2058.37   875.4 2058.33   879.4 2058.18   883.4 2058.25     884 2058.26
     887 2058.31   899.2 2058.39   899.5 2058.39   899.8 2058.39     903 2058.39
   903.5 2058.39   904.1 2058.37   906.7 2058.28   907.5 2058.26   908.3 2058.26
   910.5  2058.2   911.5  2058.2   914.3 2058.25   915.5 2058.29   916.8 2058.32
   918.1 2058.35   919.5 2058.38   921.1 2058.41   921.9 2058.42   927.5 2058.59
   935.5 2058.93     937 2058.94   939.5 2058.97   940.8 2058.95   942.4 2058.92
   943.6 2058.91   944.6    2059   947.6 2059.29   948.4  2059.5   950.9 2060.26
   951.6 2060.44   955.6 2061.03   959.4 2061.37   959.6 2061.38   959.7 2061.38
   962.1 2061.37   963.6 2061.35   971.6 2061.52   972.2 2061.49   974.8 2061.38
   975.6 2061.35   979.6 2061.54   980.7 2061.55   982.4 2061.53   983.6 2061.55
     985 2061.59   986.2 2061.64   987.6 2061.69   989.2 2061.76     990  2061.8
   991.6 2061.87   995.6  2062.2   997.6 2062.48   999.6 2062.81  1001.3 2063.12
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BR U #Mann= 12
       0      .1   266.4    .016   278.7     .06   454.7     .07  537.63     .03
   814.6      .1   899.2    .016   935.5     .06  1141.3     .07    1266    .016
  1276.1      .1  1340.2      .1
BR D #Sta/Elev= 441
       0 2247.12     5.1 2243.52    13.1 2238.05    17.1 2235.12    25.1 2229.79
    33.2 2224.13    37.2 2221.61    41.2 2218.99    45.2 2216.29    53.3 2211.09
    54.2 2210.47    57.3 2208.58    61.3 2205.97    65.3  2203.5    69.8 2200.45
    74.2 2197.35    76.3 2196.01    85.4 2189.94      92  2185.5    93.4 2184.51
   101.5 2179.34   113.5 2171.95   116.7 2169.92   124.1 2165.06   127.7 2162.64
   129.6 2161.44   133.6 2158.76   138.8 2155.38   153.5 2145.42   161.7 2139.64
   162.9 2138.91   169.8 2134.31   171.7 2133.12   173.8 2131.87   177.8 2129.29
   181.8 2126.46   185.8 2123.71   193.9 2118.34   207.2 2110.04   215.9 2104.42
     218 2103.17     222 2100.43   223.3 2099.61     226 2097.81     230 2095.33
     234  2092.7   238.1 2089.84   246.1 2084.84   250.1 2082.21   254.1 2079.76
   256.3 2078.33   266.2 2072.16   267.4 2071.45     271 2069.23   278.2 2065.14
   278.4 2065.07   282.3 2063.02   286.9 2060.84   290.3 2059.28   291.4 2058.69
   294.3 2057.06   298.3 2054.24   302.3 2053.12   306.4 2053.07   307.8    2053
   310.4 2052.89   318.4 2051.89   322.4 2051.54   322.4 2051.53   326.8 2051.34
   330.5 2051.24   350.6 2050.99   359.2 2050.57   370.2 2050.52   370.6 2050.52
   374.7 2050.67   378.7 2050.69   386.7 2050.61   390.7 2050.45   392.3 2050.42
   393.3 2050.41   394.7 2050.39   398.8 2050.55   402.1 2050.76   402.8  2050.8
   403.3 2050.85   406.6 2051.14   414.3 2051.96   430.9 2053.53   438.9 2054.25
     443 2054.42   443.7 2054.43   446.4 2054.44     447 2054.44     451 2054.35
   454.8 2053.91     455 2053.89     459 2053.73     463 2053.64   464.2 2053.64
   465.8 2053.61   467.1 2053.61   475.1  2053.9   477.5 2053.96   480.5    2054
   481.9 2053.99   483.1    2054   495.2 2053.69   503.2 2053.72   507.2 2053.68
   511.2 2053.44   515.3 2053.06   523.3 2052.72   527.3 2052.27   531.3 2051.63
     532  2051.5   534.8 2051.03   535.8 2050.81   539.7 2049.85   543.3 2048.78
   543.5 2048.74   547.3 2047.69   547.3 2047.68   551.1 2046.67   551.4  2046.6
   555.4 2044.69   569.6 2040.42  580.99 2037.64  598.56  2037.5  631.44 2036.46
  653.17 2036.22   695.3  2035.1  720.24  2035.6  759.22 2036.54  790.39 2036.36
  816.76  2037.4  823.07 2037.36   829.4 2040.18  842.24 2045.47   863.7 2049.32
   864.3  2049.5   867.3 2050.59   867.7 2050.72   868.1 2050.82   871.5 2051.83
   871.7 2051.88   879.7 2053.71   883.7 2054.45   884.2  2054.5   887.2 2054.85
   887.7 2054.91   888.4 2054.97     891 2055.19   891.8 2055.26   892.6 2055.36
   895.8 2055.77   896.8 2055.94   898.6 2056.23   899.8 2056.41   902.5 2056.93
   903.8 2057.19   906.3 2057.55   907.8 2057.77   910.1 2057.85   911.8 2057.92
   926.3 2057.96     933 2058.01   935.8 2058.05   936.8 2058.06   938.9 2058.09
   940.6 2058.12   943.1 2058.18   947.8 2058.23   948.3 2058.21   951.5 2058.05
   955.8 2057.97   955.9 2057.98   959.9 2058.42   963.8 2058.75   964.2 2058.79
   972.6  2059.8   975.9 2060.11   976.8  2060.2   978.8 2060.44   979.9 2060.54
     981 2060.67   982.6  2060.9   983.9 2061.04   985.2 2061.16   987.9 2061.41
   991.9 2061.68   995.9 2061.78   997.8 2061.82   999.9 2061.88  1013.2 2062.72
  1014.7 2062.83  1015.9 2062.91    1017 2062.99  1018.9 2063.13  1020.8 2063.26
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BR D #Mann= 12
       0      .1   290.3    .016   302.3     .06   465.8    .016   495.2     .07
   569.6     .03   829.4      .1   892.6    .016   948.3     .05    1080     .07
  1265.2    .016  1280.2      .1
BC Design=,, 0 ,, 0 ,,,,,,
BC Use User HTab Curves=0
BC User HTab FreeFlow(D)= 0

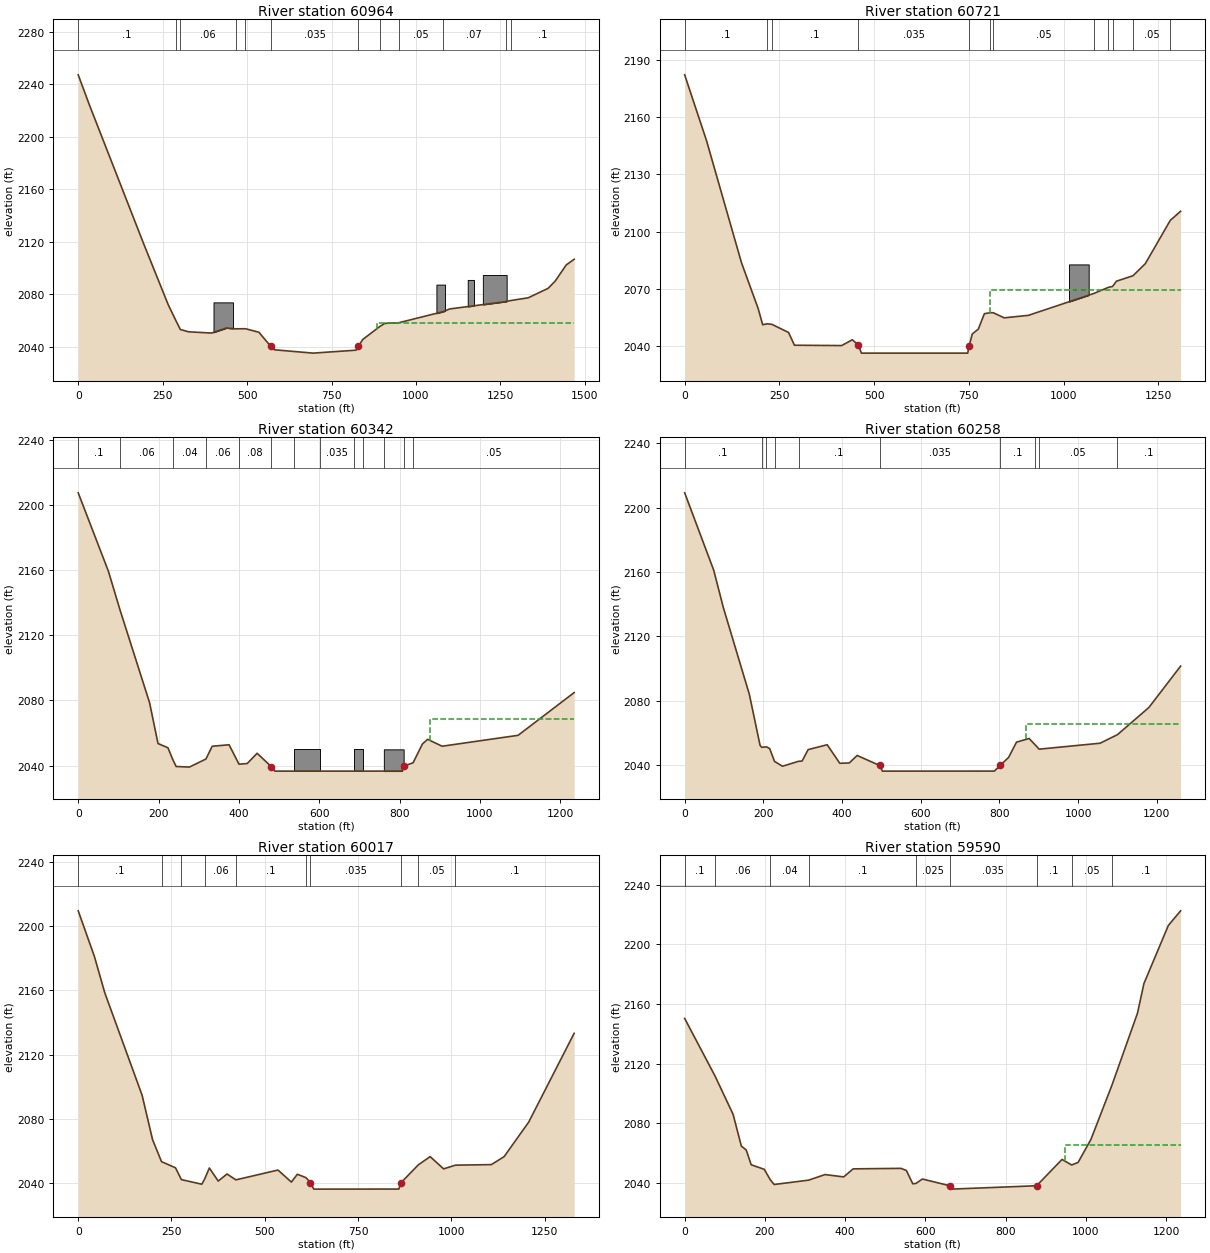
Type RM Length L Ch R = 1 ,60964   ,245.3,242.4,243.2
BEGIN DESCRIPTION:
structure xs 2
END DESCRIPTION:
XS GIS Cut Line= 3
2206629.20896121411383.1969749952206102.29897025411334.018709172
2205164.39918634411288.353176622
#Sta/Elev= 30
       0 2247.12    33.2 2224.13   193.9 2118.34   266.2 2072.16   290.3 2059.28
   302.3 2053.12   326.8 2051.34   394.7 2050.39   438.9 2054.25   465.8 2053.61
   495.2 2053.69   534.8 2051.03   569.6 2040.42  580.99 2037.64   695.3  2035.1
  823.07 2037.36   829.4 2040.18  842.24 2045.47   892.6 2055.36   907.8 2057.77
   948.3 2058.21    1080 2066.67    1100 2068.76  1265.2 2074.33  1280.2 2075.15
  1332.3 2077.26  1391.3 2084.49  1412.4 2090.09  1444.7 2102.26  1468.2 2106.62
#Mann= 12 ,-1,0
       0      .1       0   290.3    .016       0   302.3     .06       0
   465.8    .016       0   495.2     .07       0   569.6    .035       0
   829.4      .1       0   892.6    .016       0   948.3     .05       0
    1080     .07       0  1265.2    .016       0  1280.2      .1       0
#XS Ineff= 2 , 0
           535.6 2050.69   883.8          2057.8
Permanent Ineff=
       F       F
#Block Obstruct= 4 ,-1
  400.49  458.06 2073.77 1060.46 1086.01  2087.3 1153.13 1171.56 2090.87
 1197.92  1268.4 2094.59
Bank Sta=569.6,829.4
XS Rating Curve= 0 ,0
Exp/Cntr(USF)=0,0
Exp/Cntr=0.5,0.3

Type RM Length L Ch R = 1 ,60721   ,382.9,379.1,358.1
BEGIN DESCRIPTION:
structure xs 1 - channel burned 3.61':
lidar invert = 2039.75
interpolated effective invert = 2036.14
END DESCRIPTION:
Node Name=A
XS GIS Cut Line= 2
2206537.87789611411116.2292462412205231.14111853411045.974580779
#Sta/Elev= 30
       0 2182.32    57.8 2147.66   149.9 2083.62     194  2059.5   205.8 2051.06
     218 2051.54     230 2051.26   274.1    2047   289.6 2040.29   414.3 2040.11
   442.3 2043.17  458.02 2040.39   466.4 2036.14   746.8 2036.14   750.8 2039.97
   758.8 2046.18   774.8 2048.76   790.8 2056.86   806.6 2057.37   814.2 2057.36
   842.9 2054.68     907 2055.98  1080.3 2067.53  1118.3 2070.72  1128.9 2071.13
  1139.3 2073.93    1183 2076.79  1215.5 2083.14  1281.3 2105.87  1308.6 2110.67
#Mann= 12 ,-1,0
       0      .1       0     218    .016       0     230      .1       0
  458.02    .035       0   750.8     .08       0   806.6    .016       0
   814.2     .05       0  1080.3     .06       0  1118.3    .016       0
  1128.9     .06       0    1183     .05       0  1281.3      .1       0
#XS Ineff= 2 , 0
                           805.5         2069.33
Permanent Ineff=
       F       F
#Block Obstruct= 1 ,-1
 1013.97 1066.05 2082.74
Bank Sta=458.02,750.8
XS Rating Curve= 0 ,0
Exp/Cntr(USF)=0,0
Exp/Cntr=0.3,0.1

Type RM Length L Ch R = 1 ,60342   ,76.6,83.9,107.7
BEGIN DESCRIPTION:
location of decommissioned structure - cross section cut across old deck location to capture area and mannings update to reflect conditions
remains of low watercourse crossing added as blocked obstructions - elevation assumed as 10yr WSEL
channel burned 2.74':
lidar invert = 2039.31
interpolated effective invert = 2036.57
END DESCRIPTION:
XS GIS Cut Line= 4
2206637.22852724410806.4412397822206207.61343548410702.982911562
2205774.49128175410717.0111594562205416.77096045410685.447601694
#Sta/Elev= 30
       0  2207.4    75.1 2159.31   103.9 2135.65   177.7 2078.51   198.6 2053.51
   223.3 2050.92   235.6 2043.57   243.8 2039.41   276.7 2039.06   317.9 2043.99
   333.5 2051.84   375.5 2052.76   400.2 2040.83   420.7 2041.24   445.3 2047.52
  480.55 2039.35   489.4 2036.57   536.1 2036.57   602.2 2036.57   687.2 2036.57
   709.4 2036.57   760.7 2036.58   805.5  2036.6   811.3 2039.76   833.5 2041.68
   856.8 2053.24   869.9 2056.09   905.7 2051.86  1094.9 2058.55  1234.4 2084.78
#Mann= 13 ,-1,0
       0      .1       0   103.9     .06       0   235.6     .04       0
   317.9     .06       0   400.2     .08       0  480.55    .035       0
   536.1    .016       0   602.2    .035       0   687.2    .016       0
   709.4    .035       0   760.7    .016       0   811.3     .08       0
   833.5     .05       0
#XS Ineff= 2 , 0
                          876.35          2068.4
Permanent Ineff=
       F       F
#Block Obstruct= 3 ,-1
   536.1   602.2 2049.94   687.2   709.4 2049.94   760.7     810 2049.94
Bank Sta=480.55,811.3
XS Rating Curve= 0 ,0
Exp/Cntr(USF)=0,0
Exp/Cntr=0.3,0.1

Type RM Length L Ch R = 1 ,60258   ,255.2,241.4,230
BEGIN DESCRIPTION:
channel burned 2.75' to transition to approximate zone:
lidar elevation = 2039.22
interpolated invert = 2036.47
END DESCRIPTION:
XS GIS Cut Line= 3
2206652.73332675410707.7429204732206311.16489226410645.342290903
2205400.01218832 410583.33105349
#Sta/Elev= 30
       0 2209.11    73.8 2161.12    98.2 2137.99   164.3 2084.18   191.5 2052.59
   195.7 2051.23   207.9 2051.54   216.1 2050.44   228.3 2042.52   248.6  2039.5
   289.3 2042.56   298.4  2042.7   313.7 2049.81   362.2 2052.84   394.3 2041.32
   418.4 2041.55   438.4 2046.19  495.37 2039.98   502.6 2036.47   787.2 2036.49
  801.94 2040.01   823.3 2044.98   843.4 2054.45   875.4 2056.72   890.7  2052.8
   900.9 2050.09  1055.8 2053.78  1099.9 2059.08  1179.8 2075.93  1260.5 2101.61
#Mann= 10 ,-1,0
       0      .1       0   195.7    .016       0   207.9      .1       0
   228.3     .04       0   289.3      .1       0  495.37    .035       0
  801.94      .1       0   890.7    .016       0   900.9     .05       0
  1099.9      .1       0
#XS Ineff= 2 , 0
                          868.39         2065.73
Permanent Ineff=
       F       F
Bank Sta=495.37,801.94
XS Rating Curve= 0 ,0
Exp/Cntr(USF)=0,0
Exp/Cntr=0.3,0.1

Type RM Length L Ch R = 1 ,60017   ,428.1,426.9,429.1
BEGIN DESCRIPTION:
channel burned 2.68' to transition to approximate zone:
lidar elevation = 2038.88
interpolated invert = 2036.20
END DESCRIPTION:
XS GIS Cut Line= 2
2206759.49415715410393.7975375912205430.32907518 410376.99269135
#Sta/Elev= 30
       0  2209.5    43.3 2181.16    71.3  2158.4   171.3 2094.65   199.3 2067.01
   223.3 2053.32   260.7 2049.48   276.5 2042.13   331.3 2039.26   339.3  2042.7
   351.5 2049.36   375.3 2041.22   398.9 2045.63   422.6 2041.97   535.4 2048.08
   571.4  2040.6   587.4 2045.46   610.5 2043.34   622.6 2040.23   631.4  2036.2
   859.4 2036.24   865.1 2040.17   911.4 2051.28   943.4 2056.45   979.4 2048.81
  1011.2 2051.13  1107.4 2051.46  1141.6 2056.44  1207.4  2077.9  1329.3 2133.24
#Mann= 10 ,-1,0
       0      .1       0   223.3     .06       0   276.5     .04       0
   339.3     .06       0   422.6      .1       0   610.5    .025       0
   622.6    .035       0   865.1      .1       0   911.4     .05       0
  1011.2      .1       0
Bank Sta=622.6,865.1
XS Rating Curve= 0 ,0
Exp/Cntr=0.3,0.1

Type RM Length L Ch R = 1 ,59590   ,492.9,510,523.6
BEGIN DESCRIPTION:
channel burned 1.98' to transition to approximate zone:
lidar elevation = 2037.69
interpolated invert = 2035.71
END DESCRIPTION:
XS GIS Cut Line= 3
2206806.19195252410057.9334369712206352.57299228409960.427887471
     2205580.699      409953.854
#Sta/Elev= 30
       0 2150.27    75.7  2111.6   120.7 2085.89   141.2 2064.61   153.4 2061.98
   165.7 2052.07   198.4 2048.99     213 2042.12     223 2038.82   308.9 2041.74
   349.8 2045.48   396.3 2043.92   419.9 2049.31     539 2049.65   552.4 2048.23
   568.4 2039.32   576.4 2039.53   592.4 2042.49  660.49    2038   664.4 2035.71
  877.04 2037.98   940.4 2055.65   964.4 2051.92   980.4 2053.63  1012.4 2069.07
  1064.4 2105.22  1128.4 2153.79  1144.4 2173.63  1205.3 2212.69  1235.9  2222.5
#Mann= 9 ,-1,0
       0      .1       0    75.7     .06       0     213     .04       0
   308.9      .1       0   576.4    .025       0  660.49    .035       0
  877.04      .1       0   964.4     .05       0  1064.4      .1       0
#XS Ineff= 2 , 0
       0                   948.8       0    2065
Permanent Ineff=
       F       F
Bank Sta=660.49,877.04
XS Rating Curve= 0 ,0
Exp/Cntr=0.3,0.1