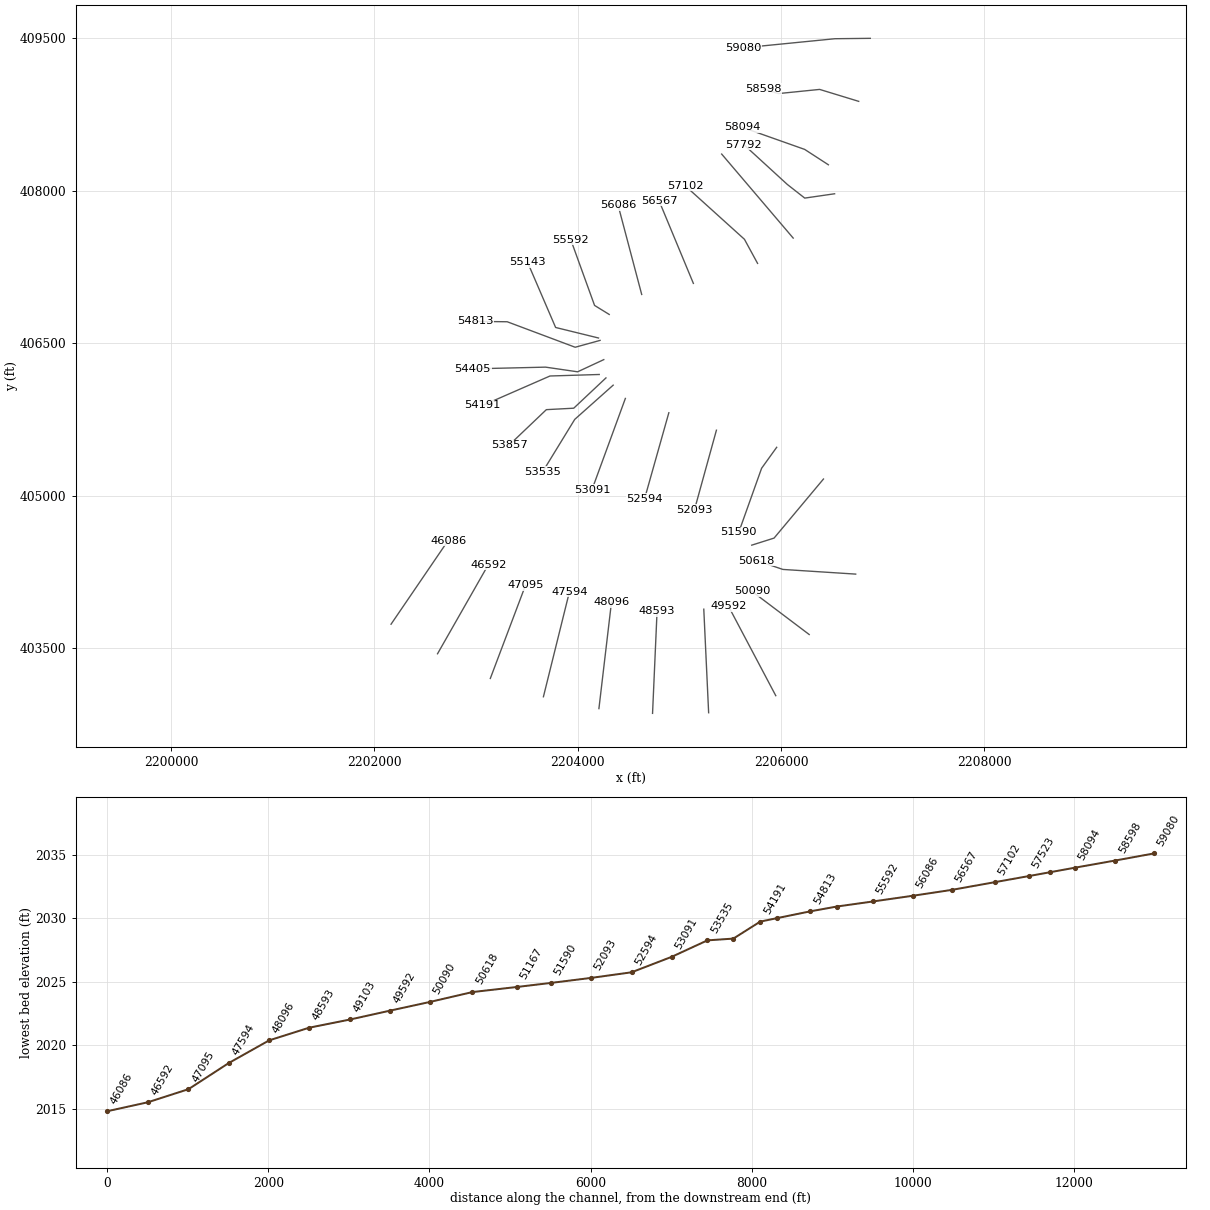
HEC-RAS study GRNBRRRV.prj: GRNBRRRV

--- GRNBRRRV.g01 (geometry) --- (continued)

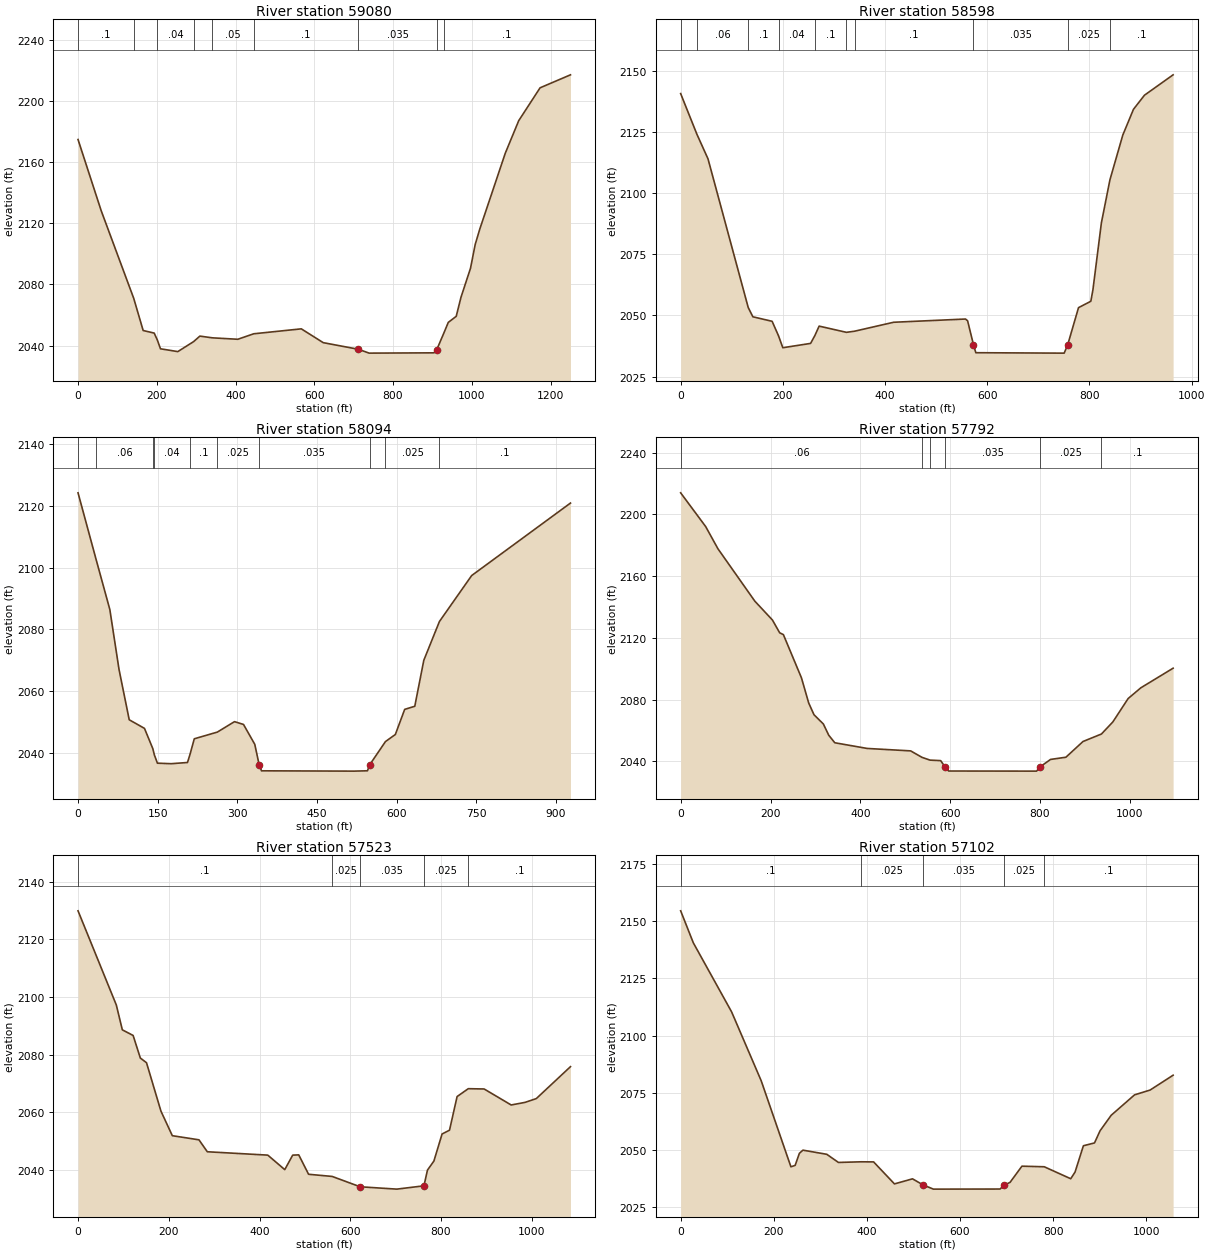
Type RM Length L Ch R = 1 ,59080   ,485.3,481.9,482.2
BEGIN DESCRIPTION:
channel burned 1.59' to transition to approximate zone:
lidar elevation = 2036.72
interpolated invert = 2035.13
END DESCRIPTION:
XS GIS Cut Line= 3
2206877.53567802409499.1850152022206530.19204598409495.436445972
2205631.41097441409406.216678609
#Sta/Elev= 30
       0 2174.67    58.7 2128.25   141.4 2070.93   165.4 2049.91   193.4 2048.22
   201.4 2043.71   209.4 2037.96   253.4 2036.12   293.4 2042.64   309.4 2046.24
   341.4 2045.12   405.7 2044.18   446.3 2047.77     567 2050.99   622.7 2041.97
  711.79 2037.66   739.3 2035.13   904.1 2035.32  911.22 2037.49   928.2 2047.75
   940.3 2055.22   960.4 2059.15   972.4 2071.52   996.6 2090.49  1008.6 2106.07
  1020.4 2116.28    1085 2165.71  1119.1 2186.96  1173.4 2208.46  1250.6 2216.94
#Mann= 9 ,-1,0
       0      .1       0   141.4     .06       0   201.4     .04       0
   293.4      .1       0   341.4     .05       0   446.3      .1       0
  711.79    .035       0  911.22     .05       0   928.2      .1       0
Bank Sta=711.79,911.22
XS Rating Curve= 0 ,0
Exp/Cntr=0.3,0.1

Type RM Length L Ch R = 1 ,58598   ,565.1,504.4,459.2
BEGIN DESCRIPTION:
channel burned 1.96' to transition to approximate zone:
lidar elevation = 2036.53
interpolated invert = 2034.57
END DESCRIPTION:
XS GIS Cut Line= 4
2206763.32725891408879.2890497442206379.07509516 408996.71505535
2205974.31570567408955.7572599842205826.02259186 409001.08530865
#Sta/Elev= 30
       0 2140.76      32 2124.03    53.5 2114.07   132.2 2053.24   141.3 2049.44
     179 2047.59   191.5 2041.66   199.9 2036.78   254.3 2038.55   262.6 2041.75
     271 2045.62   324.4 2043.08   340.4 2043.54   416.8  2047.2   557.4 2048.52
   561.5 2047.82  573.05    2038   577.6 2034.74   742.4 2034.57   750.5 2034.57
  757.28 2037.87   778.6 2053.18   802.7 2055.79   806.8 2060.51   823.4 2087.94
   840.1  2105.5   865.2 2123.76   886.1 2134.32   907.6 2140.09   963.7 2148.44
#Mann= 10 ,-1,0
       0      .1       0      32     .06       0   132.2      .1       0
   191.5     .04       0   262.6      .1       0   324.4     .05       0
   340.4      .1       0  573.05    .035       0  757.28    .025       0
   840.1      .1       0
Bank Sta=573.05,757.28
XS Rating Curve= 0 ,0
Exp/Cntr=0.3,0.1

Type RM Length L Ch R = 1 ,58094   ,366.8,301.8,265.7
BEGIN DESCRIPTION:
channel burned 2.09' to transition to approximate zone:
lidar elevation = 2036.09
interpolated invert = 2034.0
END DESCRIPTION:
XS GIS Cut Line= 3
     2206465.082408255.2828971172206232.10888826408406.440945675
     2205619.802      408623.283
#Sta/Elev= 30
       0 2124.28    33.8  2102.8    59.9 2086.41    77.2 2066.96    96.4 2050.66
   125.1 2047.87   140.8  2041.3   143.7 2039.28   149.5 2036.58   175.5 2036.41
   206.1  2036.8   210.9 2039.46   218.9 2044.49   262.3 2046.66   294.6 2050.05
   311.6 2049.14   332.8  2042.7  341.09 2036.05   345.5  2034.1   519.5    2034
     545 2034.11   549.1 2036.03   578.9 2043.59   597.5 2045.88   615.1 2054.03
   634.1 2055.04   651.1 2069.95   680.5 2082.53   741.2 2097.44   927.3 2120.96
#Mann= 10 ,-1,0
       0      .1       0    33.8     .06       0   140.8      .1       0
   143.7     .04       0   210.9      .1       0   262.3    .025       0
  341.09    .035       0   549.1      .1       0   578.9    .025       0
   680.5      .1       0
Bank Sta=341.09,549.1
XS Rating Curve= 0 ,0
Exp/Cntr=0.3,0.1

Type RM Length L Ch R = 1 ,57792   ,303.3,269,262.7
BEGIN DESCRIPTION:
channel burned 2.16' to transition to approximate zone:
lidar elevation = 2035.81
interpolated invert = 2033.65
END DESCRIPTION:
XS GIS Cut Line= 4
2206526.34124837407970.1177197132206232.55892765407927.561496121
2206061.04986056408061.9136081922205632.19765027408454.626587281
#Sta/Elev= 30
       0 2213.96    55.7 2192.09      83 2177.71   165.1 2143.78   204.3 2131.55
   220.4 2123.28   228.7 2122.08   268.9 2094.09     285 2077.82   296.8 2070.19
   317.7 2064.18   329.6 2056.93   343.1 2052.03   415.1 2048.35     512 2046.76
   537.3 2042.56   555.1 2040.78   578.8 2040.45  589.24 2036.05   596.5 2033.72
   792.3 2033.65   800.8 2036.56   823.4 2041.23   857.6 2042.66   895.6 2052.84
   936.7  2057.7   962.1 2065.54   996.1 2080.68  1024.4 2087.64  1096.2 2100.33
#Mann= 6 ,-1,0
       0     .06       0   537.3      .1       0   555.1    .025       0
  589.24    .035       0   800.8    .025       0   936.7      .1       0
Bank Sta=589.24,800.8
XS Rating Curve= 0 ,0
Exp/Cntr(USF)=0,0
Exp/Cntr=0.3,0.1

Type RM Length L Ch R = 1 ,57523   ,405.8,420.4,434.1
BEGIN DESCRIPTION:
channel burned 1.72' to transition to approximate zone:
lidar elevation = 2035.06
interpolated invert = 2033.34
END DESCRIPTION:
XS GIS Cut Line= 2
2206118.87263049407534.2808326052205415.36226304 408360.66458615
#Sta/Elev= 30
       0 2129.85    84.4 2097.18    97.6 2088.58   121.4 2086.63   137.3  2078.8
   150.9 2077.18   182.7  2060.4   207.8 2051.87   266.5 2050.44   284.9  2046.3
   418.2 2045.13   455.6  2040.1   473.1 2045.13   486.4 2045.22   508.1 2038.49
   560.1 2037.74  621.87 2034.15   702.5 2033.34  762.34 2034.49   770.1 2039.93
   784.3 2043.08   802.3 2052.46   818.7 2053.78   835.4 2065.44   860.1 2068.17
     895 2068.07   954.6 2062.52   985.3 2063.43    1010 2064.74  1085.3 2075.81
#Mann= 5 ,-1,0
       0      .1       0   560.1    .025       0  621.87    .035       0
  762.34    .025       0   860.1      .1       0
Bank Sta=621.87,762.34
XS Rating Curve= 0 ,0
Exp/Cntr(USF)=0,0
Exp/Cntr=0.3,0.1

Type RM Length L Ch R = 1 ,57102   ,582.4,535.7,487.9
BEGIN DESCRIPTION:
channel burned 0.61' to transition to approximate zone:
lidar elevation = 2033.47
interpolated invert = 2032.86
END DESCRIPTION:
XS GIS Cut Line= 3
2205768.51492369407285.2725364592205639.42549651407522.234422204
 2205054.7218208 408050.35428208
#Sta/Elev= 30
       0  2154.6    27.2  2140.6   109.4 2110.41     173 2080.26   236.8 2042.63
   245.9 2043.25     255 2048.52   262.6 2049.91   313.9 2048.09   338.9 2044.53
   387.4 2044.81   414.4 2044.77   459.2 2035.15     498 2037.36   520.6 2034.71
   542.8 2032.86     686  2032.9   694.6 2034.52   707.5 2035.83     733  2042.9
   780.9 2042.64   837.8 2037.41   847.1 2040.32     865 2051.83   888.9 2053.07
   900.8 2058.38   924.7 2065.16   974.9  2074.1  1008.3  2076.2  1057.7 2082.69
#Mann= 5 ,-1,0
       0      .1       0   387.4    .025       0   520.6    .035       0
   694.6    .025       0   780.9      .1       0
Bank Sta=520.6,694.6
XS Rating Curve= 0 ,0
Exp/Cntr=0.3,0.1

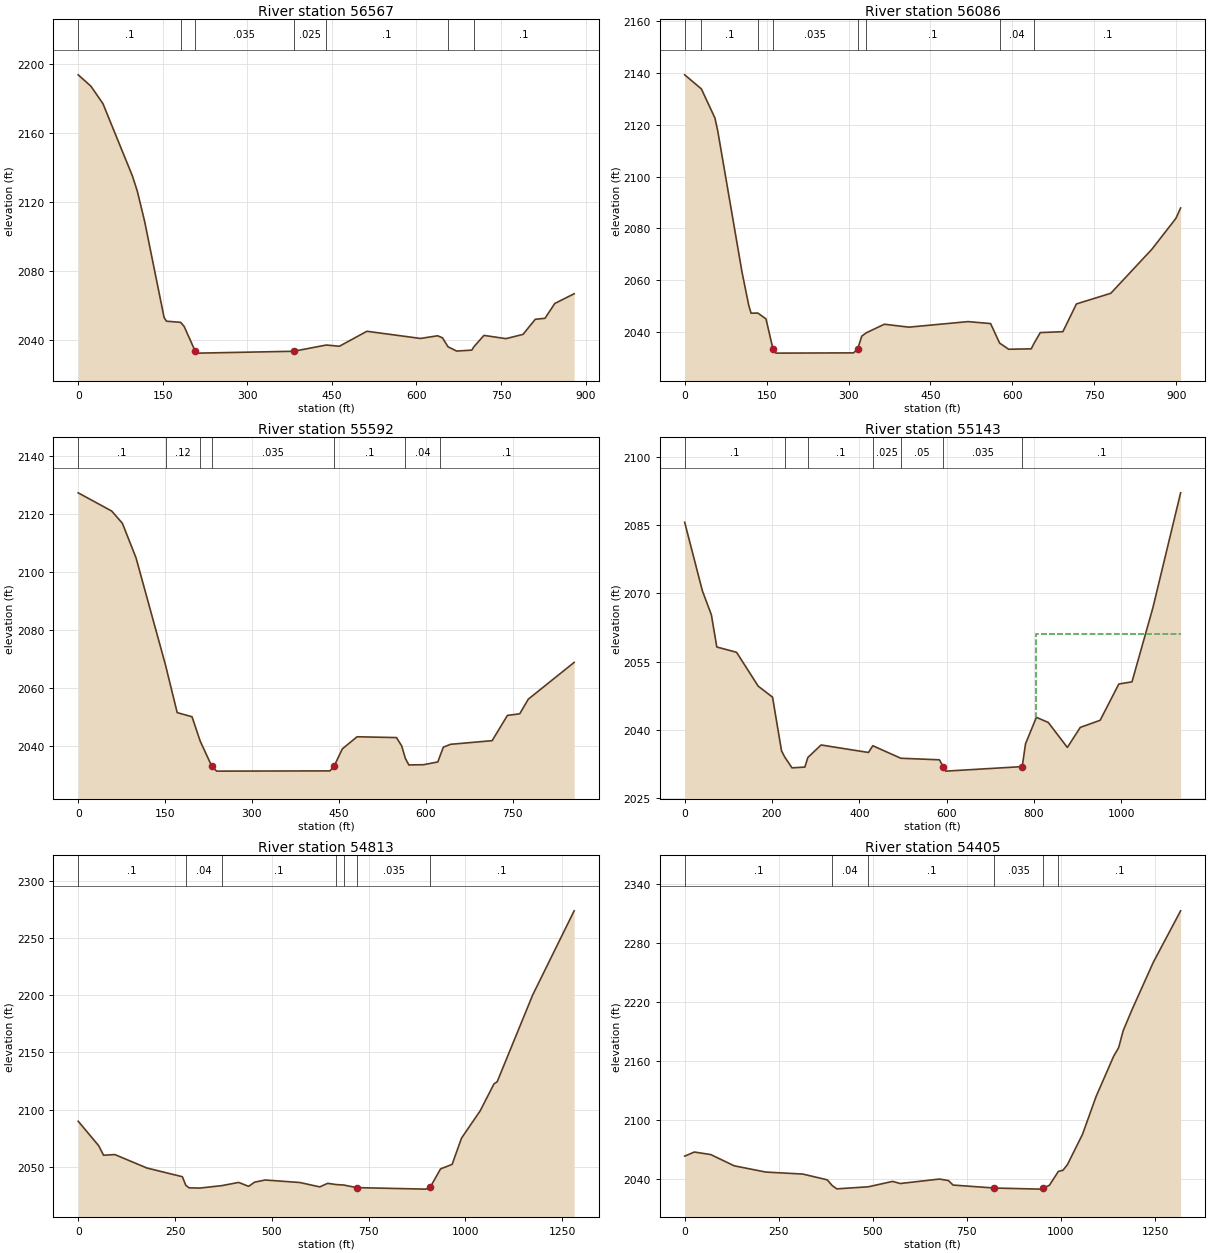
Type RM Length L Ch R = 1 ,56567   ,494.9,480.7,467
XS GIS Cut Line= 2
2205137.00251102407088.4375652922204799.47584624407900.886078577
#Sta/Elev= 30
       0 2193.95    22.5 2187.37    43.9 2177.19    96.1 2135.24   104.8 2126.43
   117.8 2108.86   152.4 2052.91   156.7  2050.8   181.7 2050.14   187.9  2047.8
  207.03 2033.75     213 2032.25     382 2033.33   440.1 2036.96   463.3 2036.24
   512.2 2044.95   607.2 2040.78   637.5 2042.33   646.2 2041.15   656.1 2035.93
   671.4 2033.45   698.2    2034     702 2035.97   719.8 2042.55   758.8 2040.67
   789.1 2043.14   810.8  2051.9   828.1  2052.5   845.4 2061.08   879.8 2066.76
#Mann= 7 ,-1,0
       0      .1       0   181.7    .025       0  207.03    .035       0
     382    .025       0   440.1      .1       0   656.1     .04       0
     702      .1       0
Bank Sta=207.03,382
XS Rating Curve= 0 ,0
Exp/Cntr=0.3,0.1

Type RM Length L Ch R = 1 ,56086   ,487.9,494.1,502.9
XS GIS Cut Line= 2
2204628.61225551406979.6349768262204396.34107631407857.596540986
#Sta/Elev= 30
       0 2139.37    30.6 2133.93    55.4 2122.67    60.5 2117.76     105 2063.12
   117.5 2050.09   121.6 2047.23     134 2047.28   148.9 2045.03   161.72033.391
   167.1 2031.79   309.2 2031.89   316.6  2033.3   324.3 2038.36   332.6 2039.65
   365.7 2042.96   410.6 2041.83   518.8 2043.97   560.2 2043.22   576.7 2035.68
   593.3 2033.29   634.7 2033.45   639.7 2035.55   651.2 2039.73   692.6 2040.08
   717.4  2050.8   780.4 2054.93   855.6 2071.95   899.5 2083.86   908.2  2087.9
#Mann= 8 ,-1,0
       0     .12       0    30.6      .1       0     134    .025       0
   161.7    .035       0   316.6    .025       0   332.6      .1       0
   576.7     .04       0   639.7      .1       0
Bank Sta=161.7,316.6
XS Rating Curve= 0 ,0
Exp/Cntr=0.3,0.1

Type RM Length L Ch R = 1 ,55592   ,443,449,455.4
XS GIS Cut Line= 3
2204309.16964161  406782.86461732204164.94486336406871.728260522
 2203931.2365896407517.549795365
#Sta/Elev= 30
       0 2127.16    57.8 2120.89    76.3 2116.66    99.8 2104.79   150.7 2067.88
   170.9 2051.48   196.5 2050.06   210.5 2041.73   230.5 2033.07   230.5 2033.06
   230.5 2033.04     239 2031.34   434.7 2031.42     442 2033.16     456 2039.01
   481.5 2043.17   549.5 2042.89   558.5    2040   564.7 2035.78   570.8 2033.47
   596.3 2033.55   620.9 2034.51   623.8 2036.11   630.4 2039.59   642.8 2040.57
   714.6 2041.83     741 2050.53   762.2 2051.07   777.1 2056.13   856.2 2068.77
#Mann= 7 ,-1,0
       0      .1       0   150.7     .12       0   210.5    .025       0
   230.5    .035       0     442      .1       0   564.7     .04       0
   623.8      .1       0
Bank Sta=230.5,442
XS Rating Curve= 0 ,0
Exp/Cntr=0.3,0.1

Type RM Length L Ch R = 1 ,55143   ,240.5,330,421.5
XS GIS Cut Line= 3
2204203.62951825406551.2224711112203781.81559858 406654.82449609
2203504.41928321407299.569334088
#Sta/Elev= 30
       0 2085.65    40.6 2070.57    61.2 2065.29    73.6 2058.23   118.9 2057.06
   168.3 2049.64   201.3  2047.2   221.9  2035.4   229.3 2034.03   245.9 2031.66
   275.4 2031.83   282.2 2033.94   312.5 2036.69   421.1 2035.04     431 2036.52
   495.2 2033.77   583.5 2033.43   592.7 2031.88     598 2030.94 773.2912031.932
   780.9 2036.96   805.8 2042.77   833.1 2041.63   876.7 2036.15   906.3 2040.55
   951.9 2042.12   994.6 2050.09  1024.8 2050.57  1072.7 2066.86  1136.2 2092.12
#Mann= 7 ,-1,0
       0      .1       0   229.3     .04       0   282.2      .1       0
     431    .025       0   495.2     .05       0   592.7    .035       0
 773.291      .1       0
#XS Ineff= 2 , 0
                          805.28         2061.11
Permanent Ineff=
       F       F
Bank Sta=592.7,773.291
XS Rating Curve= 0 ,0
Exp/Cntr=0.3,0.1

Type RM Length L Ch R = 1 ,54813   ,367.5,408.2,446.3
XS GIS Cut Line= 4
2204219.30913292406527.7254217722203974.26116855406460.223049273
2203305.41814025406711.0685459362202993.28064161406714.465694745
#Sta/Elev= 30
       0 2089.85      53 2068.43    65.5 2060.14    94.5 2060.74   177.5 2048.99
     269 2041.39   277.8 2033.91   286.3 2031.69   313.9 2031.47   370.8 2033.62
   414.5 2036.42   440.1 2032.99   455.4 2036.64   482.8 2038.53   572.5 2036.33
   623.8 2032.51   644.2 2035.61   666.5 2034.53   685.3 2034.16719.37422031.877
   897.2 2030.56908.8067  2032.1   935.7 2048.22   965.6 2052.17   989.8 2075.08
  1037.8 2098.81  1073.8  2122.5  1081.8 2124.24  1173.6 2200.06  1280.7 2273.55
#Mann= 7 ,-1,0
       0      .1       0   277.8     .04       0   370.8      .1       0
   666.5     .05       0   685.3    .025       0719.3742    .035       0
908.8067      .1       0
Bank Sta=719.3742,908.8067
XS Rating Curve= 0 ,0
Exp/Cntr=0.3,0.1

Type RM Length L Ch R = 1 ,54405   ,174.2,213.5,246.7
XS GIS Cut Line= 4
2204255.53722841406338.4672108552203998.19412966406218.654036033
 2203683.0884473406264.5891762862202967.53166945406247.724201724
#Sta/Elev= 30
       0  2063.5    25.8 2067.67    69.4 2065.08   131.7 2053.68   215.5 2047.35
   314.2  2045.3   378.9 2039.46   392.1 2033.64   404.3  2030.3     488  2032.4
   552.7 2037.87   572.9 2035.72   677.2 2040.25   701.2 2038.71   713.2 2034.16
823.07922031.149   945.3 2030.03953.27922031.037   969.3 2033.92   993.3 2048.07
  1005.3 2049.11  1017.3 2054.91  1057.3  2085.6  1093.5 2124.03  1140.1 2164.85
  1153.4 2173.56  1165.4 2190.73  1189.4  2212.5  1245.6 2260.24  1318.1 2312.38
#Mann= 6 ,-1,0
       0      .1       0   392.1     .04       0     488      .1       0
823.0792    .035       0953.2792    .025       0   993.3      .1       0
Bank Sta=823.0792,953.2792
XS Rating Curve= 0 ,0
Exp/Cntr(USF)=0,0
Exp/Cntr=0.3,0.1

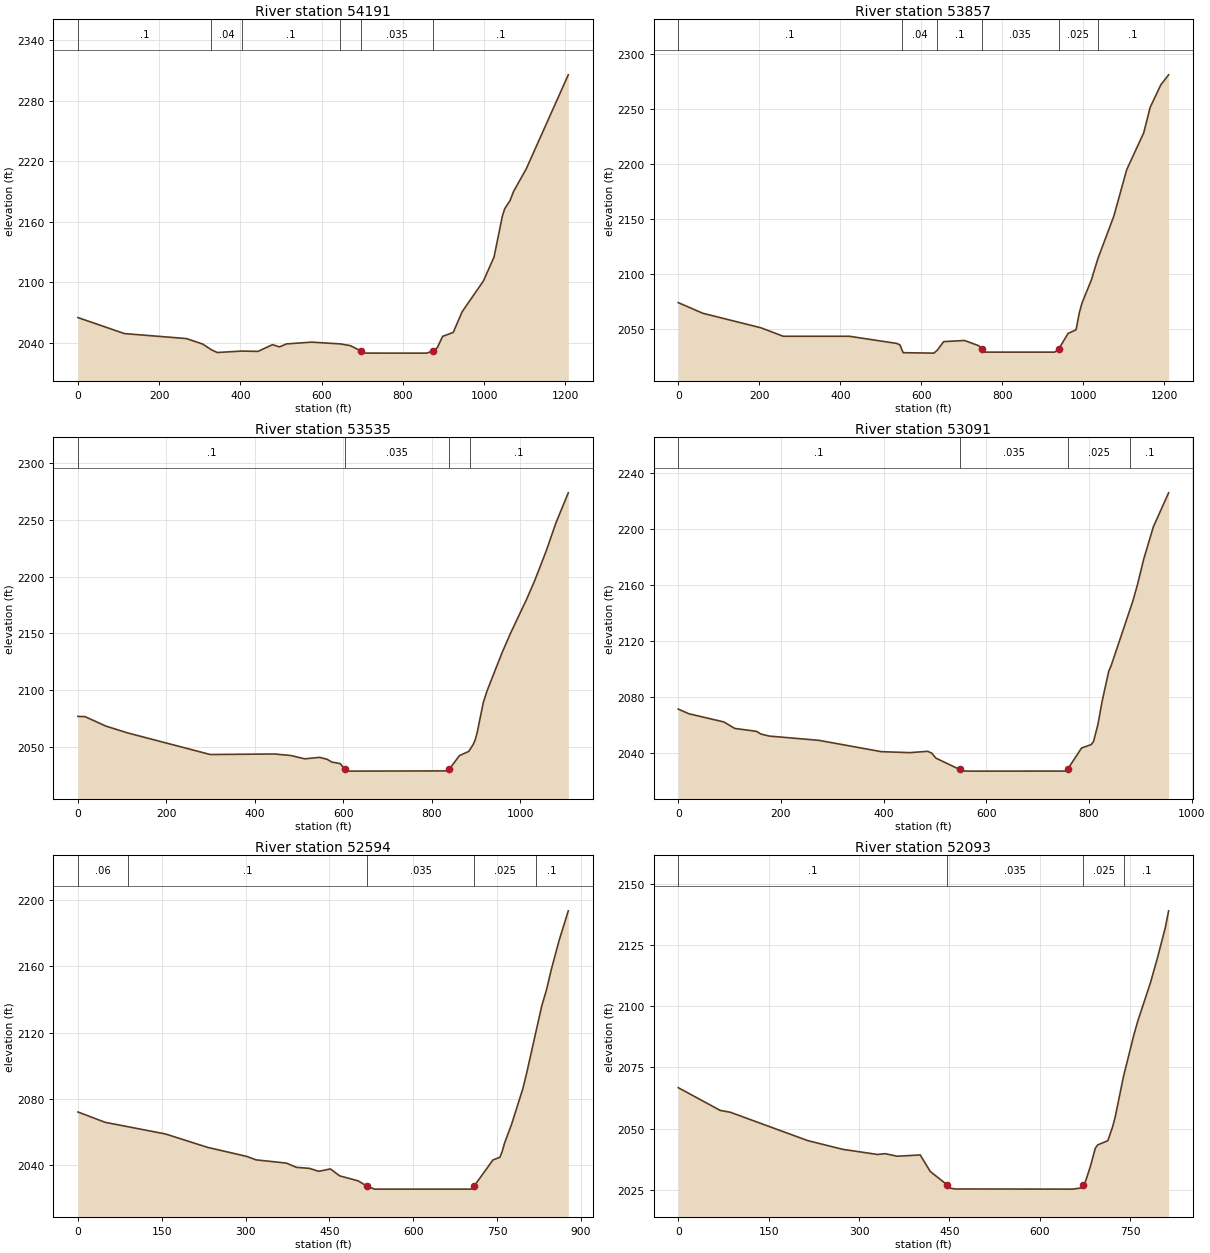
Type RM Length L Ch R = 1 ,54191   ,299.2,333.7,378.1
XS GIS Cut Line= 3
2204210.99007956406192.3122929092203726.45517528 406177.45070745
2203064.77920224405888.146494131
#Sta/Elev= 30
       0    2065   114.5 2049.12   266.9 2044.18     307 2038.77     328 2033.18
     343 2030.35     403  2031.8     443 2031.47     479 2038.13     496 2035.94
   513.4 2038.89   575.3 2040.64   645.2 2038.92   670.6 2037.18   696.3 2031.91
   705.5 2029.78   858.3 2029.75   874.8 2032.02   884.5 2035.17   897.6 2046.37
   923.8  2050.3   945.6 2070.76     998 2101.27  1024.2 2125.05  1044.6 2165.45
  1050.4 2172.89  1063.5 2180.92  1072.2 2189.99  1103.3 2212.28  1206.9 2305.59
#Mann= 6 ,-1,0
       0      .1       0     328     .04       0     403      .1       0
   645.2    .025       0   696.3    .035       0   874.8      .1       0
Bank Sta=696.3,874.8
XS Rating Curve= 0 ,0
Exp/Cntr(USF)=0,0
Exp/Cntr=0.3,0.1

Type RM Length L Ch R = 1 ,53857   ,296.3,322,356.8
XS GIS Cut Line= 4
2204276.97065193406158.5518474152203960.05547061405860.651576975
2203690.67756649405846.3903938162203324.64053206405497.783694366
#Sta/Elev= 30
       0 2074.23    60.4  2064.6   204.2 2051.38     259 2043.72   422.5  2043.7
     539 2037.23     547 2035.93   552.3 2031.23     555 2028.81   631.1 2028.41
   639.8 2031.28   655.1 2038.85   706.5  2039.9   741.3 2035.19   749.8 2031.79
   758.7 2029.31   929.1 2029.31   938.5 2031.83     962 2046.24   981.8 2049.61
   989.9 2065.12   996.5 2073.89  1019.7 2094.97  1035.5 2113.97  1075.1 2152.79
  1106.7 2194.82  1148.7 2228.24  1164.7 2251.45  1191.1 2271.93  1210.2 2280.93
#Mann= 6 ,-1,0
       0      .1       0   552.3     .04       0   639.8      .1       0
   749.8    .035       0   938.5    .025       0  1035.5      .1       0
Bank Sta=749.8,938.5
XS Rating Curve= 0 ,0
Exp/Cntr(USF)=0,0
Exp/Cntr=0.3,0.1

Type RM Length L Ch R = 1 ,53535   ,421.8,443.9,471.9
XS GIS Cut Line= 3
 2204348.0628132 406087.354862322203969.92901817 405750.65538285
 2203655.5973861405237.444564161
#Sta/Elev= 30
       0 2076.58    15.9 2076.39    63.4 2067.98   112.3    2062   298.9 2042.94
   444.4 2043.38   480.3  2042.1   512.7 2039.13   546.5 2040.42   563.3 2038.67
   573.7 2036.27   592.5 2034.94603.52592029.888   610.5 2028.27   831.7 2028.47
     839 2029.81     862 2041.94   883.3 2045.71   892.7  2051.5   897.4  2055.4
   902.1 2062.05   916.1 2088.94   924.6 2099.19   958.3 2132.65   976.8 2149.33
  1013.9 2179.94  1032.3 2196.49  1058.5  2222.9  1080.3 2247.53  1108.1 2273.92
#Mann= 4 ,-1,0
       0      .1       0603.5259    .035       0     839    .025       0
  886.31      .1       0
Bank Sta=603.5259,839
XS Rating Curve= 0 ,0
Exp/Cntr=0.3,0.1

Type RM Length L Ch R = 1 ,53091   ,490.3,497.8,510.2
XS GIS Cut Line= 2
2204467.94648785405956.6551814612204139.64148785405059.746539855
#Sta/Elev= 30
       0 2071.28    20.7 2067.94    88.9 2062.09   110.2 2057.45   152.2  2055.4
   161.3 2053.43   177.1 2052.01   273.8 2048.96   395.6 2040.87   451.5 2040.17
   485.8 2041.12   493.6 2039.85   502.1  2036.2   548.2 2028.14   553.2 2027.11
   569.5 2026.97   753.4    2027   758.7 2028.47   785.6 2043.49   804.5 2045.95
   808.8 2048.11   817.3 2060.04   825.7 2077.04   838.6 2098.46   842.8  2101.9
   885.4 2148.37   894.3 2159.95   906.8  2178.6   925.5 2201.55   955.1 2225.71
#Mann= 4 ,-1,0
       0      .1       0   548.2    .035       0   758.7    .025       0
     880      .1       0
Bank Sta=548.2,758.7
XS Rating Curve= 0 ,0
Exp/Cntr=0.3,0.1

Type RM Length L Ch R = 1 ,52594   ,500.7,500.4,501
XS GIS Cut Line= 2
2204895.61264161405816.0370531392204657.43664161404971.489002264
#Sta/Elev= 30
       0  2072.2    48.7 2065.98   156.7 2058.96     232  2050.9   302.2 2045.44
   318.8 2043.37   372.9 2041.43   390.9 2038.87   414.4 2038.24     431 2036.48
   451.8 2037.91   468.4 2033.74   501.7  2030.7   517.3 2027.53   530.8 2025.75
   701.2 2025.75   705.3 2025.87   709.5 2027.81   742.7 2043.33   755.2 2044.95
   759.4  2048.6   763.5 2053.53     776 2064.75   796.1 2086.13   802.6 2095.02
     830    2136   838.5 2145.75   846.6  2157.3   860.9 2175.28   877.5 2193.31
#Mann= 5 ,-1,0
       0     .06       0      90      .1       0   517.3    .035       0
   709.5    .025       0     820      .1       0
Bank Sta=517.3,709.5
XS Rating Curve= 0 ,0
Exp/Cntr=0.3,0.1

Type RM Length L Ch R = 1 ,52093   ,513.5,503.1,494.5
XS GIS Cut Line= 2
2205363.72694912405644.2132577742205147.23448785404859.897258906
#Sta/Elev= 30
       0 2066.73    69.5 2057.46    86.7 2056.67   214.8 2045.12   272.9 2041.56
   330.6 2039.46   343.4 2039.78   363.1 2038.74   401.5 2039.26   418.1 2032.52
   446.3 2027.03   451.3 2025.71   459.6 2025.38   654.6 2025.31   667.1 2025.75
     672 2027.19   675.4 2028.24   683.7 2034.49     692 2042.02   696.1  2043.4
   712.7 2045.06   720.8 2050.82   725.2 2055.02   738.6 2071.13   755.8 2088.13
   762.5 2093.95   783.3 2109.42   795.1 2119.72   808.2 2132.12   813.6 2138.92
#Mann= 4 ,-1,0
       0      .1       0   446.3    .035       0     672    .025       0
     740      .1       0
Bank Sta=446.3,672
XS Rating Curve= 0 ,0
Exp/Cntr=0.3,0.1

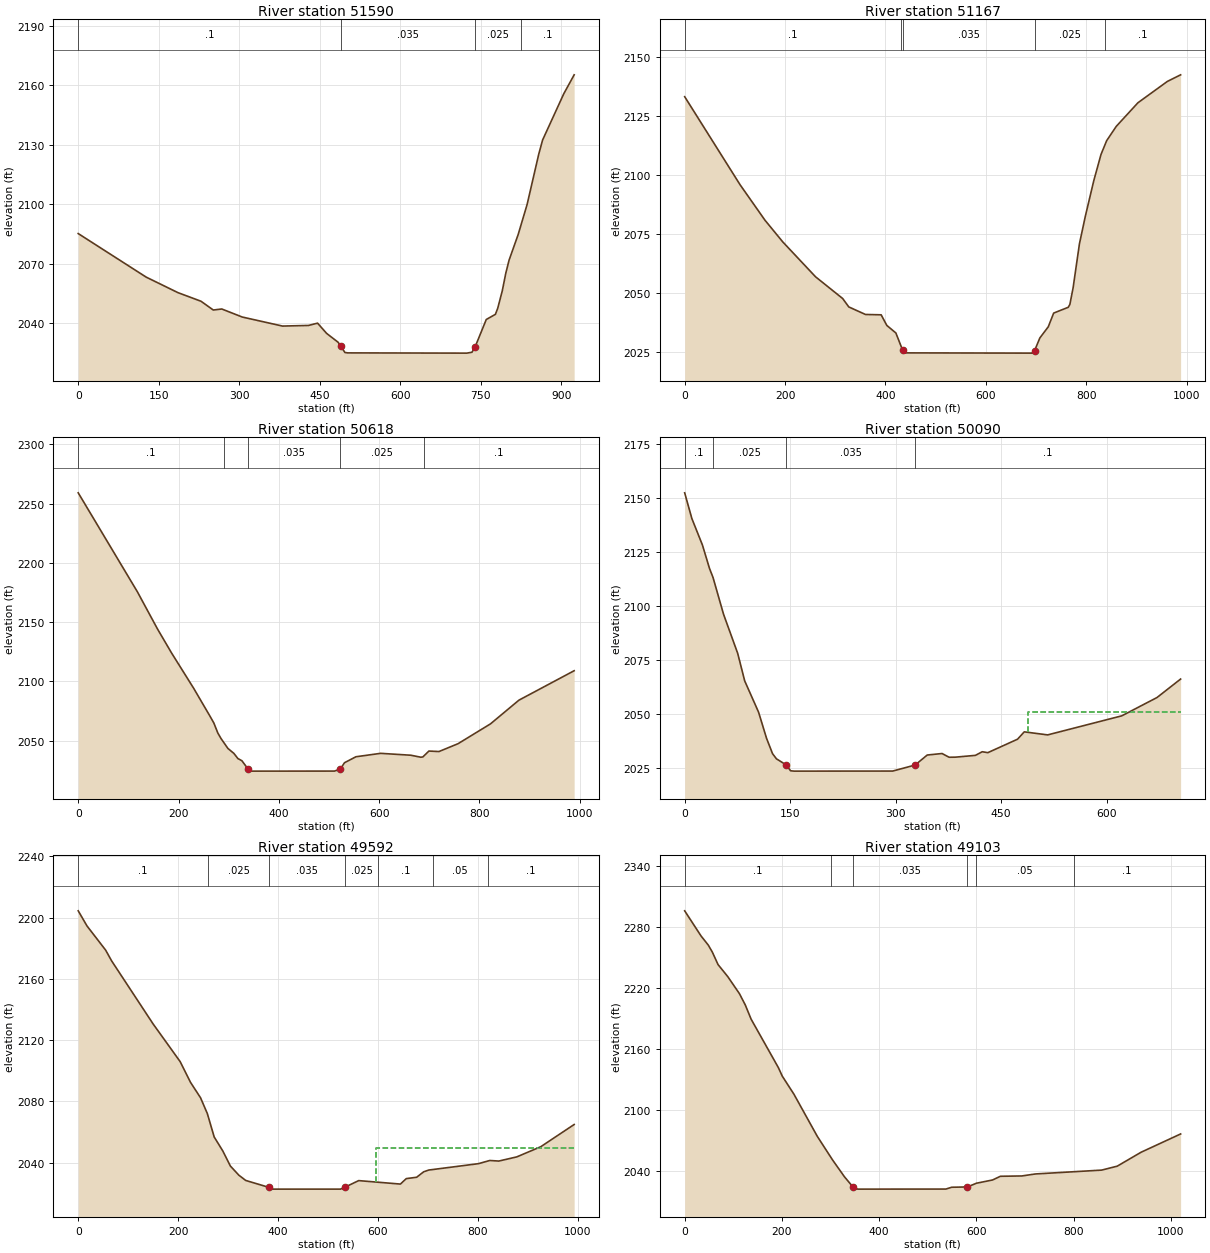
Type RM Length L Ch R = 1 ,51590   ,472.7,423.4,367.8
XS GIS Cut Line= 3
2205956.50953985405475.9846936142205808.07524213 405269.55567712
2205583.14492369404639.080950256
#Sta/Elev= 30
       0 2085.22   126.6 2063.25   185.7 2055.43   228.7 2051.08   251.6 2046.65
   267.4 2047.17   305.6 2043.11   380.5 2038.56   428.8 2038.87   445.8 2040.03
   462.8 2034.83     484 2030.41   489.2 2028.35   496.7 2025.25   501.8 2025.03
   723.8 2024.91   733.4 2025.36   738.8 2027.75     760 2041.87     777 2044.47
   781.3 2047.48   789.8 2056.29   796.4 2065.23   802.5 2071.81   819.5 2084.79
   836.1 2099.91   857.7  2125.2   864.9 2132.39   904.4 2155.75   923.7 2165.29
#Mann= 4 ,-1,0
       0      .1       0   489.2    .035       0   738.8    .025       0
  824.26      .1       0
Bank Sta=489.2,738.8
XS Rating Curve= 0 ,0
Exp/Cntr=0.3,0.1

Type RM Length L Ch R = 1 ,51167   ,677.2,548.7,436.9
XS GIS Cut Line= 3
 2206416.7245896405163.9380531392205930.94862822404582.910284234
2205711.18351215404513.326514417
#Sta/Elev= 30
       0 2133.04   110.3 2095.82     160 2080.79   195.4 2071.63   260.8 2056.85
   314.7 2047.69   326.9 2044.13   360.1 2040.94   391.4 2040.79   402.7  2036.3
   420.7 2033.11     434 2025.91   441.6 2024.69   691.8 2024.59     697 2025.62
   707.5 2031.01   724.3 2035.73     735 2041.52   764.1 2043.98   767.3 2045.19
   773.7 2052.17   786.4 2070.88     798 2082.39   814.8 2097.41   829.3 2108.61
   840.6 2114.45   859.7 2120.49   902.9 2130.48   961.6 2139.51   987.9 2142.29
#Mann= 5 ,-1,0
       0      .1       0     430    .025       0     434    .035       0
     697    .025       0  837.35      .1       0
Bank Sta=434,697
XS Rating Curve= 0 ,0
Exp/Cntr=0.3,0.1

Type RM Length L Ch R = 1 ,50618   ,599.4,527.8,469.4
XS GIS Cut Line= 3
     2206733.912      404228.5192206017.68278311404274.522177955
2205760.88551215404361.534539855
#Sta/Elev= 30
       0 2259.04     118 2175.51   158.1 2144.13   186.1 2123.92   230.2  2094.1
   262.3 2070.87   270.3 2064.92   278.3 2056.43   284.7 2051.71   298.4 2043.37
   310.4 2039.14   318.4 2034.79   326.4 2032.96   338.4 2026.07   342.4 2024.25
   346.4 2024.19   510.8 2024.22   522.8 2025.92   530.8 2031.25   553.7 2036.31
     603  2039.2   663.1 2037.61   683.1 2035.93   687.2 2036.18   699.2 2041.13
   719.3 2040.72   757.3 2047.33   821.9 2064.04   878.7 2084.07   988.8 2108.91
#Mann= 5 ,-1,0
       0      .1       0     290    .025       0   338.4    .035       0
   522.8    .025       0     690      .1       0
Bank Sta=338.4,522.8
XS Rating Curve= 0 ,0
Exp/Cntr=0.3,0.1

Type RM Length L Ch R = 1 ,50090   ,541.1,497.9,451.4
XS GIS Cut Line= 2
 2206276.3511515403634.2114115332205713.36028208404059.183667044
#Sta/Elev= 30
       0 2152.37    10.2 2140.48    25.3 2128.14    35.3 2117.34    40.3 2113.17
    55.3 2096.09    75.4    2078    85.4  2065.2   105.1 2050.74   116.5 2038.57
     125 2031.48   130.5 2029.12   144.4 2026.28   150.6 2023.58   155.6 2023.41
   295.9 2023.44   327.8 2026.24     345 2030.87   366.1 2031.57   376.1 2029.84
   384.9 2029.88   413.5 2030.71   423.2 2032.39   431.2 2031.97   473.5 2038.21
     483 2041.61   516.3  2040.2   621.7 2049.03   671.8 2057.51   705.4 2066.08
#Mann= 4 ,-1,0
       0      .1       0      40    .025       0   144.4    .035       0
   327.8      .1       0
#XS Ineff= 2 , 0
                          488.56          2050.6
Permanent Ineff=
       F       F
Bank Sta=144.4,327.8
XS Rating Curve= 0 ,0
Exp/Cntr=0.3,0.1

Type RM Length L Ch R = 1 ,49592   ,536.9,489,438.6
XS GIS Cut Line= 2
     2205947.474      403032.6742205483.31620464403910.558462409
#Sta/Elev= 30
       0 2204.47    17.6 2194.59    54.9 2178.82      67 2171.74   149.9 2130.63
   204.1    2106   224.8 2092.49   244.9  2082.4   258.5 2072.11   272.3 2056.76
   289.5 2047.65   304.7 2037.79   321.8 2031.78   335.4 2028.39   381.7 2023.88
   390.5 2022.72   525.4 2022.73   534.5 2024.06   561.6 2028.28   645.1 2026.02
   656.9 2029.59   677.6 2030.47   691.7 2034.03   701.9 2035.18   801.4 2039.35
   824.1 2041.42   842.2 2041.05   878.4  2043.8   926.3 2050.44     993 2064.92
#Mann= 7 ,-1,0
       0      .1       0     260    .025       0   381.7    .035       0
   534.5    .025       0     600      .1       0     710     .05       0
     820      .1       0
#XS Ineff= 2 , 0
                          596.57         2049.39
Permanent Ineff=
       F       F
Bank Sta=381.7,534.5
XS Rating Curve= 0 ,0
Exp/Cntr=0.3,0.1

Type RM Length L Ch R = 1 ,49103   ,526.1,510.8,497.9
XS GIS Cut Line= 2
     2205287.177      402864.6972205239.43169248403883.395975694
#Sta/Elev= 30
       0  2295.9    33.9    2271    48.5 2262.21    56.9 2255.28    68.6 2243.01
    88.6 2231.17   112.6 2214.39   124.6 2203.31   136.6 2189.31   192.7 2141.59
   200.7 2133.23   224.7 2115.41   272.8 2073.91     304 2050.81   328.8 2034.03
   346.1 2024.14   348.9 2022.51   356.9 2022.03   537.1 2022.09   549.1 2023.88
   581.3 2024.17     600 2027.84   633.2 2031.04   649.2 2034.67   693.2 2034.99
   721.3 2036.96   857.4 2040.74   889.5 2044.64   938.4  2058.3  1019.8 2076.32
#Mann= 6 ,-1,0
       0      .1       0     300    .025       0   346.1    .035       0
   581.3      .1       0     600     .05       0     800      .1       0
Bank Sta=346.1,581.3
XS Rating Curve= 0 ,0
Exp/Cntr=0.3,0.1

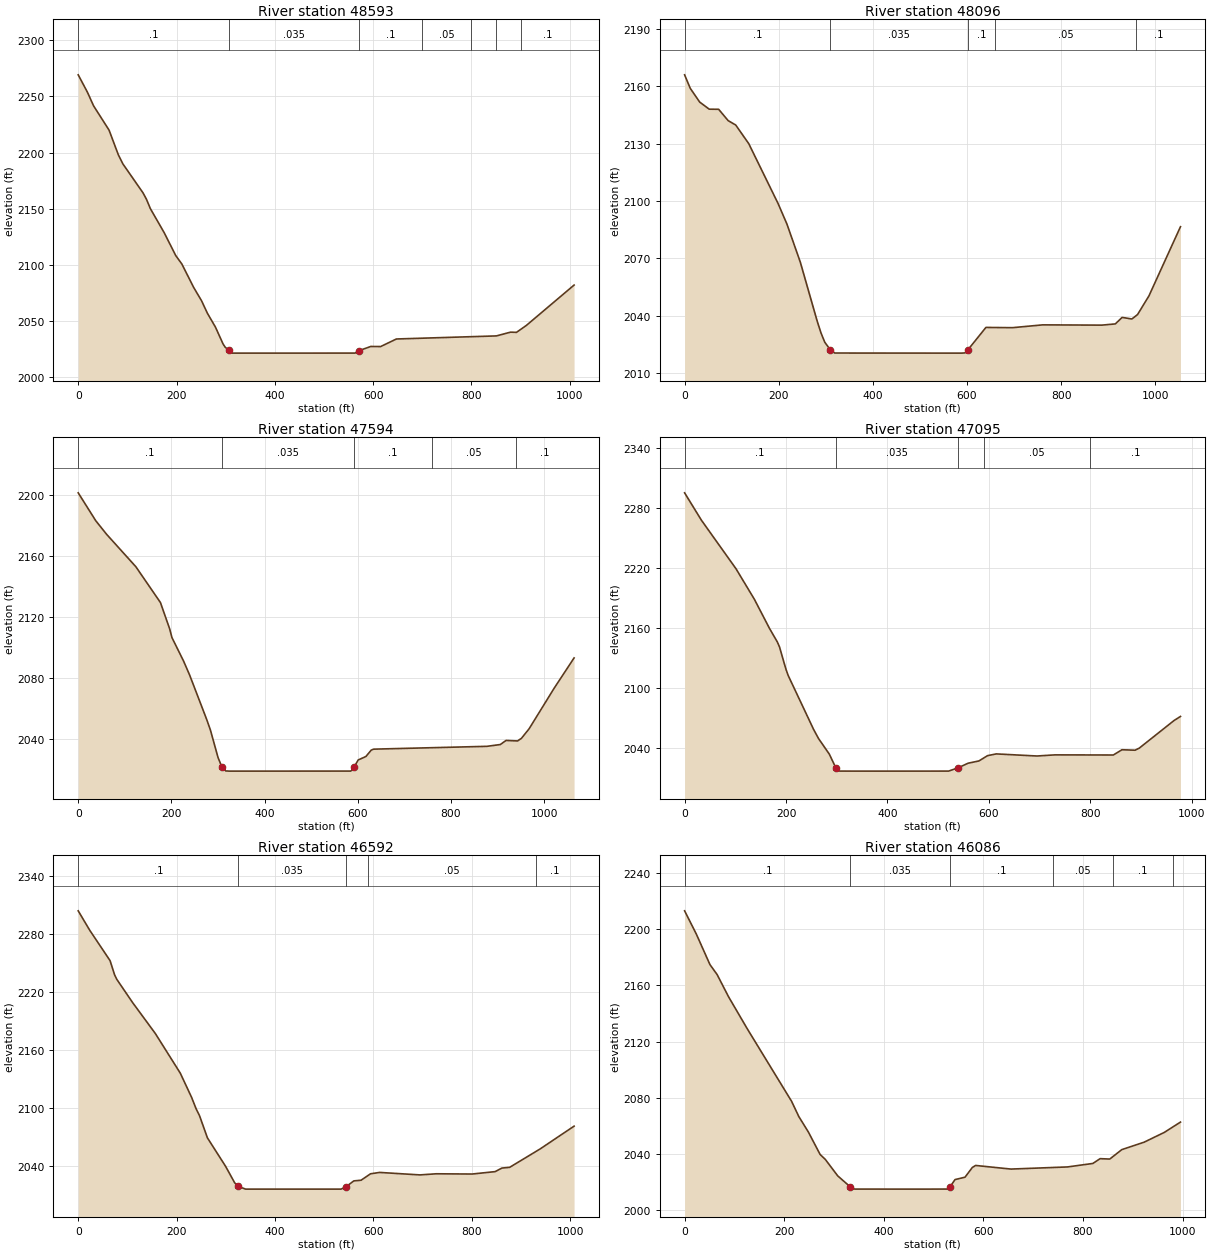
Type RM Length L Ch R = 1 ,48593   ,508.8,496.6,486.7
XS GIS Cut Line= 2
     2204735.406      402858.4882204779.98928208403866.290565292
#Sta/Elev= 30
       0 2269.19    18.7 2253.77    31.3 2241.56    62.8 2219.94    81.6 2198.02
    90.8 2189.95   131.9 2164.06   138.8 2158.44   146.8 2150.05   174.9 2128.64
   198.4 2108.29   210.9 2100.71   234.9 2079.88   250.9 2068.04   262.9 2056.83
     279 2044.74   294.7 2029.56     299 2026.69   306.2 2023.96     311 2021.38
   563.2 2021.41   571.7 2023.66   595.3 2027.32   615.3 2027.23   647.3 2033.97
   850.7 2036.71   879.6 2040.06   891.6 2039.86   911.6 2046.01  1008.8 2081.98
#Mann= 7 ,-1,0
       0      .1       0   306.2    .035       0   571.7      .1       0
     700     .05       0     800     .06       0     850     .05       0
     900      .1       0
Bank Sta=306.2,571.7
XS Rating Curve= 0 ,0
Exp/Cntr=0.3,0.1

Type RM Length L Ch R = 1 ,48096   ,522.2,501.7,480.9
XS GIS Cut Line= 2
     2204207.785      402905.2872204331.33653872403951.714642738
#Sta/Elev= 30
       0 2166.02      12 2158.96    32.1 2151.75    52.3 2148.05    72.4 2147.98
    92.5 2142.06   108.6 2139.76   136.4 2129.97   198.4 2098.79   217.4 2087.96
   246.1 2067.84   281.8 2037.08   289.9 2030.91   297.9 2026.06     310 2022.01
     310    2022   319.1 2020.43   587.5 2020.38     596 2020.49   601.9 2022.07
   640.3 2033.83   696.7  2033.7   761.1 2035.17   886.5 2035.03   915.3 2035.67
   929.7 2039.07   950.4 2038.25   962.5 2040.56   986.7 2050.33  1053.7 2086.53
#Mann= 5 ,-1,0
       0      .1       0     310    .035       0   601.9      .1       0
     660     .05       0     960      .1       0
Bank Sta=310,601.9
XS Rating Curve= 0 ,0
Exp/Cntr=0.3,0.1

Type RM Length L Ch R = 1 ,47594   ,519,499.4,484.5
XS GIS Cut Line= 2
     2203661.767      403021.8652203917.91351329404054.842488979
#Sta/Elev= 30
       0 2201.23    37.7 2182.91    61.1 2173.95   123.6 2152.79   176.5 2129.23
   196.3 2111.95   201.2 2106.24     226 2090.91   239.2 2081.63   275.5  2052.7
   283.7 2045.64   300.1 2027.53   308.5 2021.19   316.6 2018.73   324.6 2018.59
   584.5 2018.62   588.6 2019.26   591.7 2021.07     601 2025.92   617.5  2028.2
   628.9 2032.36   633.9 2033.01   877.1 2034.86   905.9 2036.04   918.3 2038.72
     943  2038.4   951.3  2040.1   967.8 2046.39  1021.3 2072.89  1064.3 2092.88
#Mann= 5 ,-1,0
       0      .1       0   308.5    .035       0   591.7      .1       0
     760     .05       0     940      .1       0
Bank Sta=308.5,591.7
XS Rating Curve= 0 ,0
Exp/Cntr=0.3,0.1

Type RM Length L Ch R = 1 ,47095   ,529.1,502.9,486
XS GIS Cut Line= 2
     2203139.469      403202.0982203484.99410288404116.986334088
#Sta/Elev= 30
       0 2295.05    33.2 2267.63   101.6 2218.91   137.9 2188.26   167.4 2159.39
   182.9 2145.81   187.2  2140.8     200 2118.33   204.3 2112.25   254.3  2058.4
   264.1 2049.19   285.4 2033.57   298.3 2019.78   302.6 2016.85   307.1 2016.56
   383.8 2016.53   520.7 2016.56   539.9 2019.94   559.1 2024.45   580.5 2026.72
   597.6 2032.03   614.7 2033.76     695 2031.66   730.2 2032.79   845.6 2032.66
   862.6 2037.93   888.4 2037.46   896.8 2039.57   965.3 2067.17     978 2071.25
#Mann= 5 ,-1,0
       0      .1       0   298.3    .035       0   539.9      .1       0
     590     .05       0     800      .1       0
Bank Sta=298.3,539.9
XS Rating Curve= 0 ,0
Exp/Cntr=0.3,0.1

Type RM Length L Ch R = 1 ,46592   ,517.5,505.9,497.4
XS GIS Cut Line= 2
      2202620.14      403444.9132203119.30435953404320.659154891
#Sta/Elev= 30
       0 2304.19    23.3 2284.15    64.8 2252.48      74 2237.75    78.6    2233
   110.8 2208.87   156.8 2176.91   207.5 2135.81   230.5 2110.69   239.7 2098.79
   246.6 2091.73   262.7 2068.65   299.6 2039.17     318 2022.11   325.7 2018.24
   340.4  2015.5   534.4 2015.51   543.6 2017.72   560.3 2024.03     575 2024.73
   594.2 2031.39   612.7 2032.82   694.7 2030.25   727.8 2031.41   800.8 2031.16
   847.5 2033.66   861.3 2037.34   877.1 2038.12   938.7 2057.09    1008 2080.83
#Mann= 5 ,-1,0
       0      .1       0   325.7    .035       0   543.6      .1       0
     590     .05       0     930      .1       0
Bank Sta=325.7,543.6
XS Rating Curve= 0 ,0
Exp/Cntr=0.3,0.1

Type RM Length L Ch R = 1 ,46086   ,480.4,493,505.9
XS GIS Cut Line= 2
     2202162.858      403735.744 2202723.9862312 404558.54530865
#Sta/Elev= 30
       0 2213.21    23.6 2196.61    50.9 2174.89    65.3 2167.78    88.3 2151.92
   125.8 2129.15   214.8 2077.45   229.4 2066.53   248.7 2055.45   272.1 2039.54
   282.6 2035.98   307.6 2024.22     333 2016.32   341.6 2014.82   479.8 2014.79
   528.8 2014.84   533.3 2016.51   543.1 2021.58   563.2 2023.31   577.9 2030.24
   584.5 2031.67   655.4 2029.09   769.1 2030.61     820  2033.1   834.5 2036.51
   853.9 2036.23   878.1 2042.96   923.1 2048.29   963.4 2055.23   995.9 2062.58
#Mann= 6 ,-1,0
       0      .1       0     333    .035       0   533.3      .1       0
     740     .05       0     860      .1       0     980     .05       0
Bank Sta=333,533.3
XS Rating Curve= 0 ,0
Exp/Cntr=0.3,0.1