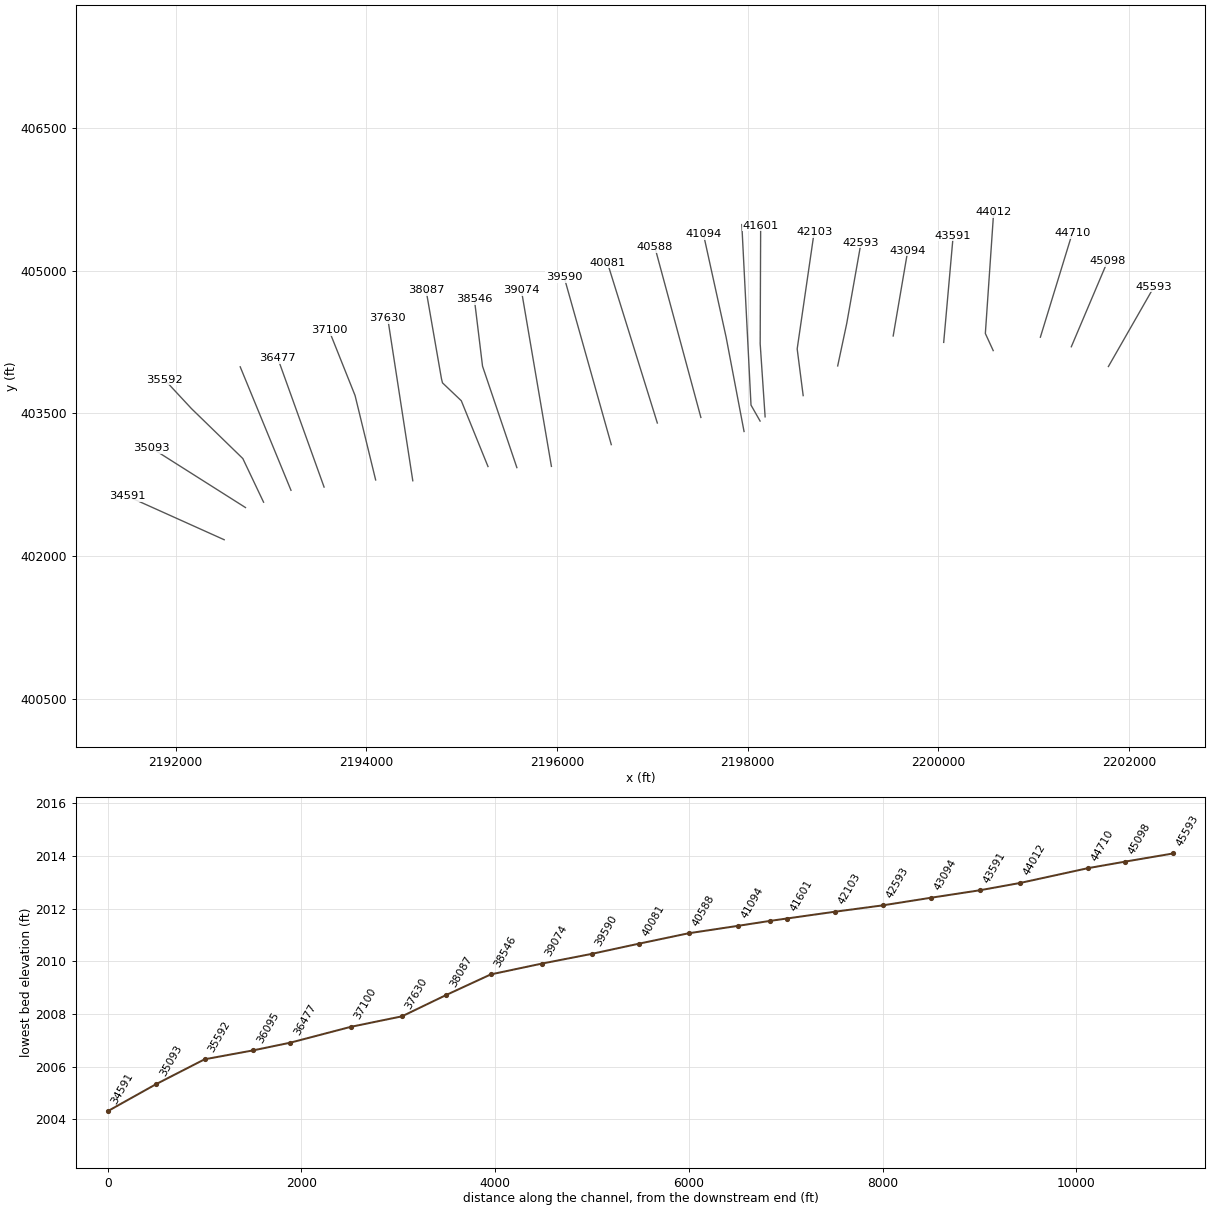
HEC-RAS study GRNBRRRV.prj: GRNBRRRV

--- GRNBRRRV.g01 (geometry) --- (continued)

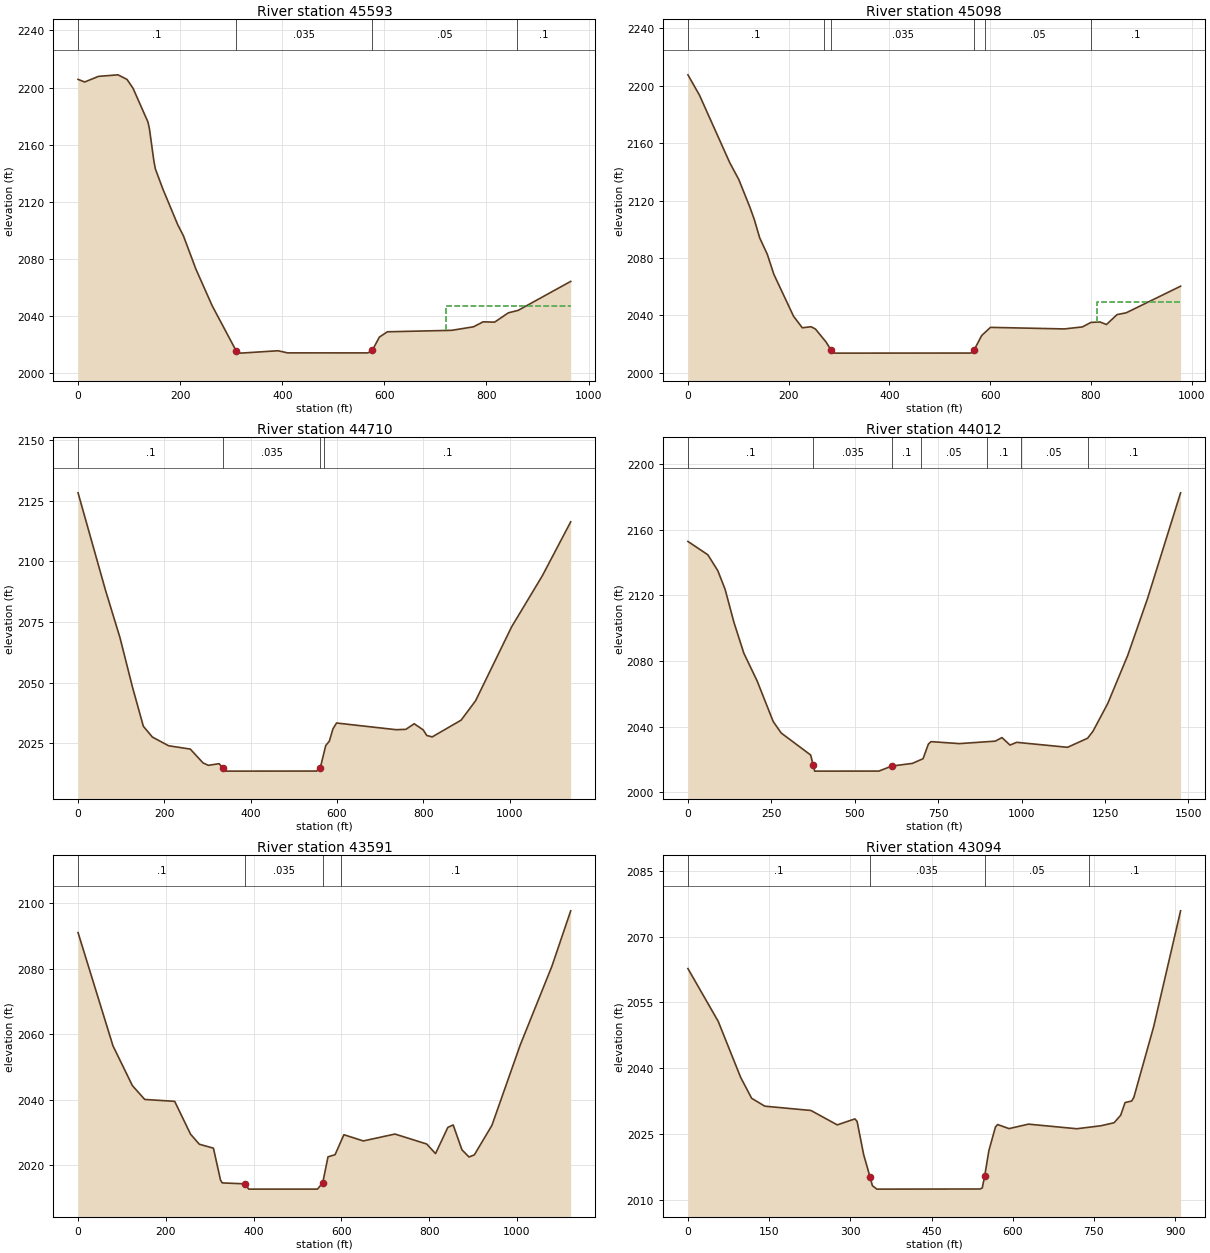
Type RM Length L Ch R = 1 ,45593   ,474.1,495.5,511.5
XS GIS Cut Line= 2
     2201785.745      403992.8182202264.83110288404830.476641606
#Sta/Elev= 30
       0 2205.76      13 2203.94    40.2 2207.87    78.3 2208.94    95.9 2205.73
   107.6 2199.62   136.9 2175.95   139.8 2171.25   148.6  2148.5   151.5 2143.03
     166 2129.11   195.5 2103.81   206.3 2096.33   230.8 2072.97   262.7 2047.28
   309.8 2015.66   318.6 2014.09   391.6 2015.75   410.5 2014.27   567.8 2014.25
   576.4 2016.03   590.2 2025.31   605.9 2029.03     732 2030.05   774.6 2032.53
   793.5 2036.01     816 2035.79   842.8 2042.29   862.1 2044.04     965 2064.32
#Mann= 4 ,-1,0
       0      .1       0   309.8    .035       0   576.4     .05       0
     860      .1       0
#XS Ineff= 2 , 0
                          720.56         2047.42
Permanent Ineff=
       F       F
Bank Sta=309.8,576.4
XS Rating Curve= 0 ,0
Exp/Cntr=0.3,0.1

Type RM Length L Ch R = 1 ,45098   ,371.2,387.2,400.6
XS GIS Cut Line= 2
     2201396.576      404200.0562201778.15810288405100.601334088
#Sta/Elev= 30
       0  2207.7    22.9 2193.57    82.9  2146.6   101.1 2134.67   122.9  2115.6
   131.8 2106.89   142.5  2094.1   157.6 2082.66   170.6 2068.72   209.7 2039.48
   227.1 2031.43   244.5 2032.18   253.2 2030.57   274.3  2021.5   283.92016.026
   287.9 2013.88   292.3 2013.78   560.7 2013.84     566 2014.33   568.3 2016.03
   583.3 2026.09   600.7 2031.73   747.4 2030.64   783.2 2032.05     800 2035.16
   817.9  2035.5     831 2033.72   851.9  2040.6   870.1 2041.87   978.1 2060.41
#Mann= 6 ,-1,0
       0      .1       0     270    .025       0   283.9    .035       0
   568.3    .025       0     590     .05       0     800      .1       0
#XS Ineff= 2 , 0
                          811.83         2049.31
Permanent Ineff=
       F       F
Bank Sta=283.9,568.3
XS Rating Curve= 0 ,0
Exp/Cntr=0.3,0.1

Type RM Length L Ch R = 1 ,44710   ,671.6,698.1,730.6
XS GIS Cut Line= 2
2201071.90381498404300.5095906352201406.61477108405391.958360516
#Sta/Elev= 30
       0  2128.3    63.5 2088.19    97.2 2068.55   125.6 2048.54   151.3 2032.03
   172.2 2027.59   209.9 2023.99   260.1 2022.62   289.4 2016.95   301.9 2015.92
     327  2016.6   335.4 2014.77   343.8 2013.53     553 2013.56   561.3 2014.87
   573.9 2024.06   582.3  2025.9   590.6 2030.94     599 2033.37   737.1 2030.62
   759.6 2030.76     779 2033.06   799.8 2030.54   808.2 2028.22   820.7 2027.65
   887.7 2034.56   921.2 2042.56  1004.8 2073.07    1076 2094.14  1141.6 2116.34
#Mann= 4 ,-1,0
       0      .1       0   335.4    .035       0   561.3    .025       0
     570      .1       0
Bank Sta=335.4,561.3
XS Rating Curve= 0 ,0
Exp/Cntr(USF)=0,0
Exp/Cntr=0.3,0.1

Type RM Length L Ch R = 1 ,44012   ,430.9,420.9,418.9
XS GIS Cut Line= 3
2200577.11370597404159.833971406 2200494.6486878404339.316658009
2200581.96458939405615.098997914
#Sta/Elev= 30
       0 2152.79    59.7 2144.67    89.5 2135.02   111.5 2123.61   137.9 2103.56
   167.6 2084.73   207.4 2067.88   255.5 2043.19   279.5 2036.18   367.8 2022.79
   375.8  2016.4   379.8 2012.97   572.3    2013   611.1 2016.07   672.5 2017.67
   704.6 2020.53   720.6 2029.47   728.6 2030.93   813.3 2029.72   920.9 2031.22
   941.1 2033.38   965.2 2028.83   985.2  2030.5  1137.6 2027.47  1197.7    2033
  1213.8 2037.25  1257.9 2054.07    1318 2083.47  1377.2    2118  1476.3 2182.38
#Mann= 7 ,-1,0
       0      .1       0   375.8    .035       0   611.1      .1       0
  697.52     .05       0  897.52      .1       0  997.52     .05       0
 1197.52      .1       0
Bank Sta=375.8,611.1
XS Rating Curve= 0 ,0
Exp/Cntr(USF)=0,0
Exp/Cntr=0.3,0.1

Type RM Length L Ch R = 1 ,43591   ,509.4,497.8,488.4
XS GIS Cut Line= 2
     2200057.587      404245.8662200156.93869248405363.913823067
#Sta/Elev= 30
       0 2090.99    79.6 2056.42   123.8 2044.29   151.9 2040.06   220.2 2039.48
   256.3 2029.47   276.4 2026.39   308.5 2025.19   324.6 2015.44   328.6 2014.59
   380.8  2014.3   388.8 2012.69   545.5 2012.69   557.5 2014.62   569.5 2022.54
   585.6 2023.19   605.7  2029.3   649.9  2027.4   722.1  2029.5   794.4 2026.46
   814.5 2023.54   842.6 2031.53   854.7 2032.28   874.7 2024.69   890.8  2022.5
   902.9 2023.14     943 2032.16  1007.3 2056.62  1079.6  2080.7  1122.5 2097.63
#Mann= 4 ,-1,0
       0      .1       0   380.8    .035       0   557.5    .025       0
     600      .1       0
Bank Sta=380.8,557.5
XS Rating Curve= 0 ,0
Exp/Cntr=0.3,0.1

Type RM Length L Ch R = 1 ,43094   ,501.9,500.1,499.8
XS GIS Cut Line= 2
     2199527.545      404313.202     2199680.785      405210.207
#Sta/Elev= 30
       0 2062.74      56 2050.69    97.4 2037.92   117.7 2033.14     142 2031.34
   227.2 2030.36   275.9 2027.07   308.4 2028.44   312.5 2027.87   324.6 2020.29
   336.3 2015.22   340.8 2013.19     349 2012.41   539.7 2012.44   543.7 2012.69
   548.1 2015.38   555.9 2021.19   568.1 2026.61   572.1 2027.15   593.2 2026.22
     629 2027.24   718.2 2026.19   762.9 2026.87   787.2 2027.56   799.4 2029.28
   807.5 2032.17   819.7 2032.52   823.7 2033.36   860.3 2049.49     910 2075.92
#Mann= 4 ,-1,0
       0      .1       0   336.3    .035       0   548.1     .05       0
     740      .1       0
Bank Sta=336.3,548.1
XS Rating Curve= 0 ,0
Exp/Cntr=0.3,0.1

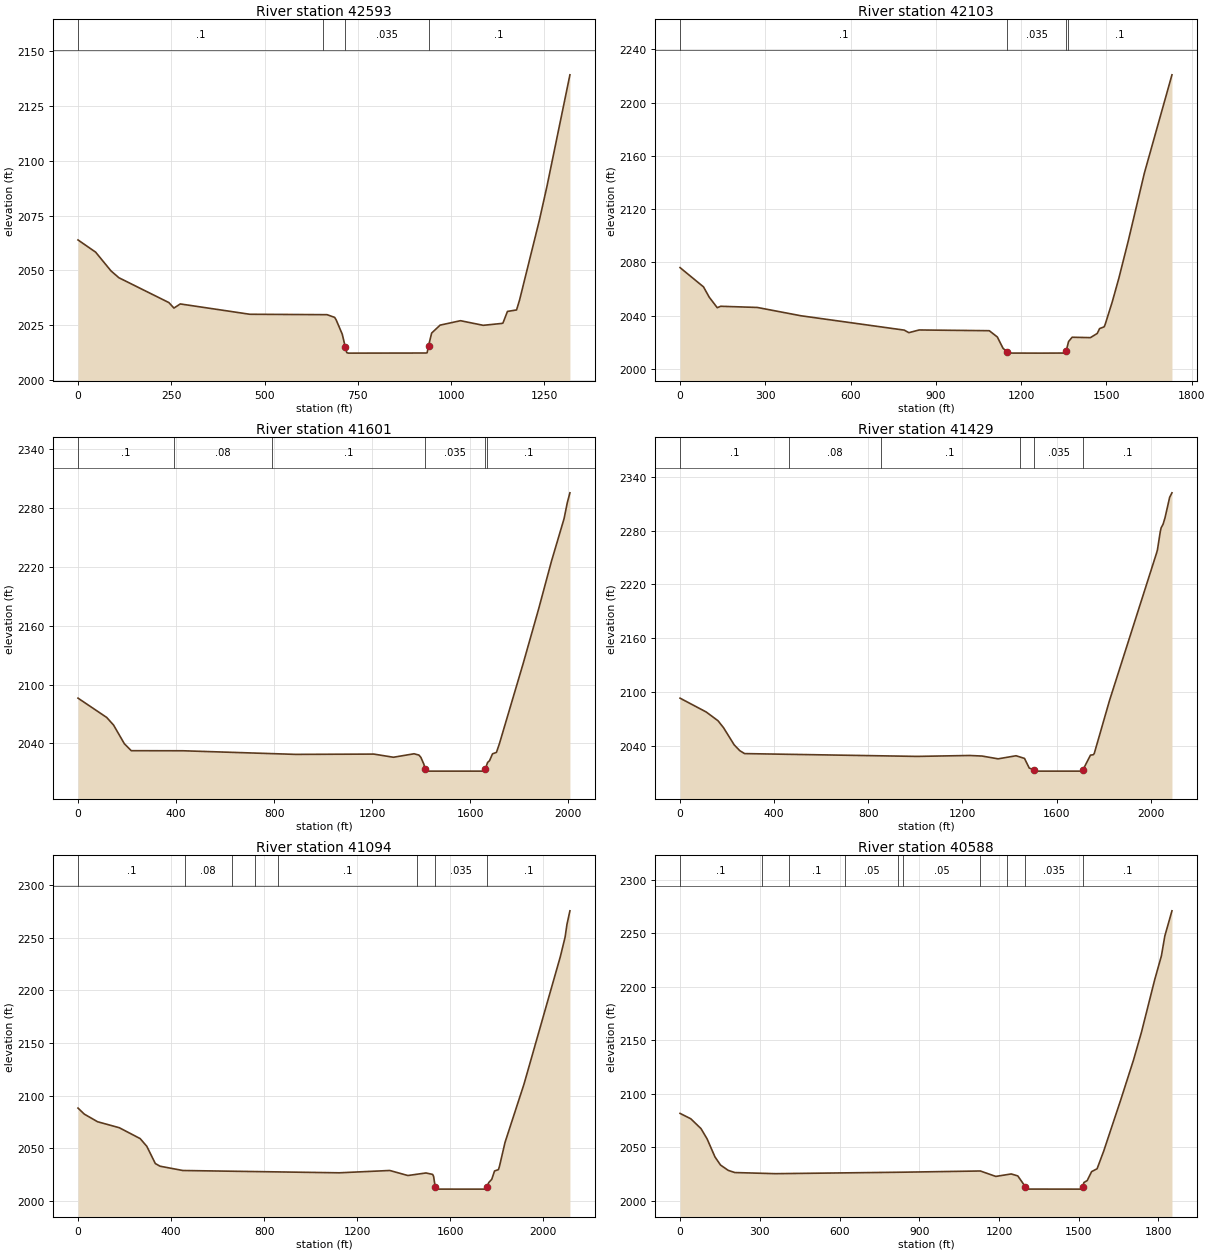
Type RM Length L Ch R = 1 ,42593   ,487,490.2,493.5
XS GIS Cut Line= 3
2198945.36064301403998.9764608682199040.40187856404445.581205657
     2199190.511      405293.965
#Sta/Elev= 30
       0 2063.84    47.2 2058.27    88.5 2049.68   109.6 2046.57   243.6 2035.21
   257.1 2032.71     274  2034.6   460.3 2029.88   667.4 2029.69   687.7 2028.46
   691.8 2027.31   708.1 2020.78   716.2 2014.97   720.2 2012.34   724.3 2012.12
   932.4 2012.17   935.5 2012.27   939.3 2015.49   947.7  2021.3   970.3 2024.91
  1024.9 2026.94  1085.8 2024.83  1134.6 2025.67  1138.6 2025.82  1150.8 2031.17
  1175.2 2031.86  1183.3 2036.41  1236.2 2072.76  1256.8 2088.47  1318.2  2139.3
#Mann= 4 ,-1,0
       0      .1       0  656.61     .05       0   716.2    .035       0
   939.3      .1       0
Bank Sta=716.2,939.3
XS Rating Curve= 0 ,0
Exp/Cntr=0.3,0.1

Type RM Length L Ch R = 1 ,42103   ,480.4,502.1,520.6
XS GIS Cut Line= 3
2198583.21697614403687.385808862  2198520.333551 404177.77503713
     2198698.196      405401.219
#Sta/Elev= 30
       0 2076.12    82.5 2061.66   102.6 2053.93   130.9 2046.01     143 2047.08
     272 2046.19   425.2 2039.95   788.9 2029.16     805 2027.25   841.4 2029.28
    1088 2028.72  1116.3 2024.01  1136.5 2015.471150.4862013.046  1156.7 2011.92
  1269.5 2011.88  1354.8 2011.941358.2782013.201  1366.9 2020.58  1379.5 2023.81
  1443.7 2023.52  1467.9 2026.67    1476 2030.31  1492.2 2031.65    1496 2033.63
  1520.7 2050.45  1543.9  2068.2  1577.1 2096.34  1633.7 2147.18  1730.7 2220.95
#Mann= 4 ,-1,0
       0      .1       01150.486    .035       01358.278    .025       0
  1364.4      .1       0
Bank Sta=1150.486,1358.278
XS Rating Curve= 0 ,0
Exp/Cntr=0.3,0.1

Type RM Length L Ch R = 1 ,41601   ,165.6,172.1,179.3
XS GIS Cut Line= 3
2198183.84457471403464.5360298662198132.10342992404232.057926051
     2198137.147      405468.842
#Sta/Elev= 30
       0  2086.1   117.1 2066.38     145 2058.62   189.1 2039.57   217.1 2032.47
   428.5 2032.39   886.4 2028.71  1206.4    2029  1286.4 2025.78  1370.4 2029.33
  1390.4 2027.99  1398.4 2025.58  1410.4 2018.72  1415.8 2013.67  1418.4 2011.75
  1422.4 2011.62  1654.4 2011.62  1658.4 2011.781661.3672014.005  1670.4 2020.49
  1678.4  2022.3  1690.4 2029.29  1706.4 2030.73  1718.2 2039.35  1814.6 2120.75
  1878.4 2177.04  1930.4 2225.45  1982.4 2269.45  1995.3 2285.49  2006.1 2295.62
#Mann= 6 ,-1,0
       0      .1       0     390     .08       0  789.26      .1       0
  1415.8    .035       01661.367    .025       0 1669.26      .1       0
Bank Sta=1415.8,1661.367
XS Rating Curve= 0 ,0
Exp/Cntr=0.3,0.1

Type RM Length L Ch R = 1 ,41429   ,315.5,335.2,356
XS GIS Cut Line= 3
 2198131.2188518403420.2398845832198035.83439335403587.807176456
2197939.45644002405482.899032954
#Sta/Elev= 30
       0 2092.99   111.3 2077.53   161.3 2067.79   184.8 2060.01   230.2 2040.82
   253.7 2034.41   274.3  2031.1  1007.2 2027.97  1231.5 2028.99  1283.6 2028.35
  1351.7 2025.25  1427.8 2028.69  1463.8 2025.74  1483.9 2014.96  1504.9 2012.89
  1511.9 2011.53  1708.1 2011.53    17122012.874  1744.2 2029.43  1756.2 2029.81
  1760.3 2031.32    1825 2090.39  2024.5 2254.62  2028.6  2258.4  2040.6 2278.67
  2044.6 2283.27  2052.6 2287.15  2060.6  2294.1  2080.6 2317.21  2090.4 2322.23
#Mann= 6 ,-1,0
       0      .1       0  462.81     .08       0  852.81      .1       0
 1442.81    .025       0  1504.9    .035       0    1712      .1       0
Bank Sta=1504.9,1712
XS Rating Curve= 0 ,0
Exp/Cntr(USF)=0,0
Exp/Cntr=0.3,0.1

Type RM Length L Ch R = 1 ,41094   ,500.2,506.3,512.2
XS GIS Cut Line= 3
2197962.87201368403310.6316060232197774.50824831404301.832595635
     2197536.955      405381.501
#Sta/Elev= 30
       0 2088.25      27 2082.53      84  2075.3   177.7 2069.59   267.2 2059.28
   295.7 2051.97   332.4  2035.6   352.7 2033.09   450.5 2029.01  1122.9 2026.83
    1340 2029.03  1417.8 2024.25  1495.7 2026.68  1524.3 2025.31  1528.4 2023.49
 1535.26 2013.63  1540.7 2011.35  1749.6 2011.341757.683 2013.51  1765.7 2017.63
  1778.3 2020.61  1790.5 2028.61  1806.9  2029.8    1811 2032.49  1835.6  2055.8
  1916.8 2110.85  2073.1 2231.88  2093.6 2250.43  2101.8 2262.75  2114.4 2275.44
#Mann= 8 ,-1,0
       0      .1       0     460     .08       0     660      .1       0
     760     .08       0     860      .1       0 1458.94    .025       0
 1535.26    .035       01757.683      .1       0
Bank Sta=1535.26,1757.683
XS Rating Curve= 0 ,0
Exp/Cntr=0.3,0.1

Type RM Length L Ch R = 1 ,40588   ,504.2,506.7,511.9
XS GIS Cut Line= 2
2197509.86454806403458.220333944     2197027.295      405245.093
#Sta/Elev= 30
       0 2081.84    40.4 2076.81    78.8 2067.63   101.7 2058.07   131.5 2041.13
   152.2 2033.61   181.2  2028.6   206.1 2026.56   359.3  2025.5     840 2026.89
    1130 2028.01    1188 2022.94  1246.1 2025.24  1270.9  2023.41299.5382013.224
  1308.2  2011.1  1511.2 2011.061515.1372012.897  1519.5 2017.22  1531.9 2019.04
  1548.5  2027.4  1569.2 2030.11  1594.1 2046.64  1657.8 2094.21    1706 2131.55
  1736.1 2157.68  1786.1 2206.95  1811.1 2228.98  1824.1  2247.7  1850.9 2271.16
#Mann= 10 ,-1,0
       0      .1       0     310     .08       0     410      .1       0
     620     .05       0     820      .1       0     840     .05       0
    1130      .1       0    1230    .025       01299.538    .035       0
1515.137      .1       0
Bank Sta=1299.538,1515.137
XS Rating Curve= 0 ,0
Exp/Cntr=0.3,0.1

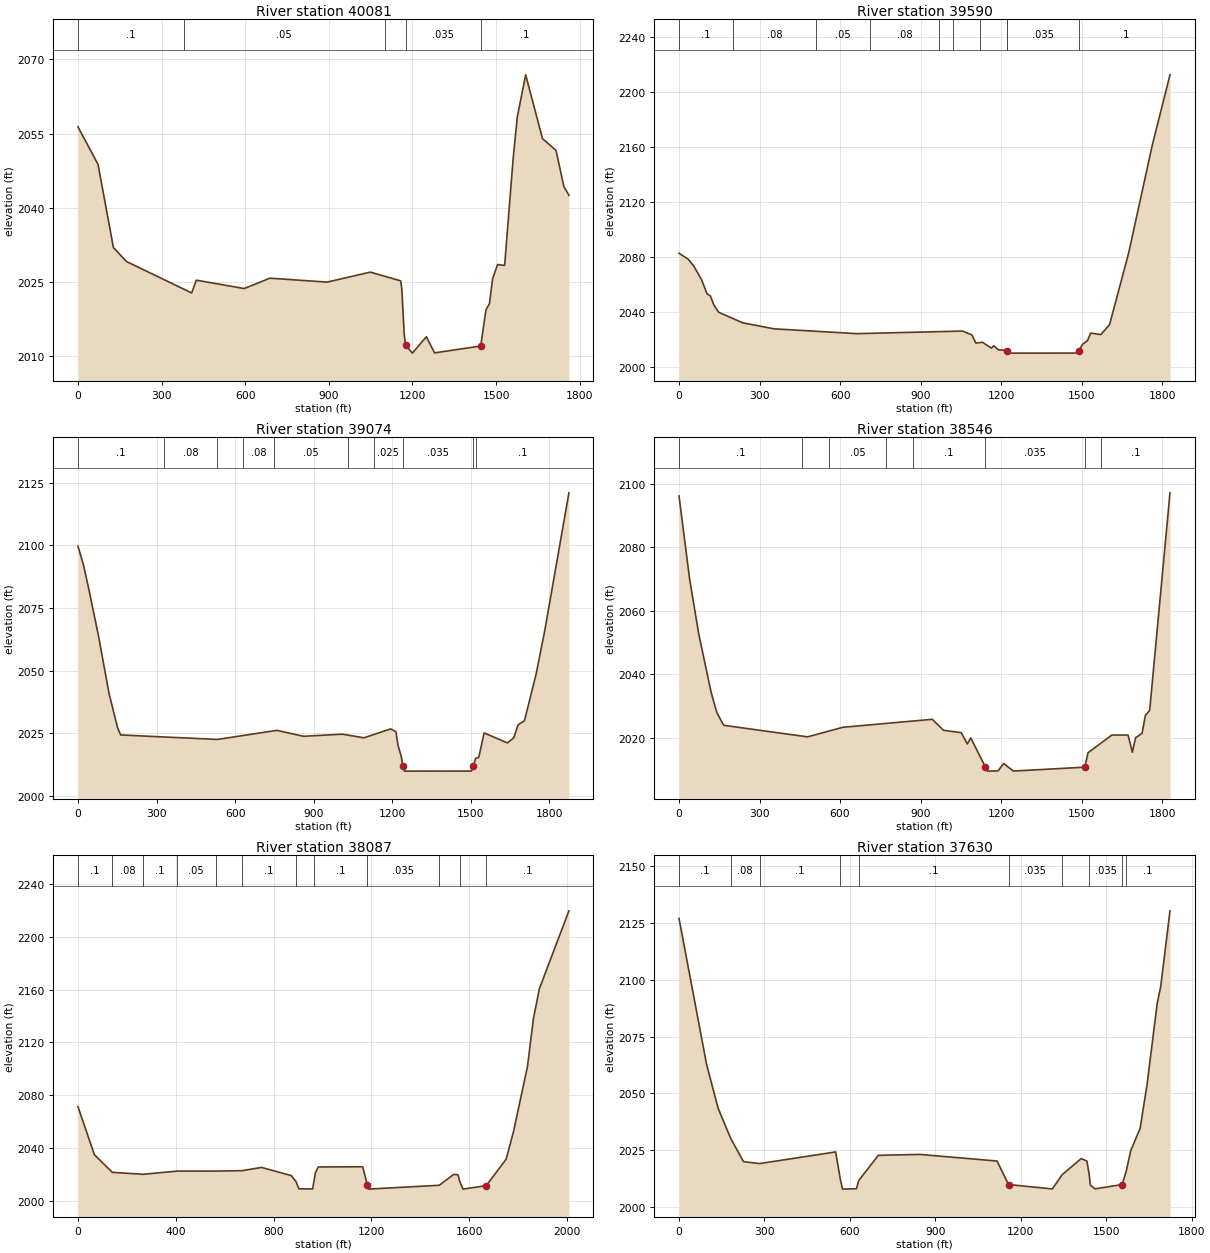
Type RM Length L Ch R = 1 ,40081   ,496.5,491.2,488.2
XS GIS Cut Line= 2
2197052.94358987403399.700849416     2196529.747      405081.422
#Sta/Elev= 30
       0  2056.4    72.1 2048.78   127.2    2032   174.3 2029.17   407.9 2022.83
   424.6 2025.41   596.4 2023.72   688.6 2025.81   893.8 2025.02  1048.8 2027.04
  1157.7 2025.27  1161.9 2023.57  1170.3 2014.541175.0582012.343  1199.6 2010.67
  1249.9 2013.99  1279.2 2010.721444.8052012.106  1463.5 2019.41  1476.1 2020.65
  1487.5 2025.74  1505.4 2028.57  1530.6 2028.39    1561 2049.89    1576 2058.39
    1606  2066.9  1666.4 2054.01  1714.9 2051.64  1743.1 2044.32  1761.2 2042.57
#Mann= 5 ,-1,0
       0      .1       0     380     .05       0    1100      .1       0
1175.058    .035       01444.805      .1       0
Bank Sta=1175.058,1444.805
XS Rating Curve= 0 ,0
Exp/Cntr=0.3,0.1

Type RM Length L Ch R = 1 ,39590   ,539.5,516.1,507.1
XS GIS Cut Line= 2
 2196569.8696931 403172.65724161     2196074.686      404933.269
#Sta/Elev= 30
       0 2082.87    33.8 2078.66    54.6 2073.68    83.6 2063.83   104.4 2053.41
   116.9 2051.88   129.4 2045.48   147.7 2039.98   237.4  2032.3   353.7 2027.95
   661.2 2024.44    1056 2026.31  1091.5 2023.44  1105.8 2017.61  1130.4 2018.17
    1164 2013.87  1172.3  2015.7  1188.8 2012.76  1222.2 2012.09  1234.6 2010.28
  1483.9 2010.31  1489.9 2012.03  1503.3 2016.75  1521.3 2019.29  1533.8 2024.87
  1571.2 2023.72  1603.9 2031.01  1674.9 2083.05  1762.3 2160.89  1828.9 2212.57
#Mann= 10 ,-1,0
       0      .1       0     200     .08       0     510     .05       0
     710     .08       0     970     .05       0    1020     .06       0
    1120      .1       0    1220    .025       0  1222.2    .035       0
  1489.9      .1       0
Bank Sta=1222.2,1489.9
XS Rating Curve= 0 ,0
Exp/Cntr=0.3,0.1

Type RM Length L Ch R = 1 ,39074   ,539.3,527.2,518.3
XS GIS Cut Line= 2
2195941.73387563402944.3607789892195626.87865229404792.399670774
#Sta/Elev= 30
       0 2099.73    21.1 2092.25    41.4 2082.56    77.9 2064.18   118.5 2041.02
   151.1 2027.27   163.1 2024.35   532.4 2022.56   759.6 2026.19     861 2023.82
  1009.6 2024.66  1092.3 2023.21  1193.8 2026.76  1214.1 2025.66  1222.4 2020.05
  1234.4 2015.82 1240.61 2011.95  1246.5 2009.91  1502.2 2009.94  1509.7 2011.95
  1518.4 2015.01  1530.6 2015.43  1550.8 2025.16  1640.1 2021.16  1664.5 2023.28
  1680.7 2028.44    1705 2030.03  1749.7 2048.77  1782.1 2065.85  1874.7 2121.01
#Mann= 10 ,-1,0
       0      .1       0     330     .08       0     530      .1       0
     630     .08       0     750     .05       0    1030      .1       0
    1130    .025       0 1240.61    .035       0  1509.7    .025       0
    1520      .1       0
Bank Sta=1240.61,1509.7
XS Rating Curve= 0 ,0
Exp/Cntr=0.3,0.1

Type RM Length L Ch R = 1 ,38546   ,450.5,459.5,498
XS GIS Cut Line= 3
2195579.20147734402931.4871947912195218.99612667 403996.26867933
2195133.78965845404696.384316904
#Sta/Elev= 30
       0 2096.14    39.8 2069.82    73.6 2052.64     120  2034.2   141.1 2027.88
   166.5 2023.93   478.9 2020.29   609.9  2023.3   943.4 2025.82   985.7 2022.36
  1051.3 2021.62  1074.3 2018.09    1087 2019.95  1141.8 2010.77  1149.2  2009.5
  1188.5 2009.56  1209.6  2011.9  1245.9 2009.53  1511.8 2010.74  1511.8 2010.75
  1511.8 2010.77  1523.9 2015.28  1612.8 2020.87    1673 2020.87  1689.1 2015.47
  1701.2 2019.99  1725.4 2021.42  1737.5 2027.01  1753.6 2028.63  1829.3 2097.14
#Mann= 8 ,-1,0
       0      .1       0     460     .08       0     560     .05       0
     770     .08       0     870      .1       0  1141.8    .035       0
  1511.8    .025       0 1574.06      .1       0
Bank Sta=1141.8,1511.8
XS Rating Curve= 0 ,0
Exp/Cntr=0.3,0.1

Type RM Length L Ch R = 1 ,38087   ,459.9,457,453.1
XS GIS Cut Line= 5
2195276.28408971402942.8066924362194996.20960377403633.444913451
2194798.88439776403821.2221256172194788.01900682403864.944224304
2194626.15768026 404796.18407834
#Sta/Elev= 30
       0 2071.27    67.3 2034.82   140.7 2021.47   265.9 2019.97     404 2022.37
   563.2 2022.41   671.4 2022.72   750.8 2025.19   872.5 2018.99   892.2  2014.3
   903.5 2008.97   959.6 2008.84   965.4 2014.94   971.2 2021.24   982.7 2025.53
  1164.4 2025.691183.3232012.222  1188.8 2008.75  1477.8 2011.65  1536.6 2019.88
  1554.2 2019.58  1562.3 2014.12  1574.7 2008.721669.9132011.383  1751.2 2031.43
  1781.6 2052.62  1838.4 2101.85  1862.8 2138.25  1887.1 2160.82  2007.9 2219.89
#Mann= 12 ,-1,0
       0      .1       0   140.7     .08       0   265.9      .1       0
     404     .05       0   563.2     .08       0   671.4      .1       0
   892.2     .04       0   965.4      .1       01183.323    .035       0
  1477.8      .1       0  1562.3    .035       01669.913      .1       0
Bank Sta=1183.323,1669.913
XS Rating Curve= 0 ,0
Exp/Cntr=0.3,0.1

Type RM Length L Ch R = 1 ,37630   ,499,529.7,595.7
XS GIS Cut Line= 2
2194487.15740239402793.5513850072194224.55567694404497.355664613
#Sta/Elev= 30
       0 2127.02    96.8 2062.78   137.2  2043.5   181.7 2030.18   226.3    2020
   282.9 2019.15     550 2024.27   566.9  2011.9   574.3 2007.91     623 2008.08
     631  2011.7   699.8 2022.77   845.5 2023.18  1116.7 2020.27  1157.1 2009.92
  1310.9    2008  1345.3 2014.24  1412.1 2021.35  1432.3 2020.25  1440.1 2014.41
  1444.5 2009.69  1460.7 2008.04  1555.8 2009.92  1570.1 2015.71  1586.1 2024.83
  1618.9 2034.59  1642.8 2053.31  1679.2 2089.79  1691.4 2097.08  1723.9 2130.34
#Mann= 10 ,-1,0
       0      .1       0   181.7     .08       0   282.9      .1       0
   566.9     .04       0     631      .1       0  1157.1    .035       0
  1345.3      .1       0  1440.1    .035       0  1555.8    .025       0
  1570.1      .1       0
Bank Sta=1157.1,1555.8
XS Rating Curve= 0 ,0
Exp/Cntr=0.3,0.1

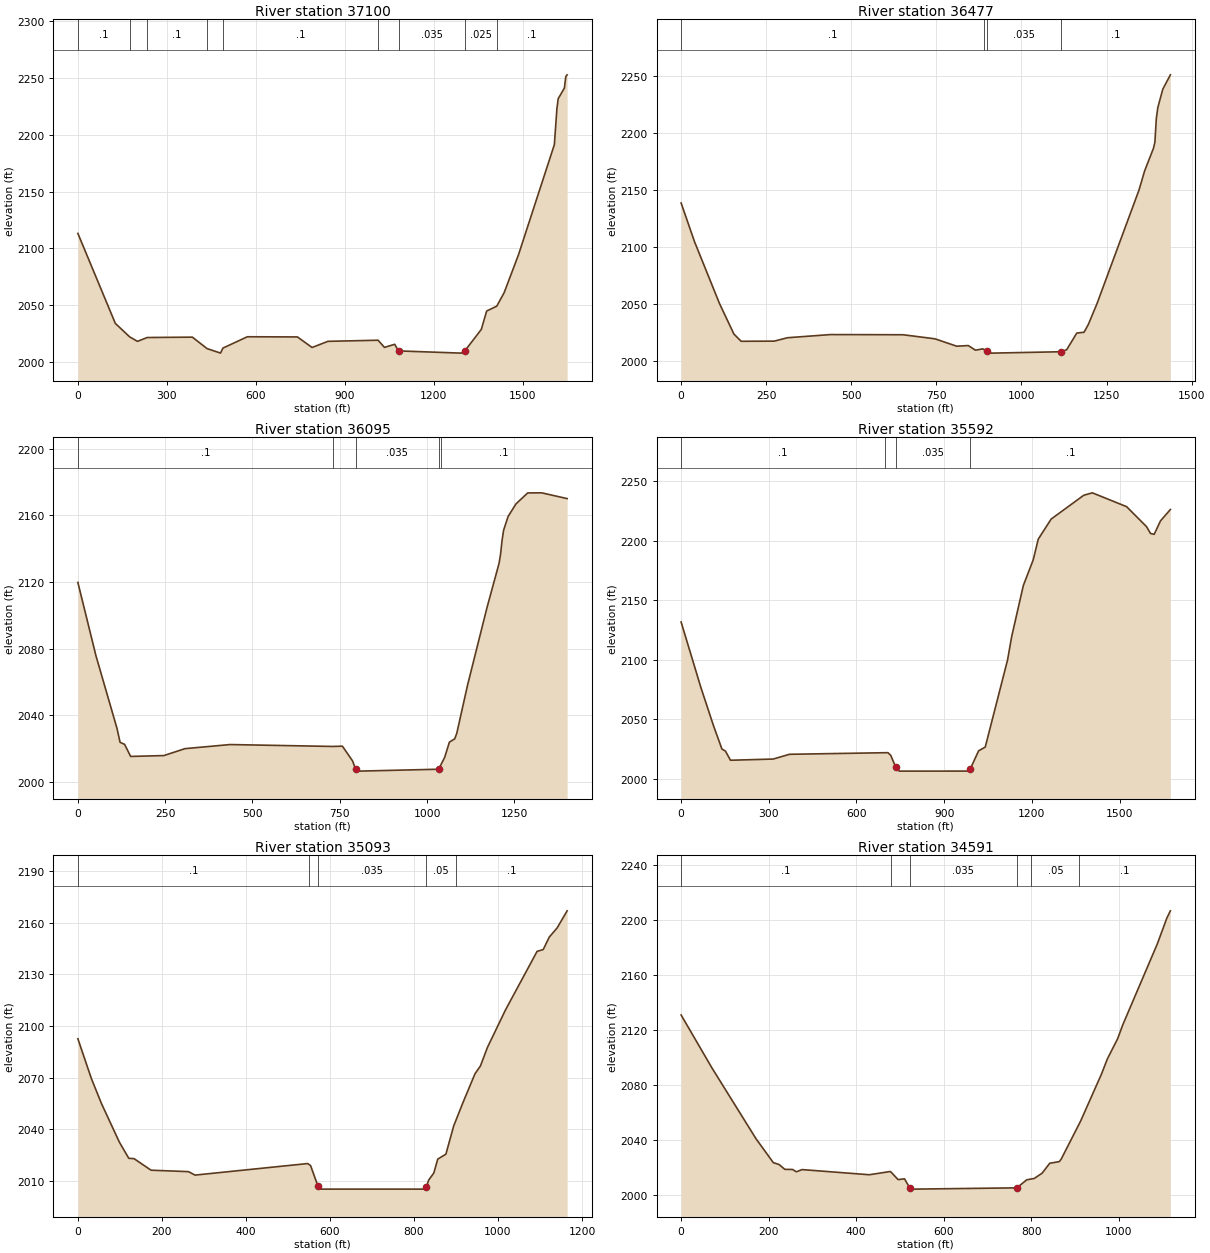
Type RM Length L Ch R = 1 ,37100   ,629.9,623.7,621.7
XS GIS Cut Line= 3
2194097.50679565402801.9209253172193881.62296554403688.175287618
     2193608.188      404373.224
#Sta/Elev= 30
       0 2113.07   126.3 2033.72   174.6 2021.86     201 2017.89   233.9 2021.28
   386.2  2021.6   435.6  2011.5   480.9 2007.56   489.2 2011.97   571.5 2021.94
   740.3 2021.79   789.7 2012.49   843.2  2017.9  1012.3 2018.89  1033.8 2012.56
  1068.3  2015.3  1081.2 2009.47  1292.7 2007.51  1305.2 2009.62  1360.4 2028.44
  1378.4 2044.63  1412.4 2048.89  1437.4 2060.82  1486.1 2094.51  1606.7 2191.35
  1615.3 2223.03  1619.6 2231.87  1640.5 2241.26  1645.4 2251.56  1649.8 2252.92
#Mann= 9 ,-1,0
       0      .1       0   174.6     .08       0   233.9      .1       0
   435.6     .04       0   489.2      .1       0  1012.3    .025       0
  1081.2    .035       0  1305.2    .025       0  1412.4      .1       0
Bank Sta=1081.2,1305.2
XS Rating Curve= 0 ,0
Exp/Cntr=0.3,0.1

Type RM Length L Ch R = 1 ,36477   ,373.8,381,385.8
XS GIS Cut Line= 2
2193556.47043697402727.1697365672193070.46471679404080.028563029
#Sta/Elev= 30
       0 2138.64    39.3 2104.73   112.6 2050.54   155.1 2023.64   176.4  2017.3
   273.8 2017.43   312.4 2020.41   439.6  2023.2   652.2 2023.03   745.9 2019.46
   809.7 2012.98   843.7 2013.55   864.9 2009.49   886.2 2010.63   898.9 2008.87
   911.6 2006.91  1115.7 2008.12  1132.7 2009.87  1162.5  2024.5  1183.8 2025.23
  1196.3 2031.99    1222 2050.41  1345.2 2149.89    1362 2166.93  1387.7 2186.56
    1392 2191.93  1396.2 2212.82  1400.5  2222.2  1415.2 2238.46  1437.5 2251.06
#Mann= 4 ,-1,0
       0      .1       0     890    .025       0   898.9    .035       0
  1115.7      .1       0
Bank Sta=898.9,1115.7
XS Rating Curve= 0 ,0
Exp/Cntr=0.3,0.1

Type RM Length L Ch R = 1 ,36095   ,433.8,503.2,551.8
XS GIS Cut Line= 2
2193209.12528434402693.446968903     2192676.463      403989.548
#Sta/Elev= 30
       0 2119.72    51.6 2075.93   112.2 2032.12   120.8  2023.9   133.8 2022.68
   151.1 2015.43   246.2 2015.94   306.8 2020.09   435.8 2022.55     730 2021.41
   757.6 2021.58   786.8 2012.72   795.4 2007.85   804.1 2006.62  1033.3 2007.76
  1050.6 2014.91  1064.1 2024.01  1079.4    2026  1085.2 2029.28  1116.2 2058.27
  1171.7 2104.59  1206.3 2131.16  1210.6 2136.64  1214.9 2144.95  1219.3 2150.99
  1232.2 2159.27  1254.7 2166.78  1288.4 2173.39  1328.4 2173.44  1401.3 2169.98
#Mann= 5 ,-1,0
       0      .1       0     730    .025       0   795.4    .035       0
  1033.3    .025       0    1040      .1       0
Bank Sta=795.4,1033.3
XS Rating Curve= 0 ,0
Exp/Cntr=0.3,0.1

Type RM Length L Ch R = 1 ,35592   ,465.7,499.2,527.1
XS GIS Cut Line= 4
2192921.57205314 402568.527174672192703.99000736403026.514060358
2192164.95796539403550.9625109512191882.38666655403854.855756229
#Sta/Elev= 30
       0  2131.7    67.6 2076.68   111.4 2044.07   139.6 2024.89   151.6 2023.14
     169 2015.43   315.1 2016.44   370.8 2020.44   707.7 2021.81   717.4 2019.51
   734.52009.548   746.4 2006.28   986.7 2006.31   989.7 2008.29    1018 2023.38
  1040.6  2026.5    1117 2099.84  1131.1 2119.53  1170.9 2162.38  1204.7 2183.98
  1222.1 2201.47  1266.1  2218.3  1377.7 2238.34  1407.1 2240.39  1524.3 2228.75
  1592.4 2211.97  1606.2 2206.19  1618.6 2205.48  1640.5 2216.88  1674.1 2226.38
#Mann= 4 ,-1,0
       0      .1       0  697.04    .025       0   734.5    .035       0
   989.7      .1       0
Bank Sta=734.5,989.7
XS Rating Curve= 0 ,0
Exp/Cntr=0.3,0.1

Type RM Length L Ch R = 1 ,35093   ,478.6,501.5,520.7
XS GIS Cut Line= 2
2192731.74110515402512.287921423     2191748.016      403135.703
#Sta/Elev= 30
       0 2092.56    32.2 2069.44    56.3 2054.89    98.9 2032.54   121.2 2023.22
   133.7 2023.02   174.2 2016.32   263.2 2015.48   278.9 2013.48   547.2 2020.18
     554 2018.95   571.4  2007.1   577.2 2005.34   823.6 2005.34   829.3 2006.57
   835.1 2010.61   847.2 2014.69   856.6 2022.75     876 2025.62   894.5 2041.94
   916.3 2055.36   945.3 2072.28   958.2 2076.79     975 2087.61  1017.9 2109.31
  1093.1 2143.27  1107.6 2144.31  1122.1 2151.55  1140.8 2156.87  1164.6 2166.78
#Mann= 5 ,-1,0
       0      .1       0     550    .025       0   571.4    .035       0
   829.3     .05       0     900      .1       0
Bank Sta=571.4,829.3
XS Rating Curve= 0 ,0
Exp/Cntr=0.3,0.1

Type RM Length L Ch R = 1 ,34591   ,480,497.7,514.7
XS GIS Cut Line= 2
2192508.33600226402174.401563029     2191488.849      402633.143
#Sta/Elev= 30
       0 2131.01    70.4 2092.52   171.2 2040.93   210.7 2023.57   223.9 2022.21
     237 2018.69   254.6 2018.62   263.4 2016.92   276.5 2018.52     430 2014.77
   478.3 2017.15   495.8 2011.24   510.4  2011.8   522.1 2005.38   530.9 2004.31
   767.1 2005.24   789.7 2011.09   806.9 2012.08   824.8 2015.92   842.3 2023.14
   864.3 2024.34   868.7 2026.32   912.8 2053.82   960.8 2088.27   973.9 2099.05
   997.5 2113.85    1009 2123.77    1088 2182.71  1109.9 2201.59  1117.9 2206.81
#Mann= 6 ,-1,0
       0      .1       0     480    .025       0   522.1    .035       0
   767.1    .025       0     800     .05       0     910      .1       0
Bank Sta=522.1,767.1
XS Rating Curve= 0 ,0
Exp/Cntr=0.3,0.1