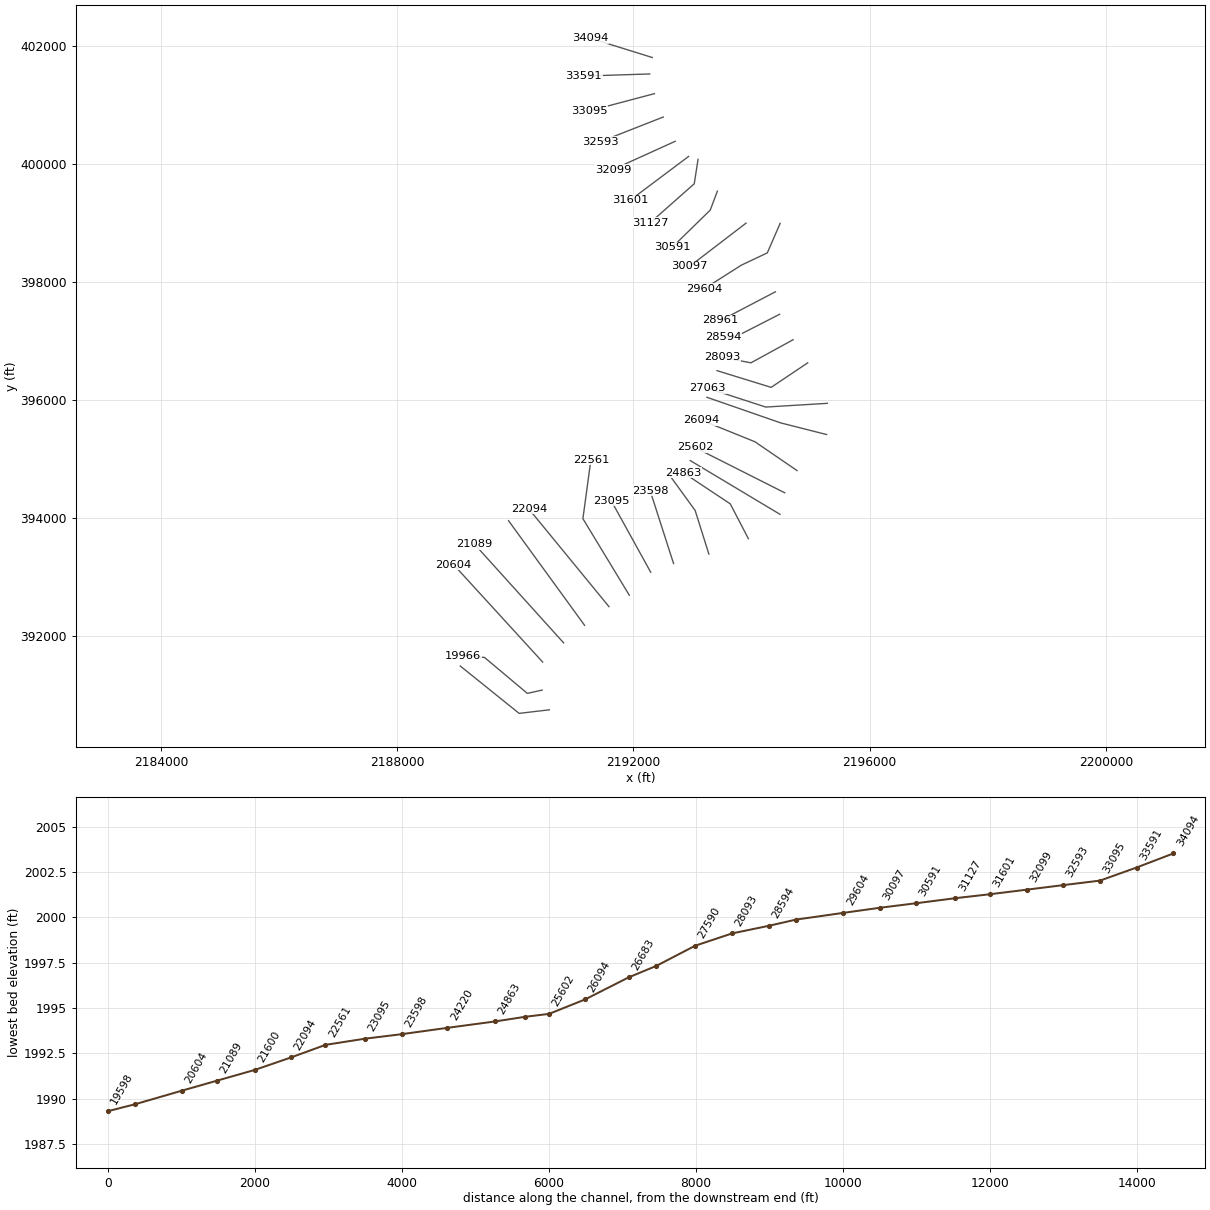
HEC-RAS study GRNBRRRV.prj: GRNBRRRV

--- GRNBRRRV.g01 (geometry) --- (continued)

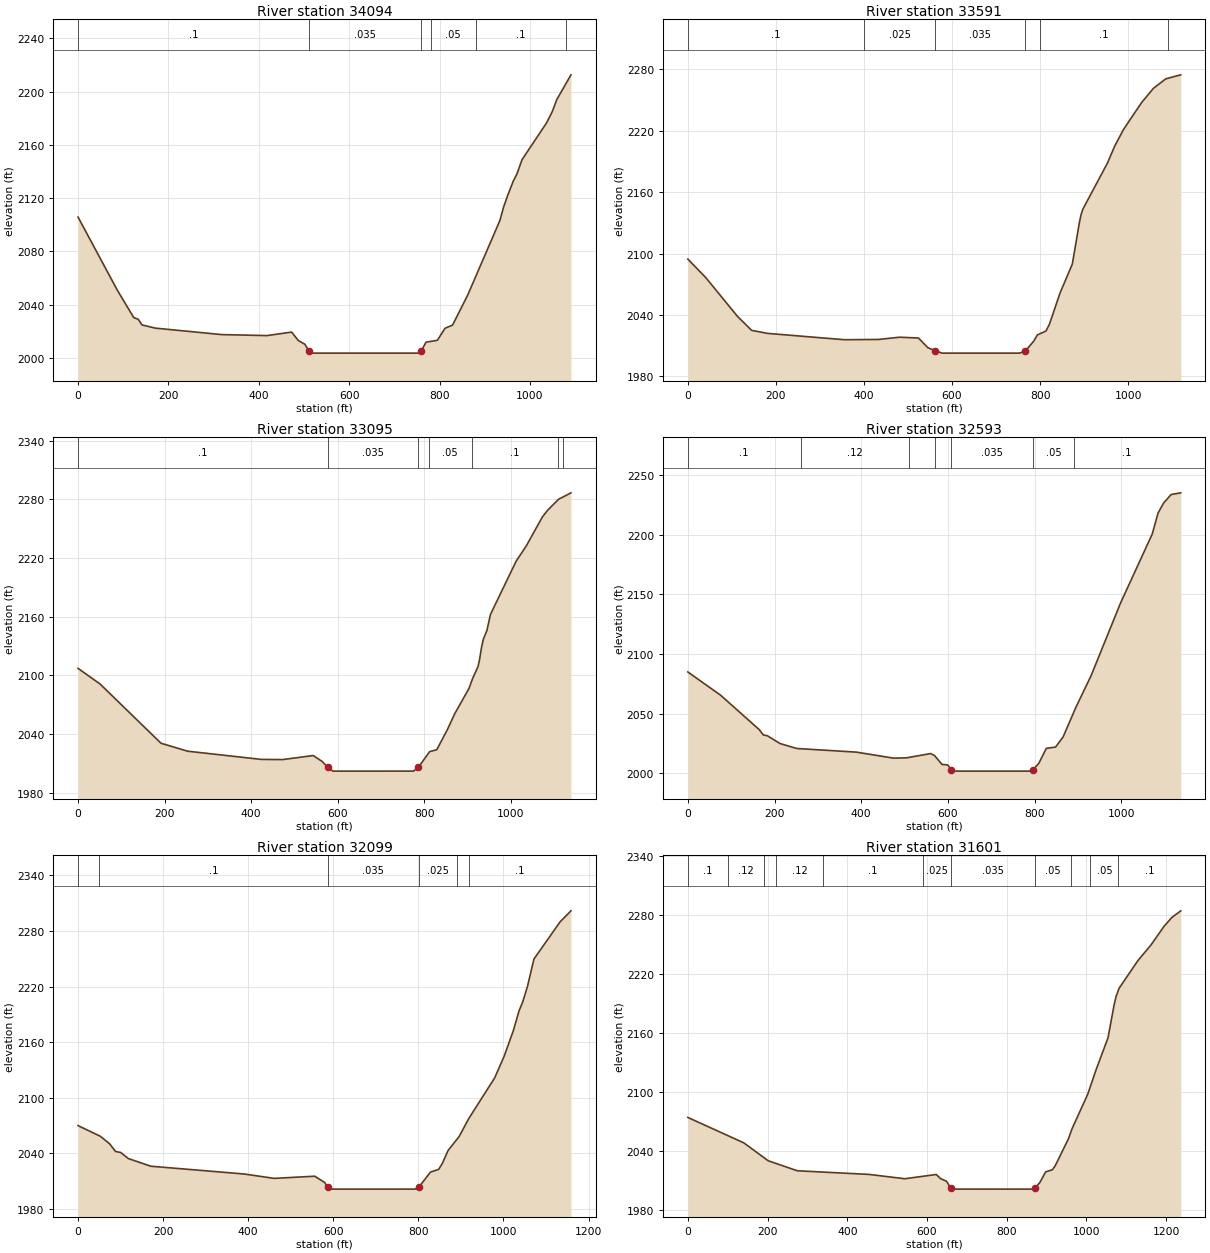
Type RM Length L Ch R = 1 ,34094   ,458.7,502.3,544.9
XS GIS Cut Line= 2
2192319.28930978401797.975076314     2191278.051      402122.586
#Sta/Elev= 30
       0 2105.68    87.1 2050.67   123.2 2030.23   133.1 2028.97   141.5 2024.72
   171.1  2022.3   318.1 2017.44   418.1  2016.7   472.5 2019.34   487.4    2013
   501.9  2010.2   511.2 2005.08   518.6 2003.53   753.2 2003.53   758.9 2004.83
     770 2011.75   795.1 2013.16   811.9 2022.17   828.7 2024.58   862.2 2047.12
   933.4 2103.12   941.8 2113.43   950.2 2121.52   962.7  2132.5   971.1 2138.07
   982.4 2148.84  1036.7 2176.47  1049.5 2185.08  1059.1 2193.81  1090.7 2212.56
#Mann= 6 ,-1,0
       0      .1       0   511.2    .035       0   758.9    .025       0
     780     .05       0     880      .1       0    1080     .06       0
Bank Sta=511.2,758.9
XS Rating Curve= 0 ,0
Exp/Cntr=0.3,0.1

Type RM Length L Ch R = 1 ,33591   ,467.5,496.3,523.6
XS GIS Cut Line= 2
2192277.03454099 401519.19628208     2191158.032      401483.596
#Sta/Elev= 30
       0 2094.53    40.9  2076.4   112.9 2038.56   144.9 2024.99     181 2022.03
   355.7 2015.84   433.1  2016.1   481.1  2018.3   523.8  2017.5   545.1 2008.07
   561.3  2005.2   577.2 2002.75   753.2 2002.75   766.9 2004.99   785.3 2014.28
     794 2020.57   813.3 2024.28   821.3 2030.98   845.3 2061.37   873.3 2089.73
   889.3 2130.22   893.3 2138.26   897.3  2143.4   953.1 2188.33   969.3 2204.65
   989.4 2221.03  1030.6 2247.37  1057.4 2261.22  1085.4 2270.54  1119.6 2274.47
#Mann= 6 ,-1,0
       0      .1       0     400    .025       0   561.3    .035       0
   766.9     .05       0     800      .1       0    1090     .06       0
Bank Sta=561.3,766.9
XS Rating Curve= 0 ,0
Exp/Cntr=0.3,0.1

Type RM Length L Ch R = 1 ,33095   ,489.1,502.3,516.6
XS GIS Cut Line= 2
2192357.47795139401185.796769927      2191256.42      400893.954
#Sta/Elev= 30
       0 2107.19      51 2091.14   191.7 2030.55   253.4 2022.41   423.5 2014.03
   472.6 2013.84   543.4 2017.98   564.2 2011.88   577.3 2005.75     589 2002.03
   775.2 2002.05   786.6 2005.99   812.4 2021.95     829 2023.97   853.8 2044.78
   870.4 2060.68   903.5 2086.73   911.7 2096.67   924.1 2108.81   927.3 2114.83
   932.4 2128.58   936.6 2137.04   944.8 2145.94   953.1  2162.4  1012.3 2216.76
  1035.9 2232.53  1073.1  2262.2  1085.5 2269.15  1110.4 2280.18  1139.1  2286.8
#Mann= 7 ,-1,0
       0      .1       0   577.3    .035       0   786.6    .025       0
     810     .05       0     910      .1       0    1110     .06       0
    1120      .1       0
Bank Sta=577.3,786.6
XS Rating Curve= 0 ,0
Exp/Cntr=0.3,0.1

Type RM Length L Ch R = 1 ,32593   ,490.1,493.6,500.6
XS GIS Cut Line= 2
2192505.93982307 400789.49259073      2191447.44      400373.563
#Sta/Elev= 30
       0 2084.98    75.7 2065.44   164.9 2036.55   173.8 2032.23   183.6 2031.45
   212.5 2024.95   251.2 2020.78   388.7 2017.72   474.6 2012.68   504.5 2012.94
   560.1  2016.5   569.2 2014.86   586.4 2007.41   599.3 2006.99   607.9 2003.06
   615.6 2001.78   788.3 2001.78     797 2003.08   809.9 2008.42   827.1 2020.89
   848.5 2021.97   865.7 2030.42   895.8 2055.67   930.3 2081.81   998.2 2142.74
  1071.6 2200.83  1084.9 2218.34  1097.8 2226.78    1115 2233.87  1137.3 2235.31
#Mann= 7 ,-1,0
       0      .1       0     260     .12       0     510      .1       0
     570    .025       0   607.9    .035       0     797     .05       0
     890      .1       0
Bank Sta=607.9,797
XS Rating Curve= 0 ,0
Exp/Cntr=0.3,0.1

Type RM Length L Ch R = 1 ,32099   ,467.8,498.7,522.9
XS GIS Cut Line= 2
2192707.89895139400378.030257774     2191653.005      399898.992
#Sta/Elev= 30
       0 2070.03    52.4 2058.53    74.4 2050.34      88 2042.17   100.1 2041.05
   118.3 2034.49     171 2026.24   390.7 2017.84     461 2013.12   556.3 2015.47
   579.6 2008.75   586.5 2003.75   597.2 2001.53     792 2001.54     801 2003.54
   828.2 2019.88   847.6 2022.84   856.4  2029.3   869.5 2043.03   895.9 2058.38
   917.9 2077.25   979.4 2121.64  1001.3 2144.56  1023.3 2172.65  1036.5  2193.8
  1045.3 2203.54  1056.5 2220.39  1071.6 2249.69  1133.1 2289.84  1158.6 2301.68
#Mann= 6 ,-1,0
       0     .12       0      50      .1       0   586.5    .035       0
     801    .025       0     890     .05       0     920      .1       0
Bank Sta=586.5,801
XS Rating Curve= 0 ,0
Exp/Cntr=0.3,0.1

Type RM Length L Ch R = 1 ,31601   ,462,473.8,482.8
XS GIS Cut Line= 2
2192935.59461843400122.198258906      2191946.28        399380.3
#Sta/Elev= 30
       0  2074.2   140.3 2048.37   201.7 2030.12   274.6 2019.96   454.3 2016.26
   544.3 2011.86   623.2 2016.17   634.2 2011.95   648.9 2009.31   659.2 2002.62
   664.2 2001.31   863.2 2001.28   871.7 2002.67   883.2 2008.07   897.5  2018.8
   914.6 2021.01   921.8 2025.22   954.6 2052.34   964.2 2063.07  1003.2 2097.81
  1024.2  2122.8  1054.2  2155.4  1069.2 2188.41  1074.2 2197.09  1081.8 2205.57
  1129.2 2233.83  1161.8 2249.61  1194.2  2268.4  1214.2 2277.61  1236.6  2284.4
#Mann= 11 ,-1,0
       0      .1       0     100     .12       0     190      .1       0
     220     .12       0     340      .1       0     590    .025       0
   659.2    .035       0   871.7     .05       0     960      .1       0
    1010     .05       0    1080      .1       0
Bank Sta=659.2,871.7
XS Rating Curve= 0 ,0
Exp/Cntr=0.3,0.1

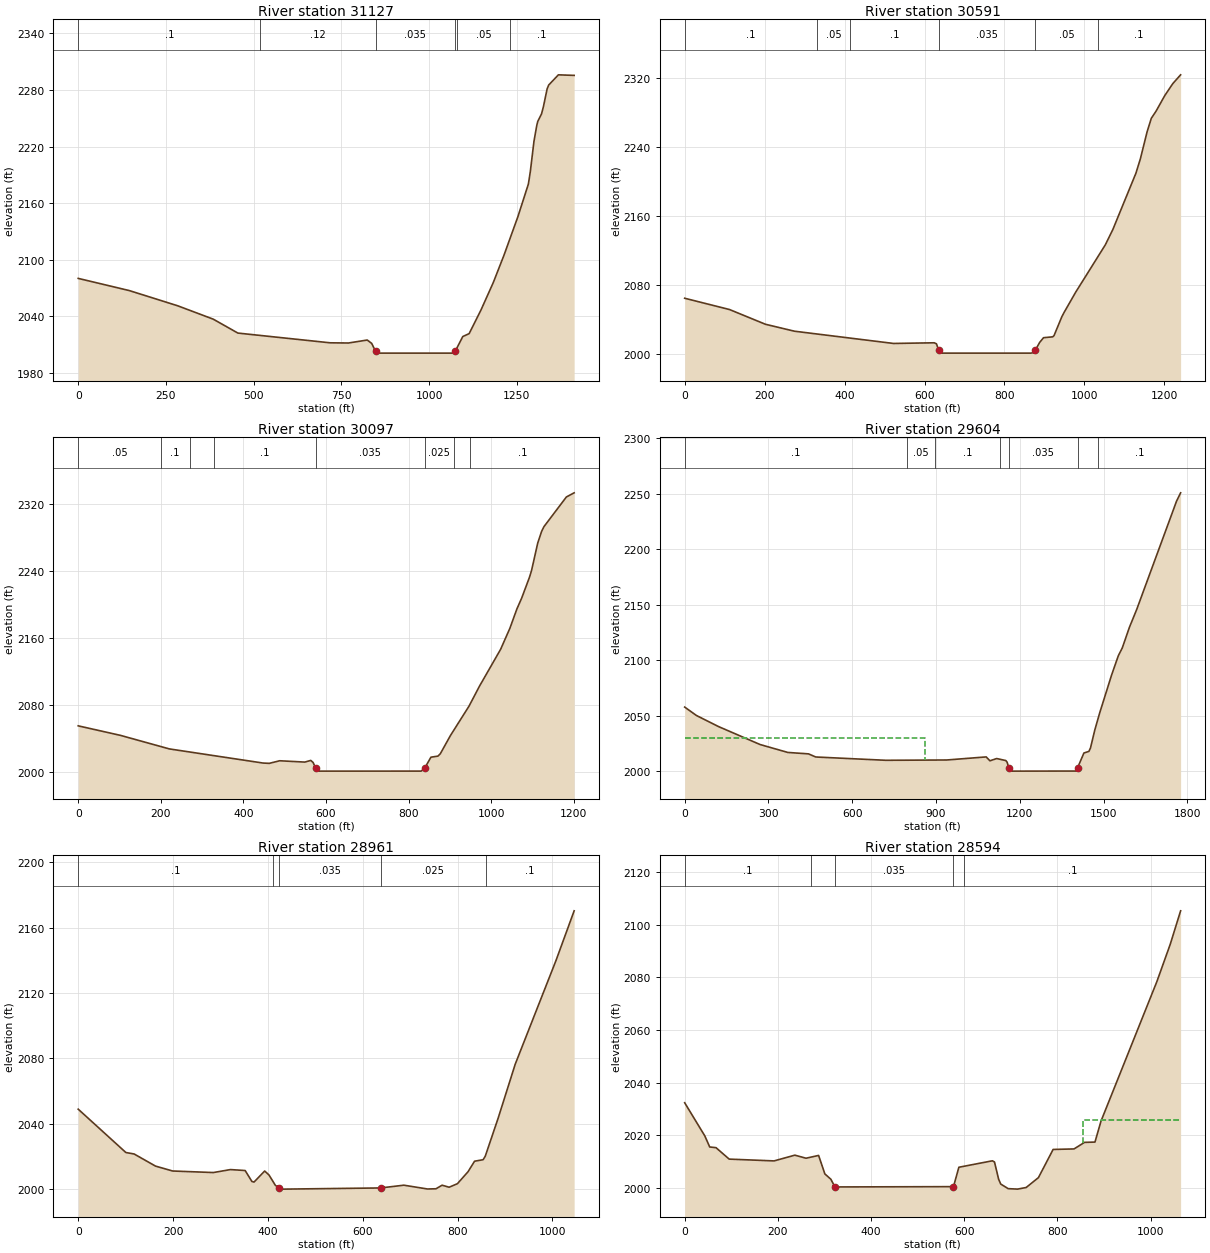
Type RM Length L Ch R = 1 ,31127   ,529.1,536.2,542.1
XS GIS Cut Line= 3
2193095.38582491400073.2417847992193030.88203627399658.891555356
2192286.55329164399000.532291721
#Sta/Elev= 30
       0 2080.31   145.8 2067.36   283.4 2051.27   384.7 2037.09     455 2022.32
   717.8    2012   770.1  2011.8   823.5 2014.95   836.2  2011.4   847.5 2002.86
   855.5 2001.06  1067.9 2001.06  1074.2 2003.01  1095.8 2018.65  1113.9 2021.75
  1147.9 2047.02  1182.7 2075.91  1213.1 2104.82  1252.8 2145.74  1282.7 2180.35
  1288.1 2193.25  1298.7 2225.84  1306.6 2242.47  1309.4 2246.73  1320.1  2254.7
  1325.4 2262.17  1336.1 2281.24  1340.6 2285.34  1368.2 2296.16  1413.1 2295.56
#Mann= 6 ,-1,0
       0      .1       0  519.34     .12       0   847.5    .035       0
  1074.2    .025       0 1079.34     .05       0 1229.34      .1       0
Bank Sta=847.5,1074.2
XS Rating Curve= 0 ,0
Exp/Cntr=0.3,0.1

Type RM Length L Ch R = 1 ,30591   ,515.5,493.3,479.6
XS GIS Cut Line= 3
2193422.29253985399534.3111062792193301.49196327399212.620527238
     2192660.215      398585.435
#Sta/Elev= 30
       0 2064.56   112.3 2051.42     202 2034.32   274.7 2026.25   522.4 2012.02
   624.2 2012.79   629.8 2011.61   635.5 2003.99   638.3  2001.5     642 2000.78
   865.8 2000.78   870.3 2001.12     877 2004.15   888.2 2013.34   897.7  2018.7
   920.6 2019.71     924  2021.2   943.5  2043.1   949.2 2048.13   977.8 2071.36
  1052.2 2126.57  1071.1 2144.47  1128.8 2209.85    1140 2226.68  1156.7 2257.88
  1167.3 2273.65  1179.1 2281.91  1200.9 2300.02    1221 2313.94  1240.6 2324.18
#Mann= 6 ,-1,0
       0      .1       0     330     .05       0  413.62      .1       0
   635.5    .035       0     877     .05       0 1033.62      .1       0
Bank Sta=635.5,877
XS Rating Curve= 0 ,0
Exp/Cntr=0.3,0.1

Type RM Length L Ch R = 1 ,30097   ,509.9,493.3,483.4
XS GIS Cut Line= 2
2193907.40951555398991.578438103     2192954.195      398260.801
#Sta/Elev= 30
       0 2054.65   102.6 2043.23   220.9 2027.06   447.6 2010.19   462.7 2009.82
   487.9 2012.91   548.9 2011.34   563.2 2013.32   568.9 2010.86   575.32003.703
   583.2 2000.53   830.7 2000.56   838.9  2003.9   854.2 2017.16   871.3 2018.49
     877 2021.31   901.2 2042.84   946.6 2078.28   971.8 2102.05    1023 2146.09
  1045.4 2171.18  1062.5 2194.43  1073.9 2207.17  1092.8 2232.09  1097.8 2240.04
  1112.9 2273.12  1122.4  2287.2    1128 2292.75  1182.3 2328.19  1201.1 2333.14
#Mann= 8 ,-1,0
       0     .05       0     200      .1       0     270     .05       0
     330      .1       0   575.3    .035       0   838.9    .025       0
     910     .05       0     950      .1       0
Bank Sta=575.3,838.9
XS Rating Curve= 0 ,0
Exp/Cntr=0.3,0.1

Type RM Length L Ch R = 1 ,29604   ,658,643.3,635.1
XS GIS Cut Line= 4
 2194485.0311663398987.7568753182194267.56889745398487.774654768
2193829.12473886398280.228362161     2193199.913      397880.312
#Sta/Elev= 30
       0 2057.92    42.1 2050.35   120.6 2040.43   270.1 2024.19   369.2 2017.08
   443.4 2015.78   469.5 2012.97   720.9    2010   938.4 2010.28  1079.6 2013.05
  1093.1 2009.55  1117.2 2011.58  1149.9 2009.78  1154.7 2008.261160.6922003.236
  1168.9 2000.25  1401.2 2000.321406.9922003.281  1429.6 2016.56  1447.6 2018.04
  1453.3 2021.22  1468.5 2037.17  1486.4  2052.9  1528.7 2086.73  1552.8  2104.1
    1567 2111.17  1592.5 2129.68  1618.6 2145.76  1761.3 2243.29  1775.9  2250.8
#Mann= 7 ,-1,0
       0      .1       0  795.23     .05       0  895.23      .1       0
 1130.31    .025       01160.692    .035       01406.992     .05       0
 1480.31      .1       0
#XS Ineff= 2 , 0
          861.91 2029.77
Permanent Ineff=
       F       F
Bank Sta=1160.692,1406.992
XS Rating Curve= 0 ,0
Exp/Cntr=0.3,0.1

Type RM Length L Ch R = 1 ,28961   ,368,366.4,369.1
XS GIS Cut Line= 2
2194404.59518146397828.3661017522193478.12879536397343.532331824
#Sta/Elev= 30
       0 2048.84   100.5  2022.3   117.9  2021.4     163 2013.98   199.1 2010.98
   284.9 2010.03     321 2011.85     352 2011.27   366.2 2004.58   370.7 2004.21
   393.2 2010.97   402.3 2008.53   415.8 2002.17   423.5 2000.76   432.4 1999.88
   637.5  2000.6   686.7 2002.29   736.4 1999.97   754.4  2000.1   767.3 2002.28
   782.1 2001.05   799.6 2003.21   822.1 2010.59   835.7 2016.98   853.7 2017.88
   858.3 2020.05   885.3  2043.2   921.4 2076.35  1007.4 2139.86  1045.7  2170.3
#Mann= 5 ,-1,0
       0      .1       0     410    .025       0   423.5    .035       0
   637.5    .025       0     860      .1       0
Bank Sta=423.5,637.5
XS Rating Curve= 0 ,0
Exp/Cntr=0.3,0.1

Type RM Length L Ch R = 1 ,28594   ,496.6,500.9,505.5
XS GIS Cut Line= 3
     2194476.004      397447.4692193672.71833565 397036.57016642
2193514.38842202397070.608775762
#Sta/Elev= 30
       0 2032.35    43.2 2019.76    53.7 2015.55    67.2 2015.29    95.5 2010.94
   191.8 2010.26   236.4 2012.44   260.4 2011.28   287.4 2012.34   300.8 2005.32
   313.7 2003.29322.39952000.369576.79922000.483   588.4 2007.85   660.3  2010.3
   664.8 2009.85   673.7  2003.3   678.2 2001.47   694.2 1999.72   714.2 1999.54
   732.8 2000.16   759.1 2003.91   790.6 2014.61   835.5 2014.81     858  2017.3
   880.4 2017.41   893.3 2025.34  1013.3 2078.39  1041.9 2092.53  1064.2 2105.25
#Mann= 5 ,-1,0
       0      .1       0     270    .025       0322.3995    .035       0
576.7992    .025       0     600      .1       0
#XS Ineff= 2 , 0
                          854.54         2025.73
Permanent Ineff=
       F       F
Bank Sta=322.3995,576.7992
XS Rating Curve= 0 ,0
Exp/Cntr=0.3,0.1

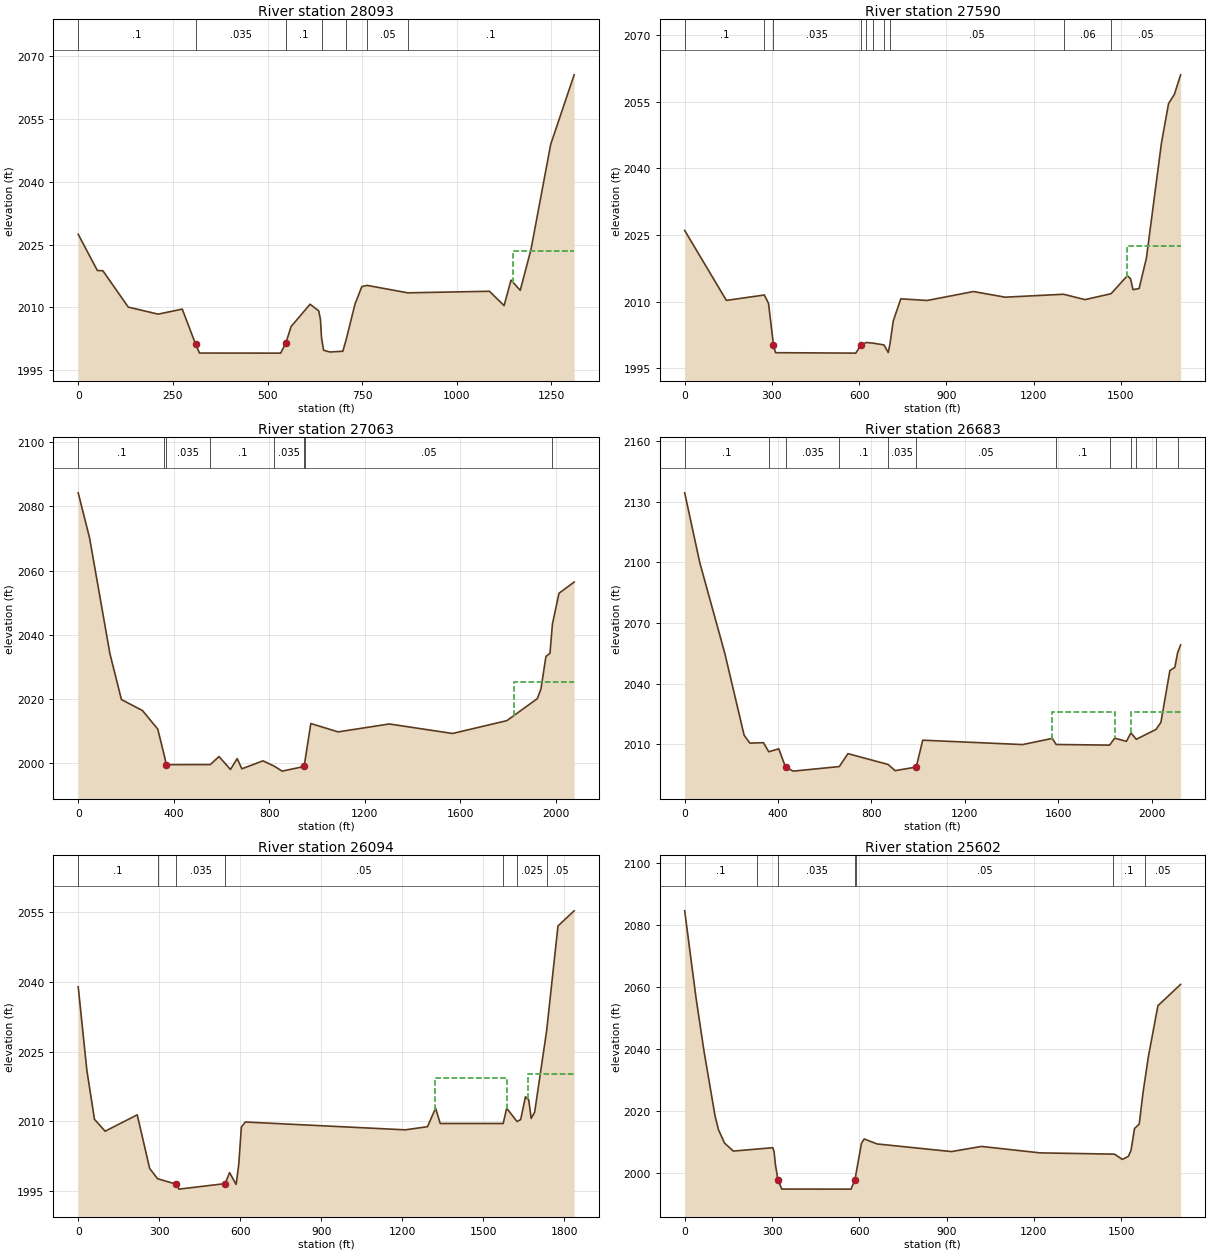
Type RM Length L Ch R = 1 ,28093   ,488.9,503.8,520.6
XS GIS Cut Line= 3
     2194705.172      397016.7272193990.54663824396625.051572992
2193504.29489259396717.644078577
#Sta/Elev= 30
       0 2027.45    50.5 2018.82    65.2 2018.74   132.2 2010.09     211 2008.41
   274.8 2009.61   309.8 2001.32   320.4 1999.14   534.8 1999.12   548.5 2001.55
   562.2 2005.45   612.4 2010.77   635.2 2009.21   639.8 2007.14   642.7 2002.72
   648.2  1999.8   664.9 1999.39     699 1999.57   708.2  2002.5   731.1 2010.82
   749.2 2014.97   762.9 2015.27   870.3 2013.49  1086.1 2013.86  1124.9 2010.44
  1143.1 2016.52  1167.5 2014.09    1196 2023.86    1248 2048.88  1309.9 2065.44
#Mann= 7 ,-1,0
       0      .1       0   309.8    .035       0   548.5      .1       0
   642.7     .04       0   708.2      .1       0   762.9     .05       0
   870.3      .1       0
#XS Ineff= 2 , 0
                         1149.18         2023.57
Permanent Ineff=
       F       F
Bank Sta=309.8,548.5
XS Rating Curve= 0 ,0
Exp/Cntr=0.3,0.1

Type RM Length L Ch R = 1 ,27590   ,595.3,526.9,412.7
XS GIS Cut Line= 3
     2194951.654      396624.7032194332.46970992396209.494864483
2193415.70517014396492.588271406
#Sta/Elev= 30
       0 2026.05   143.4 2010.31   273.9 2011.52   288.3 2009.63305.28492000.224
   312.4 1998.54   588.1 1998.44   606.2 2000.23     624 2000.83   647.9 2000.69
   685.4 2000.28   699.8 1998.58   705.6 2000.42   717.1  2005.7   743.1 2010.66
   833.7 2010.29   992.8  2012.3  1101.7 2011.03  1302.6 2011.69  1376.3 2010.48
  1465.9 2011.81  1521.7 2015.85  1532.9  2015.2  1541.2 2012.73  1562.2 2012.97
  1587.3 2019.79  1639.2 2045.76  1663.5 2054.59  1683.6 2056.68    1705 2061.07
#Mann= 10 ,-1,0
       0      .1       0   273.9    .025       0305.2849    .035       0
   606.2    .025       0     624      .1       0   647.9     .05       0
   685.4     .04       0   705.6     .05       0  1302.6     .06       0
  1465.9     .05       0
#XS Ineff= 2 , 0
                          1519.1         2022.66
Permanent Ineff=
       F       F
Bank Sta=305.2849,606.2
XS Rating Curve= 0 ,0
Exp/Cntr=0.3,0.1

Type RM Length L Ch R = 1 ,27063   ,414.6,380.1,205.5
XS GIS Cut Line= 3
2195284.86553872395938.8343583942194241.11197459395875.764846018
2193259.89519219 396195.52095252
#Sta/Elev= 30
       0 2084.27    47.6 2070.18   132.9 2034.02     181 2019.69   269.2 2016.26
   333.3 2010.46   361.2 2002.04   368.8 1999.35   553.4 1999.38   589.8 2001.89
   637.9 1997.84   665.9 2001.26   685.6 1998.05   774.1 2000.55   822.2 1998.84
   854.2 1997.33   946.4 1998.78   950.1 2000.53   974.5  2012.2  1088.7 2009.59
  1303.3 2012.06  1568.3 2009.09  1795.5 2013.09  1923.3 2019.97  1938.5    2023
  1959.6 2033.15  1976.4 2034.14  1986.7  2043.3  2014.3  2052.9  2077.7  2056.4
#Mann= 8 ,-1,0
       0      .1       0   361.2    .025       0   368.8    .035       0
   553.4      .1       0   822.2    .035       0   946.4      .1       0
   950.1     .05       0  1986.7     .06       0
#XS Ineff= 2 , 0
                         1823.94         2025.23
Permanent Ineff=
       F       F
Bank Sta=368.8,946.4
XS Rating Curve= 0 ,0
Exp/Cntr=0.3,0.1

Type RM Length L Ch R = 1 ,26683   ,645.3,588.9,559.4
XS GIS Cut Line= 3
2195271.08605583395410.387083556 2194494.5169723395607.318232336
2193244.80198755396041.399080841
#Sta/Elev= 30
       0 2134.41    64.9 2099.78   172.2 2054.85   254.7 2014.42   279.5 2010.54
   337.3 2010.77   360.2 2006.27     403 2007.71   432.2  1998.6   465.2 1996.69
   662.3 1998.95   699.3 2005.34   871.4 1999.99     901 1996.93  991.75  1998.7
  1019.6    2012  1447.3 2009.83  1574.3 2012.88  1591.2 2009.87  1819.9 2009.56
  1841.6 2012.99  1891.9 2011.44  1911.4 2015.62  1934.2 2012.44  2018.9 2017.35
  2039.6 2020.82  2078.2 2046.47  2099.3 2048.03  2111.2 2055.27  2124.1 2059.14
#Mann= 12 ,-1,0
       0      .1       0   360.2    .025       0   432.2    .035       0
   662.3      .1       0   871.4    .035       0  991.75     .05       0
  1591.2      .1       0  1819.9     .05       0  1911.4    .025       0
  1934.2     .05       0  2018.9     .06       0  2111.2     .07       0
#XS Ineff= 2 ,-1
 1574.65 1843.66 2026.03 1912.68  2124.1 2026.03
Permanent Ineff=
       T       F
Bank Sta=432.2,991.75
XS Rating Curve= 0 ,0
Exp/Cntr=0.3,0.1

Type RM Length L Ch R = 1 ,26094   ,476.3,491.3,510.6
XS GIS Cut Line= 3
     2194770.456      394799.7722194058.00653649395287.900018424
2193156.69481969395652.439815753
#Sta/Elev= 30
       0 2038.89    31.9 2021.04    60.2 2010.46    99.7 2007.91   218.5 2011.42
   264.5 1999.92   293.7 1997.72   361.6 1996.56     373 1995.48  543.951996.663
   560.4 1999.02   584.6 1996.49   594.3 2000.78     604 2008.82   618.6 2009.88
  1210.8  2008.2  1293.1 2008.88    1323 2012.86  1340.2 2009.56  1573.2 2009.56
  1586.2 2012.84  1624.5 2009.98  1637.9  2010.4  1655.6 2015.29  1667.9 2014.62
  1676.8 2010.65  1689.7 2011.99    1734 2029.44    1776 2051.94  1835.9 2055.19
#Mann= 7 ,-1,0
       0      .1       0   293.7    .025       0   361.6    .035       0
  543.95     .05       0  1573.2     .05       0  1624.5    .025       0
    1734     .05       0
#XS Ineff= 2 ,-1
 1319.44 1587.61 2019.37 1664.23  1835.9 2020.16
Permanent Ineff=
       T       F
Bank Sta=361.6,543.95
XS Rating Curve= 0 ,0
Exp/Cntr=0.3,0.1

Type RM Length L Ch R = 1 ,25602   ,334.6,322.4,316.6
XS GIS Cut Line= 2
     2194562.463      394423.2932193041.24891463395191.085722447
#Sta/Elev= 30
       0 2084.42    38.8 2056.53    66.3 2039.23   104.3 2018.34   116.3  2013.8
     137 2009.54   166.9 2006.95   302.8 2008.03   307.2 2006.71   311.7 2002.59
   320.7 1997.66   333.6  1994.7   571.6 1994.68     585  1997.7   607.4 2009.42
   616.7 2010.85   661.1 2009.25   916.6 2006.79  1019.7 2008.45  1221.3 2006.37
  1476.7 2005.96  1503.9 2004.26  1524.7 2005.27  1533.6 2007.16  1545.6 2014.22
  1561.8 2015.66    1575  2025.9  1593.2 2037.37    1626 2053.83    1704  2060.7
#Mann= 7 ,-1,0
       0      .1       0     250    .025       0   320.7    .035       0
     585    .025       0     590     .05       0    1470      .1       0
    1580     .05       0
Bank Sta=320.7,585
XS Rating Curve= 0 ,0
Exp/Cntr=0.3,0.1

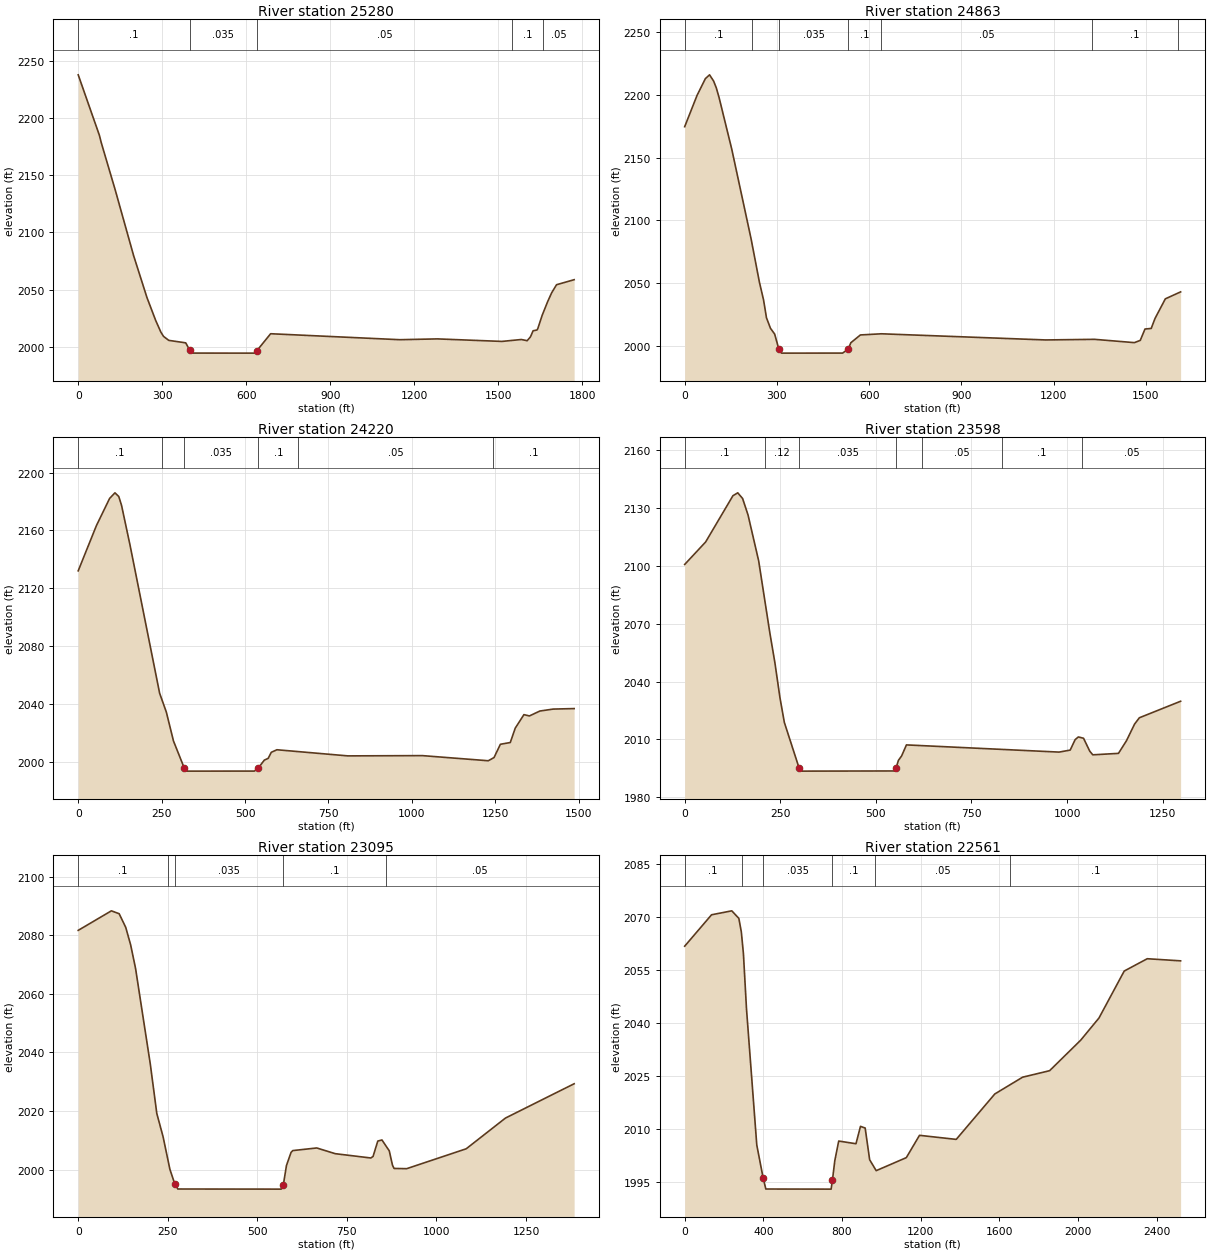
Type RM Length L Ch R = 1 ,25280   ,499.6,417,351.3
XS GIS Cut Line= 2
2194481.62127438394058.9415435142192962.31188641394969.597935082
#Sta/Elev= 30
       0 2237.61    75.6 2184.83    82.2 2178.46   132.3 2136.96     198 2079.58
   245.5 2043.11   276.8 2023.02   295.5 2012.73   304.8 2009.14   323.5 2005.66
   384.1 2003.49   398.31996.991   407.4 1994.55   631.3 1994.52   638.3 1996.69
   687.2 2011.46  1148.6 2006.25  1282.7 2006.95  1513.1 2004.75  1582.6 2006.41
  1603.5 2005.38  1615.3 2008.74  1624.6 2014.03  1638.6 2014.72  1641.4 2015.87
  1657.2 2027.64  1677.1 2039.74  1690.9 2047.17  1708.4 2054.27  1771.3 2058.67
#Mann= 5 ,-1,0
       0      .1       0   398.3    .035       0   638.3     .05       0
    1550      .1       0    1660     .05       0
Bank Sta=398.3,638.3
XS Rating Curve= 0 ,0
Exp/Cntr(USF)=0,0
Exp/Cntr=0.3,0.1

Type RM Length L Ch R = 1 ,24863   ,668.6,643.1,622.6
XS GIS Cut Line= 3
2193947.30757525393645.429202445  2193640.657974394235.497374532
 2192850.8029405394760.518661508
#Sta/Elev= 30
       0 2174.63    40.3 2199.61    67.4 2212.95    80.9 2215.96    94.1 2211.01
     103 2205.49   111.9 2197.87     153 2156.91   216.1 2085.25   243.1 2050.83
   256.7 2036.55   266.1 2022.41   279.2    2014   292.7 2009.47   306.3 1997.53
   315.3 1994.26   513.6 1994.29   531.7 1997.34   540.7 2002.57   571.7 2008.74
     640 2009.66  1174.4 2004.76  1333.2 2005.25  1462.9 2002.62  1482.1 2004.41
  1497.5 2013.46  1517.7 2013.92  1530.1 2021.87  1563.7 2037.51  1613.4 2043.05
#Mann= 7 ,-1,0
       0      .1       0     220    .025       0   306.3    .035       0
   531.7      .1       0     640     .05       0 1324.99      .1       0
 1604.99     .05       0
Bank Sta=306.3,531.7
XS Rating Curve= 0 ,0
Exp/Cntr(USF)=0,0
Exp/Cntr=0.3,0.1

Type RM Length L Ch R = 1 ,24220   ,620.3,622.1,623.3
XS GIS Cut Line= 3
2193278.25389981393385.2416619972193045.94359584394123.988428626
2192627.78504869394700.117982475
#Sta/Elev= 30
       0 2132.15    54.4 2163.28    94.1 2182.11   110.1 2185.98   121.5 2183.45
   129.9 2177.32   155.1  2150.1     244 2047.68   264.1 2034.67   285.5 2014.72
   317.4 1996.28   326.9 1993.91   528.3 1993.94   540.3 1996.24   557.6 2001.47
   569.4 2002.74   578.6 2006.89   595.4 2008.66   807.9 2004.43  1031.4 2004.61
    1229 2001.07  1246.2 2003.28  1265.2 2012.44  1294.9 2013.65  1309.7 2023.55
  1335.8  2032.9  1352.2 2031.99  1383.5 2035.38  1423.4 2036.73  1486.3 2037.07
#Mann= 6 ,-1,0
       0      .1       0     250     .12       0   317.4    .035       0
   540.3      .1       0     660     .05       0 1244.41      .1       0
Bank Sta=317.4,540.3
XS Rating Curve= 0 ,0
Exp/Cntr(USF)=0,0
Exp/Cntr=0.3,0.1

Type RM Length L Ch R = 1 ,23598   ,465.1,502.4,527.9
XS GIS Cut Line= 2
     2192680.401      393224.9892192283.51802431394459.888440367
#Sta/Elev= 30
       0 2100.65    54.8  2112.3   126.2 2136.27   138.8 2137.77   151.5 2134.84
   165.7 2126.31   193.5 2102.55   222.8 2065.14   236.1 2049.59   249.1 2031.71
   260.7 2018.79   299.2 1995.22   306.9 1993.56   550.6 1993.65  553.171995.372
     559 1999.12   567.4 2001.44     580 2007.15   979.2 2003.42  1008.3 2004.46
  1021.2 2009.87  1029.6 2011.27  1043.2 2010.59  1059.6 2003.85  1067.4 2002.01
  1134.6 2002.76  1155.6 2009.36  1176.6 2017.91  1189.2 2021.21  1297.1 2029.77
#Mann= 7 ,-1,0
       0      .1       0     210     .12       0   299.2    .035       0
  553.17      .1       0     620     .05       0     830      .1       0
    1040     .05       0
Bank Sta=299.2,553.17
XS Rating Curve= 0 ,0
Exp/Cntr=0.3,0.1

Type RM Length L Ch R = 1 ,23095   ,523.2,534.7,537.7
XS GIS Cut Line= 2
     2192293.945      393077.1092191624.86948445394289.025799892
#Sta/Elev= 30
       0 2081.64    92.6 2088.31   114.3 2087.32   132.6 2082.68   146.3 2076.73
     160  2068.7   201.1  2036.1   219.4 2019.12   236.9 2011.19   255.9 2000.08
   269.2 1995.22   278.1 1993.35   566.6 1993.31   572.5 1994.72   581.3 2001.38
   594.1 2005.85     599 2006.47   665.8 2007.36   717.4 2005.41   816.8 2003.94
     823 2004.47   836.2 2009.72   847.8 2010.09   868.2 2006.39   877.3 2001.46
   881.6 2000.37   916.9 2000.29    1083 2007.08  1192.6 2017.57  1384.3 2029.28
#Mann= 5 ,-1,0
       0      .1       0     250     .12       0   269.2    .035       0
   572.5      .1       0     860     .05       0
Bank Sta=269.2,572.5
XS Rating Curve= 0 ,0
Exp/Cntr=0.3,0.1

Type RM Length L Ch R = 1 ,22561   ,442.9,466.7,506.2
XS GIS Cut Line= 3
2191930.85413677392688.3107500832191145.64530935393984.602246243
2191280.66282727 394981.22430101
#Sta/Elev= 30
       0 2061.79   136.6 2070.69   239.5 2071.81   275.4 2069.67     288 2065.85
   298.6 2059.72   314.3 2044.02   366.6 2005.45   398.7 1996.19   412.6    1993
   744.6 1992.97   751.41995.625   763.3 2001.06   783.1 2006.59   870.9 2005.83
   893.8 2010.75   917.6 2010.28   940.4 2001.29   973.7  1998.2  1126.8 2001.89
  1193.8 2008.21  1380.6 2007.06  1576.7 2019.93    1718 2024.68  1855.2 2026.52
  2012.9 2035.14  2106.3 2041.45  2234.6 2054.75  2351.7 2058.24  2521.3 2057.64
#Mann= 6 ,-1,0
       0      .1       0     290    .025       0   398.7    .035       0
   751.4      .1       0     970     .05       0 1655.56      .1       0
Bank Sta=398.7,751.4
XS Rating Curve= 0 ,0
Exp/Cntr(USF)=0,0
Exp/Cntr=0.3,0.1

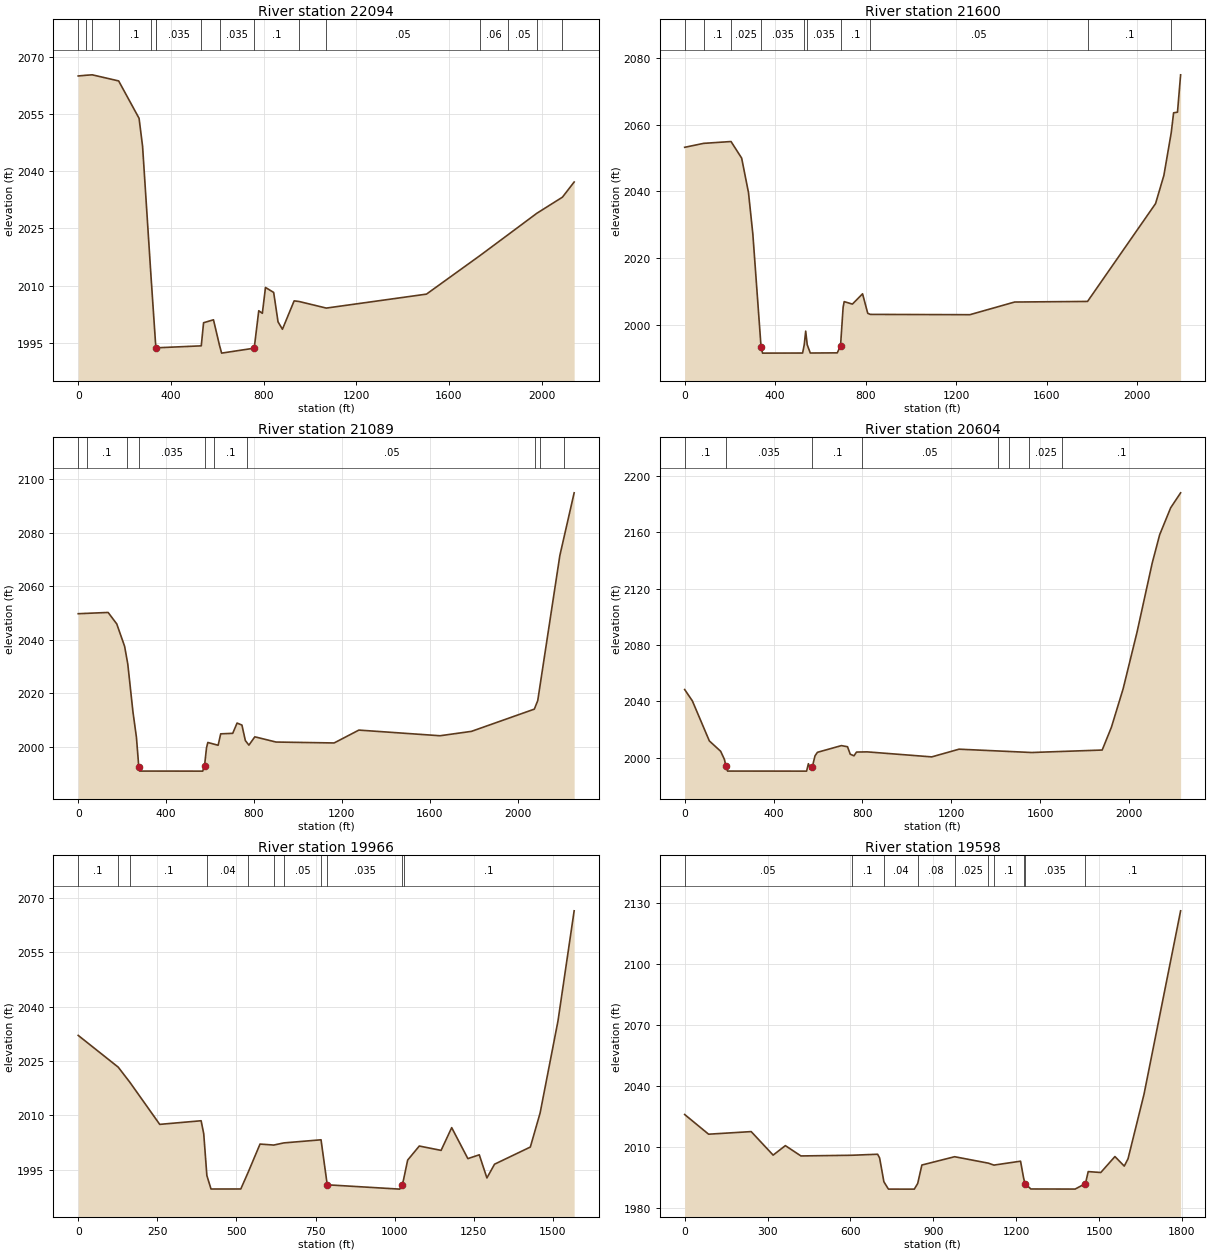
Type RM Length L Ch R = 1 ,22094   ,501.7,493.7,481.9
XS GIS Cut Line= 2
     2191586.893      392494.2382190230.17750936 394150.33125603
#Sta/Elev= 30
       0 2064.95    34.8 2065.14    60.7 2065.25   174.6 2063.65   262.7 2053.85
   277.9  2046.5   313.8 2012.84   333.7 1994.99335.7973 1993.67   531.2 1994.19
   541.2 2000.25   583.9 2001.02   610.2 1994.26   619.1 1992.28759.79391993.579
   779.4 2003.39   794.9 2002.72   808.4  2009.5   843.8 2008.19   862.7 2000.47
   881.6 1998.54   932.1 2005.98   953.4 2005.82    1071 2004.09  1503.4 2007.75
  1733.8 2017.83    1855  2023.3  1979.9 2028.95  2090.3 2033.17  2140.9 2037.15
#Mann= 16 ,-1,0
       0     .12       0    34.8      .1       0    60.7     .12       0
   174.6      .1       0   313.8     .12       0   333.7    .025       0
335.7973    .035       0   531.2      .1       0   610.2    .035       0
759.7939      .1       0   953.4     .06       0    1071     .05       0
  1733.8     .06       0    1855     .05       0  1979.9     .06       0
  2090.3     .05       0
Bank Sta=335.7973,759.7939
XS Rating Curve= 0 ,0
Exp/Cntr=0.3,0.1

Type RM Length L Ch R = 1 ,21600   ,498.7,511.4,547.4
XS GIS Cut Line= 2
     2191174.435      392177.4322189886.45753151393950.795608217
#Sta/Elev= 30
       0 2053.18    83.7 2054.36   204.8 2054.91   251.8 2049.95   282.1  2039.6
   301.3 2027.18   337.51993.469   344.2 1991.59   521.2 1991.62   528.4  1994.1
   534.8 1998.17   541.6 1994.08   555.2 1991.62   674.4 1991.67   688.81993.791
   700.2  2005.3   704.9    2007   741.2 2006.26   786.1 2009.34     809 2003.51
   820.3 2003.18  1260.3 2003.09  1458.1 2006.88  1780.4 2007.06    2081 2036.34
  2117.8 2044.79  2150.2 2057.54  2160.7  2063.5  2177.9  2063.7  2191.7 2074.87
#Mann= 10 ,-1,0
       0     .12       0    83.7      .1       0   204.8    .025       0
   337.5    .035       0   528.4      .1       0   541.6    .035       0
   688.8      .1       0   820.3     .05       0  1780.4      .1       0
  2150.2     .06       0
Bank Sta=337.5,688.8
XS Rating Curve= 0 ,0
Exp/Cntr=0.3,0.1

Type RM Length L Ch R = 1 ,21089   ,491.6,484.2,485.1
XS GIS Cut Line= 2
     2190819.349      391880.409 2189307.2903224393556.195625354
#Sta/Elev= 30
       0 2049.73   136.1  2050.2   175.6  2045.9   211.2 2037.56   225.7 2030.92
   249.2 2013.06     265 2003.61275.69241992.565   280.3 1991.02   566.7    1991
 575.0841993.095   583.9 1999.69   589.9 2001.69   636.8 2000.65   648.5 2004.91
   703.3  2005.1     723 2008.94   745.1 2008.18   760.7  2002.4   776.9  2000.7
   803.8  2003.8   900.4 2001.85  1164.8 2001.51  1277.3 2006.31  1646.8  2004.2
  1789.9 2005.84  2075.9 2014.13  2091.4 2017.32    2192 2071.44  2257.1 2094.83
#Mann= 10 ,-1,0
       0     .07       0      40      .1       0     220    .025       0
275.6924    .035       0 575.084    .025       0     620      .1       0
     770     .05       0    2080      .1       0    2100     .05       0
    2210      .1       0
Bank Sta=275.6924,575.084
XS Rating Curve= 0 ,0
Exp/Cntr=0.3,0.1

Type RM Length L Ch R = 1 ,20604   ,629.4,638.7,654.1
XS GIS Cut Line= 2
     2190463.857         391556.2188957.96858513393204.160410332
#Sta/Elev= 30
       0 2048.37    34.6 2040.31     111 2011.91     162 2004.52     179 1998.74
 185.8741993.757   193.1 1990.48   548.8 1990.44     557  1995.7   566.9 1991.74
   574.7 1993.52   586.6 2001.26   597.6  2003.8   705.6 2008.56   733.1 2007.75
   745.2 2002.47   762.2  2001.3   773.6 2003.98   821.7 2004.11  1112.3 2000.55
  1235.1 2006.02    1562 2003.66  1879.4 2005.41  1920.9 2021.56  1973.8 2048.95
  2036.3  2089.1  2104.7 2138.24  2138.2 2158.28  2187.7  2177.4  2232.5 2188.03
#Mann= 8 ,-1,0
       0      .1       0 185.874    .035       0   574.7      .1       0
     800     .05       0    1410    .025       0    1460     .05       0
    1550    .025       0    1700      .1       0
Bank Sta=185.874,574.7
XS Rating Curve= 0 ,0
Exp/Cntr=0.3,0.1

Type RM Length L Ch R = 1 ,19966   ,371,367.9,372.8
XS GIS Cut Line= 4
2190455.68370656391080.7234466012190204.78857827391024.968973648
2189479.98042988391633.6219700532189117.57635568391666.145412609
#Sta/Elev= 30
       0 2032.07   126.5 2023.31   163.4 2019.13   257.6 2007.54   388.4 2008.54
   396.7 2004.96   406.6 1993.44   419.7 1989.72   513.8 1989.73   537.2 1994.36
   574.6 2002.11   618.1 2001.84   649.6 2002.43   767.4 2003.29     7871990.883
  1016.2 1989.69  1024.2 1990.85  1028.6 1992.47  1041.1 1997.69  1077.9 2001.57
  1146.8 2000.37  1180.3 2006.64  1231.4  1998.1  1267.5 1999.15  1291.6 1992.77
  1315.7 1996.56  1428.8 2001.29  1459.7 2010.67  1516.2 2036.05  1567.3 2066.41
#Mann= 11 ,-1,0
       0      .1       0   126.5     .05       0   163.4      .1       0
   406.6     .04       0   537.2     .08       0   618.1      .1       0
   649.6     .05       0   767.4    .025       0     787    .035       0
  1024.2    .025       0  1028.6      .1       0
Bank Sta=787,1024.2
XS Rating Curve= 0 ,0
Exp/Cntr(USF)=0,0
Exp/Cntr=0.3,0.1

Type RM Length L Ch R = 1 ,19598   ,135.5,144.2,155.1
XS GIS Cut Line= 3
2190578.21477898  390746.48138272190065.82612942390686.171245045
     2189069.242      391488.637
#Sta/Elev= 30
       0 2026.05    86.6 2016.36   240.8 2017.64   320.2 2006.06   364.5 2010.73
   420.9 2005.65   605.4 2005.99   698.5 2006.49   705.7 2004.67   721.2 1992.93
   737.6 1989.32   831.3 1989.31   843.6 1992.11   858.7 2001.18   977.3 2005.27
  1099.6 2002.09  1119.5 2001.14  1215.9 2003.07  1226.8 1994.94  1231.9 1992.07
  1253.2 1989.38  1413.6 1989.34 1450.811992.049  1460.9 1997.94  1506.4  1997.5
  1557.6 2005.35  1591.4 2000.65    1605 2004.25  1662.9 2036.04  1795.4 2126.36
#Mann= 10 ,-1,0
       0     .05       0   605.4      .1       0   721.2     .04       0
   843.6     .08       0   977.3    .025       0  1099.6     .08       0
  1119.5      .1       0  1226.8    .025       0  1231.9    .035       0
 1450.81      .1       0
Bank Sta=1231.9,1450.81
XS Rating Curve= 0 ,0
Exp/Cntr=0.3,0.1