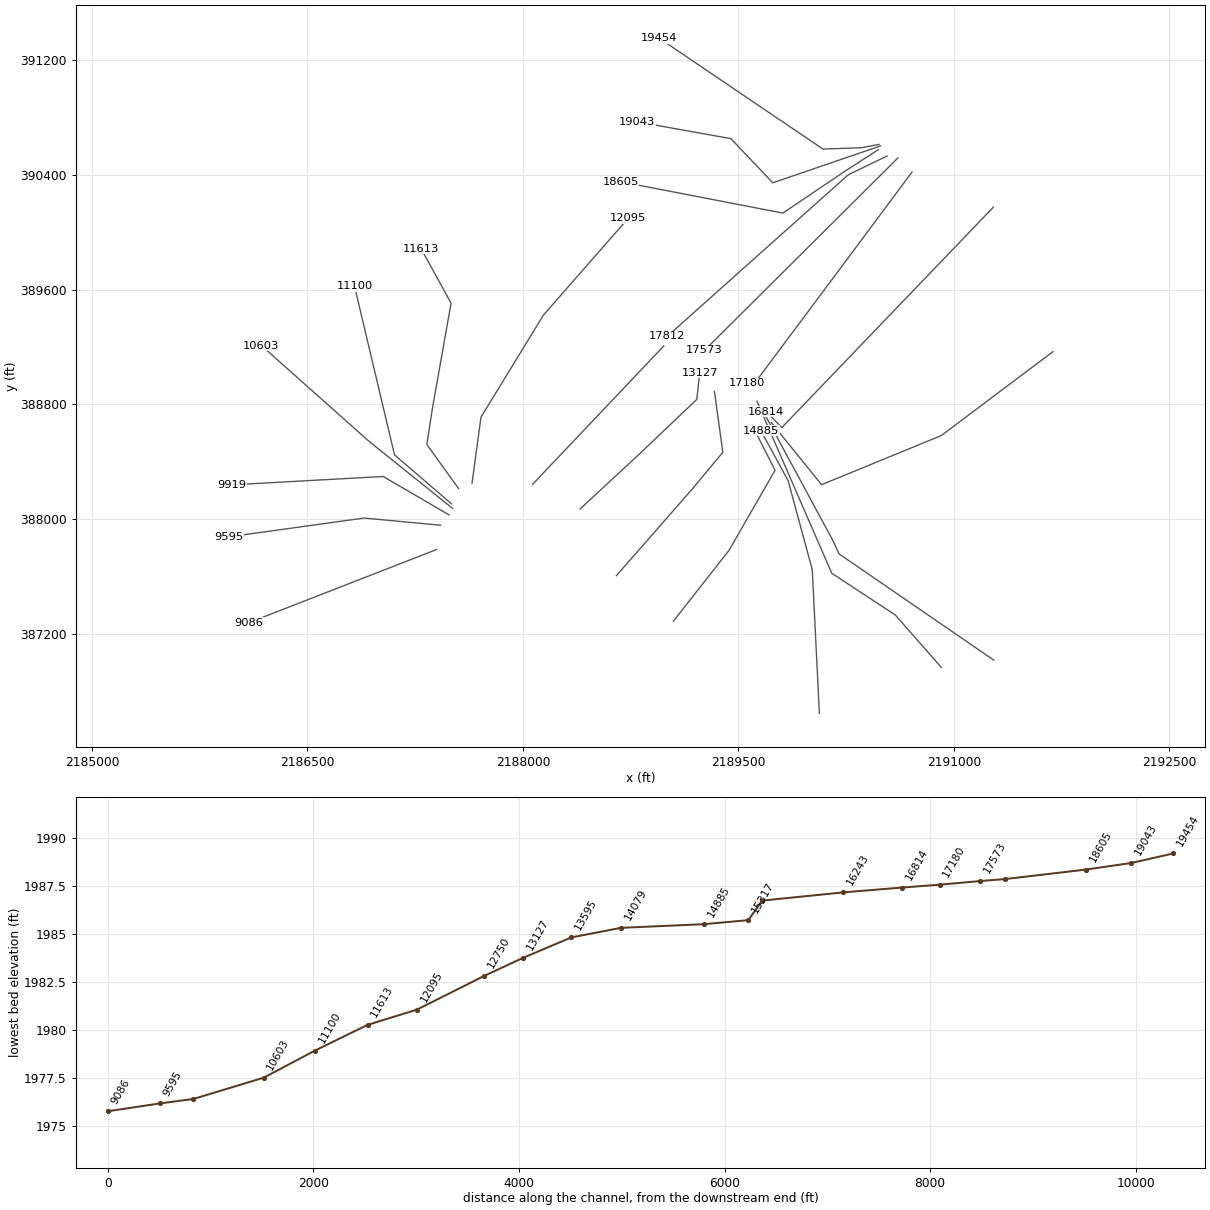
HEC-RAS study GRNBRRRV.prj: GRNBRRRV

--- GRNBRRRV.g01 (geometry) --- (continued)

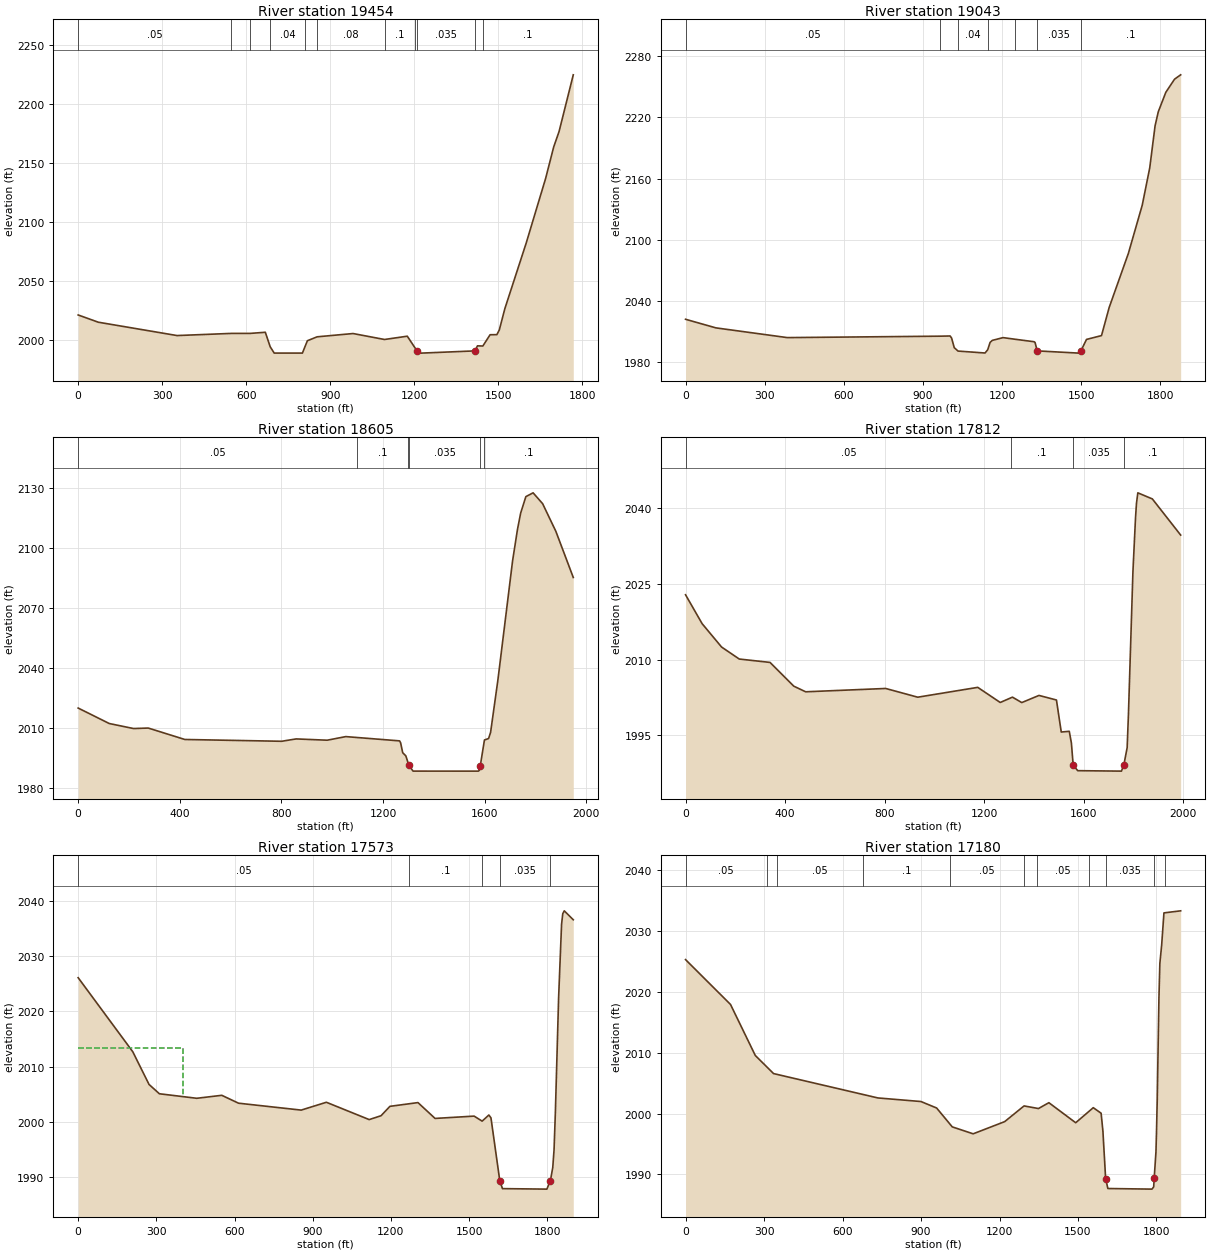
Type RM Length L Ch R = 1 ,19454   ,366.4,411,468.8
XS GIS Cut Line= 4
2190478.91473695390611.4566325782190358.11337889390588.225602181
2190088.63342628390578.9331900222188950.31293682391350.203399208
#Sta/Elev= 30
       0 2021.48      72 2015.35   353.1 2004.07   546.4 2005.89   613.5 2005.89
   668.2 2006.85   685.6 1994.61   699.9 1989.25   800.7 1989.26   808.7 1994.04
   818.4 1999.69     853    2003   981.4 2005.78  1093.8 2000.75  1175.1 2003.53
  1203.9 1993.24  1209.7 1991.37  1224.1 1989.22  1416.4 1991.11  1425.7 1995.37
  1444.9 1995.23  1470.7 2004.76  1494.8 2004.85  1503.5 2008.71  1523.6 2026.97
  1599.7 2082.33  1668.8 2136.75  1697.8 2163.52  1717.1 2176.64  1767.7  2224.5
#Mann= 11 ,-1,0
       0     .05       0   546.4      .1       0   613.5    .025       0
   685.6     .04       0   808.7    .025       0     853     .08       0
  1093.8      .1       0  1203.9    .025       0  1209.7    .035       0
  1416.4    .025       0  1444.9      .1       0
Bank Sta=1209.7,1416.4
XS Rating Curve= 0 ,0
Exp/Cntr(USF)=0,0
Exp/Cntr=0.3,0.1

Type RM Length L Ch R = 1 ,19043   ,444.8,437.7,439.3
XS GIS Cut Line= 4
2190489.11602666390600.5831902772189739.61162284390343.881893409
2189448.04965603390651.2896192882188796.78895842390768.548236376
#Sta/Elev= 30
       0 2021.94   115.2 2013.49   385.8 2003.95   965.4 2005.35  1003.5 2005.54
    1009 2003.48  1019.1 1994.07  1033.3 1990.74  1135.8 1988.84    1146 1992.07
  1154.9 1999.22  1163.4 2001.22  1204.1 2003.94  1248.1 2002.39  1321.5 1999.91
  1325.5 1999.18  1333.7 1990.92  1492.2 1988.72  1499.9 1991.19  1520.6 2002.16
  1577.5 2005.93  1606.6 2033.52  1679.4 2086.57    1732 2133.92  1760.4 2170.45
  1780.7 2211.81  1792.9 2225.61  1821.4 2244.66  1854.6 2257.56  1877.7 2261.82
#Mann= 7 ,-1,0
       0     .05       0   965.4      .1       0  1033.3     .04       0
    1146      .1       0  1248.1    .025       0  1333.7    .035       0
  1499.9      .1       0
Bank Sta=1333.7,1499.9
XS Rating Curve= 0 ,0
Exp/Cntr(USF)=0,0
Exp/Cntr=0.3,0.1

Type RM Length L Ch R = 1 ,18605   ,655.8,792.9,898.6
XS GIS Cut Line= 4
2190475.43075482390575.5070501182190245.60552904390427.119144377
2189809.86106152390132.8974063972188680.83298421 390351.26909213
#Sta/Elev= 30
       0 2019.95   122.3 2012.21   218.1 2009.69     276 2009.94     420 2004.22
   801.1 2003.32   858.1  2004.5   980.3 2003.86  1053.7 2005.66  1265.5 2003.52
  1269.6 2002.53  1277.7 1997.61    1290 1996.03  1302.2 1991.26  1318.5 1988.39
  1575.1 1988.38  1579.2 1988.68  1583.3 1991.17  1599.6 2003.96  1615.9 2004.71
  1623.8 2007.79  1652.6 2034.05  1710.3 2093.59  1729.6 2109.35  1742.2 2117.55
  1762.6 2125.77  1791.1 2127.68  1828.6 2122.26  1880.7 2108.42  1949.3 2085.32
#Mann= 6 ,-1,0
       0     .05       0 1099.34      .1       0 1299.34    .025       0
  1302.2    .035       0  1583.3    .025       0 1599.34      .1       0
Bank Sta=1302.2,1583.3
XS Rating Curve= 0 ,0
Exp/Cntr(USF)=0,0
Exp/Cntr=0.3,0.1

Type RM Length L Ch R = 1 ,17812   ,231.7,239.3,243.3
XS GIS Cut Line= 3
2190534.66920991390530.148026188 2190265.1892573390400.054255964
2189003.74430673389273.349281703
#Sta/Elev= 30
       0 2022.87    66.6 2017.14   144.9  2012.5     216 2010.12   339.6 2009.45
   435.1 2004.74   482.9 2003.62   804.7 2004.28   933.5 2002.55  1174.8  2004.5
  1265.2  2001.5  1314.3 2002.56  1351.8 2001.48    1421  2002.9  1491.2 2001.99
  1510.5 1995.64  1542.8 1995.78  1551.3 1993.46  1558.5 1989.04  1576.8 1987.97
  1752.5 1987.88 1762.24 1989.12  1775.5 1992.54  1780.7  1999.2  1798.7 2027.44
  1809.1 2038.14    1813 2041.03  1818.4  2043.1  1876.8 2041.89  1990.6 2034.72
#Mann= 4 ,-1,0
       0     .05       0 1309.24      .1       0  1558.5    .035       0
 1762.24      .1       0
Bank Sta=1558.5,1762.24
XS Rating Curve= 0 ,0
Exp/Cntr(USF)=0,0
Exp/Cntr=0.3,0.1

Type RM Length L Ch R = 1 ,17573   ,373.3,392.3,407.2
XS GIS Cut Line= 2
2190610.64421253390517.0472984232189264.39690382389176.771518855
#Sta/Elev= 30
       0 2026.09   209.6 2012.67   271.9 2006.75   311.6 2005.06     455 2004.24
     551 2004.78   615.4 2003.35   855.8  2002.1   952.3 2003.52  1116.7 2000.38
  1162.1 2001.08  1196.1 2002.78  1303.8 2003.46  1369.4 2000.59  1519.2 2001.01
    1550  2000.1  1575.9 2001.21  1583.9 2000.69  1617.71989.315    1628 1987.87
  1798.4 1987.781811.9891989.334    1821 1991.69    1826 1994.94  1831.1 2001.81
  1843.5 2022.51  1854.8 2035.77  1859.4 2037.69  1865.1 2038.21  1899.7 2036.59
#Mann= 5 ,-1,0
       0     .05       0    1270      .1       0    1550    .025       0
  1617.7    .035       01811.989      .1       0
#XS Ineff= 2 , 0
          402.46 2013.37
Permanent Ineff=
       F       F
Bank Sta=1617.7,1811.989
XS Rating Curve= 0 ,0
Exp/Cntr=0.3,0.1

Type RM Length L Ch R = 1 ,17180   ,382,366.7,355.7
XS GIS Cut Line= 4
2190709.00931269390419.0490603022190080.43764575 389574.28596458
2189610.07551633388943.7198233752189557.34130527388946.585820329
#Sta/Elev= 30
       0 2025.27   171.8 2017.91   266.6 2009.53   336.4 2006.56   735.2 2002.56
   899.8 2001.97   959.6 2000.91  1019.4 1997.81  1099.3 1996.67  1219.7 1998.67
  1293.9 2001.25  1348.8 2000.82  1388.7 2001.78  1491.2 1998.49  1558.4 2000.96
  1588.4 2000.05  1595.3 1997.09  1605.6 1989.33  1614.2 1987.69  1782.9 1987.59
  1789.3 1987.96 1791.17 1989.34  1797.9 1993.64  1799.9 1996.66  1802.9 2002.25
  1809.4 2019.02  1812.9 2024.65  1819.9 2027.72  1828.5 2032.94  1892.4 2033.28
#Mann= 11 ,-1,0
       0     .05       0     310      .1       0     350     .05       0
     680      .1       0    1010     .05       0 1292.96      .1       0
 1342.96     .05       0 1542.96      .1       0  1605.6    .035       0
 1791.17      .1       0 1832.96     .06       0
Bank Sta=1605.6,1791.17
XS Rating Curve= 0 ,0
Exp/Cntr(USF)=0,0
Exp/Cntr=0.3,0.1

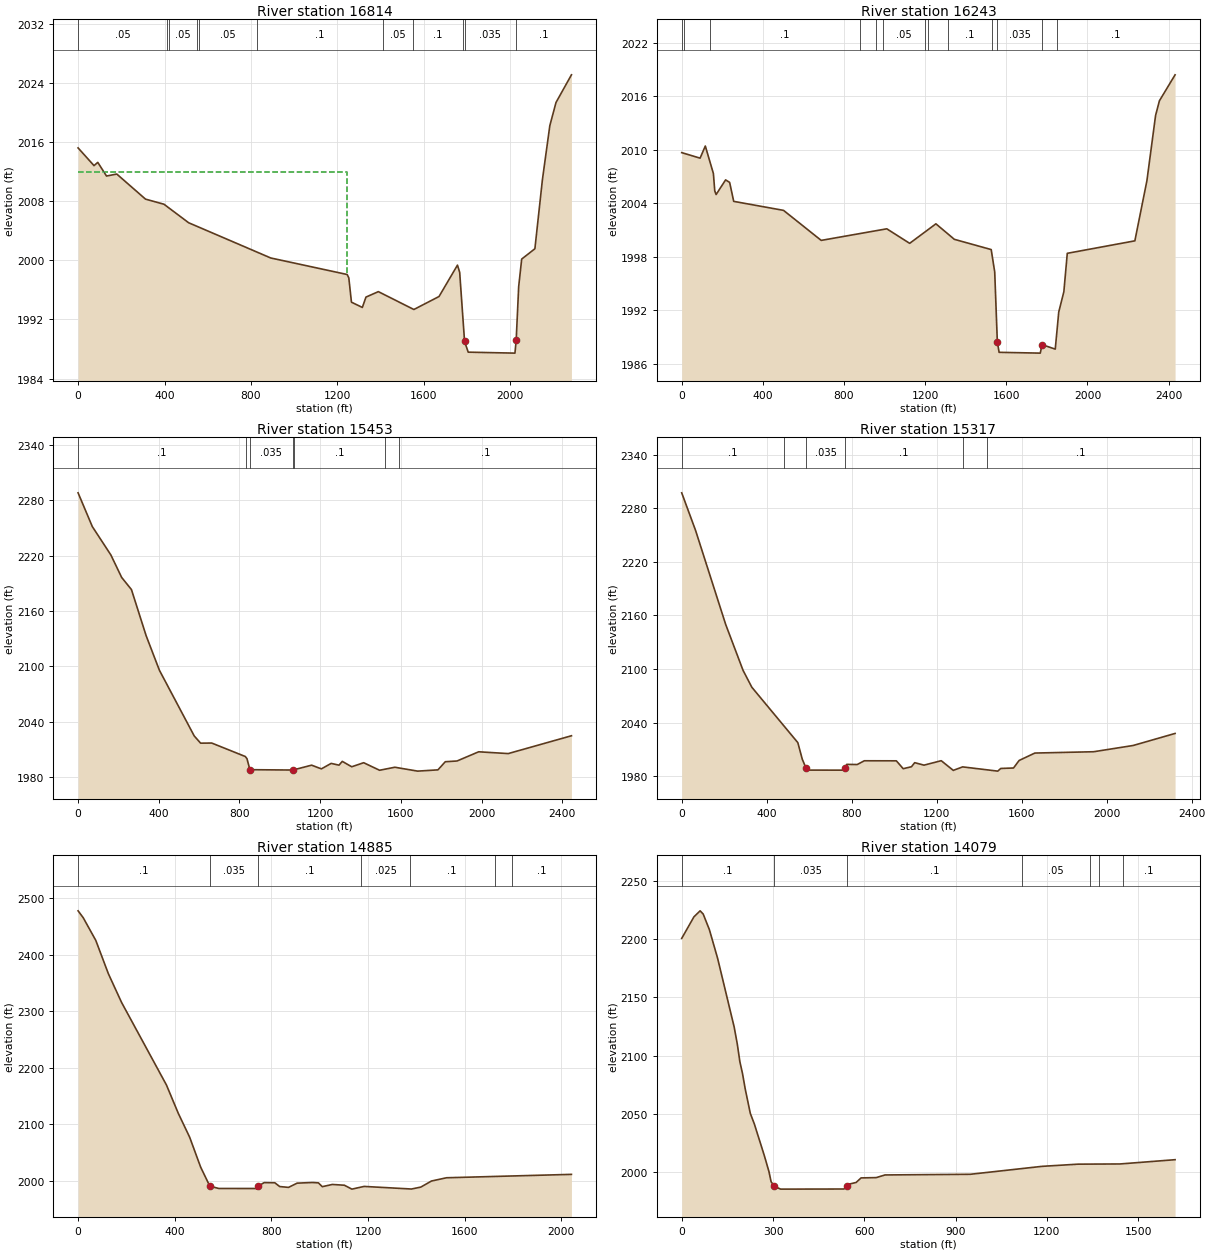
Type RM Length L Ch R = 1 ,16814   ,629.8,570.4,517.5
XS GIS Cut Line= 3
2191275.23852897390174.3827267762189802.23144054388638.626344403
2189694.48335218388749.559105326
#Sta/Elev= 30
       0 2015.24    73.7 2012.84    91.1 2013.28   131.6 2011.43     179  2011.7
     312  2008.3   397.4 2007.61   511.6  2005.1   891.3 2000.33    1245 1998.09
  1252.6 1997.63  1264.8 1994.34  1315.2 1993.63  1331.9 1995.03  1389.2 1995.77
  1553.6 1993.35    1670 1995.11  1755.3 1999.36  1765.5 1998.39  1788.1 1989.02
  1805.1 1987.57  2021.2 1987.44  2026.9 1989.16  2038.5 1996.45  2052.4 2000.18
  2113.5 2001.58  2148.3 2010.94  2182.6 2018.26  2211.3  2021.4  2282.6 2025.14
#Mann= 11 ,-1,0
       0     .05       0     410      .1       0     420     .05       0
     550      .1       0     560     .05       0     830      .1       0
    1410     .05       0    1550      .1       0    1780    .025       0
  1788.1    .035       0  2026.9      .1       0
#XS Ineff= 2 , 0
         1245.87 2011.98
Permanent Ineff=
       F       F
Bank Sta=1788.1,2026.9
XS Rating Curve= 0 ,0
Exp/Cntr(USF)=0,0
Exp/Cntr=0.3,0.1

Type RM Length L Ch R = 1 ,16243   ,919.8,790.6,680.7
XS GIS Cut Line= 4
2191689.05273727389167.1047740872190912.58827529388583.241098467
2190079.16861082388240.8283681032189727.59110451388675.750494079
#Sta/Elev= 30
       0 2009.69    90.6 2009.07   116.3 2010.43   156.2 2007.34   162.9 2005.39
   169.6 2004.99   216.3 2006.63   236.2 2006.35   256.3 2004.22   501.9 2003.21
   687.6 1999.84  1010.9 2001.14  1123.6 1999.51    1253  2001.7  1343.8 1999.96
  1525.5 1998.81  1542.8  1996.3  1555.7 1988.47  1564.4 1987.28  1767.3 1987.19
  1776.3 1988.14  1841.2 1987.64  1858.4  1991.8  1883.6 1994.08  1900.5 1998.39
  2233.6 1999.79    2293 2006.54  2335.7 2013.86  2354.5  2015.5  2431.8 2018.42
#Mann= 13 ,-1,0
       0      .1       0      10     .07       0     140      .1       0
     880     .05       0     960      .1       0  991.49     .05       0
 1201.49      .1       0 1211.49     .05       0 1311.49      .1       0
 1531.49    .025       0  1555.7    .035       0  1776.3    .025       0
 1851.49      .1       0
Bank Sta=1555.7,1776.3
XS Rating Curve= 0 ,0
Exp/Cntr(USF)=0,0
Exp/Cntr=0.3,0.1

Type RM Length L Ch R = 1 ,15453   ,131.1,136,142.8
XS GIS Cut Line= 4
2191278.21114261387018.6549204192190200.98569344387758.689497043
2190156.96916737 387853.741627322189665.74914258388763.513455166
#Sta/Elev= 30
       0 2287.92    70.4 2251.46   162.6 2220.67     216 2196.37   264.5 2183.24
   337.3 2133.36   403.1 2095.93   575.7 2024.84   607.4 2017.02   662.5 2017.15
   828.9 2002.58   837.2 2000.21   851.7 1988.32  1064.8 1987.94  1157.5  1993.2
    1206 1989.21  1254.5 1995.11  1293.4 1993.22  1309.7  1997.3  1356.5 1991.47
  1415.6 1995.86  1494.5  1987.7  1570.1 1990.96  1683.4 1986.76  1783.8 1988.13
  1820.2 1996.93  1878.3 1997.72  1985.9 2007.69  2132.1 2005.74  2445.6 2025.03
#Mann= 7 ,-1,0
       0      .1       0     830    .025       0   851.7    .035       0
  1064.8    .025       0    1070      .1       0 1521.68    .025       0
 1591.68      .1       0
Bank Sta=851.7,1064.8
XS Rating Curve= 0 ,0
Exp/Cntr(USF)=0,0
Exp/Cntr=0.3,0.1

Type RM Length L Ch R = 1 ,15317   ,545.8,431.5,332.1
XS GIS Cut Line= 4
2190912.58827528386968.0867099612190592.78770636387333.111601763
2190150.23540391387623.8393916942189629.06193782388822.308404064
#Sta/Elev= 30
       0  2297.3    65.3 2255.16     207 2149.92   288.6 2098.61   329.9 2079.68
   546.4 2017.64   567.4 1999.07     584 1989.69   595.6 1986.88   758.8 1986.83
   768.9 1989.77   776.8  1993.3   825.8 1993.12   859.3 1997.33    1010 1997.27
  1042.4 1988.46  1081.2 1990.66  1096.4  1995.2  1140.3 1992.44  1221.3 1997.42
    1278 1986.58  1322.1 1990.48  1487.3 1985.74  1501.4 1988.72  1561.4 1989.24
  1587.7 1997.64  1661.8 2005.97  1938.5 2007.45  2124.2 2014.43  2321.7 2027.92
#Mann= 6 ,-1,0
       0      .1       0     480    .025       0     584    .035       0
   768.9      .1       0  1324.8    .025       0  1434.8      .1       0
Bank Sta=584,768.9
XS Rating Curve= 0 ,0
Exp/Cntr(USF)=0,0
Exp/Cntr=0.3,0.1

Type RM Length L Ch R = 1 ,14885   ,898.6,806.5,718.5
XS GIS Cut Line= 4
2190063.82575538386647.9307297662190014.39063719387649.125056567
2189846.44193172388268.7160796552189656.38775727 388617.80674605
#Sta/Elev= 30
       0 2477.78    21.3 2465.58    73.3 2425.49   125.4 2366.49   180.2 2315.58
   365.7 2169.72   414.5 2119.82   461.8 2077.36   507.2 2024.52545.10841990.916
     582 1986.66   738.1 1986.62746.3842 1991.21   770.2 1997.04   814.2  1996.8
   834.3  1990.1     871  1988.6   906.4  1996.1   970.6 1997.27   994.5 1996.61
  1010.7 1989.85  1052.2 1993.78  1101.9 1992.44  1133.2 1985.53  1183.6 1990.32
  1379.6 1985.73  1418.4 1989.13  1462.5 1999.87  1524.7 2005.63  2041.8 2011.63
#Mann= 7 ,-1,0
       0      .1       0545.1084    .035       0746.3842      .1       0
 1172.41    .025       0 1372.41      .1       0 1724.36     .05       0
 1794.36      .1       0
Bank Sta=545.1084,746.3842
XS Rating Curve= 0 ,0
Exp/Cntr(USF)=0,0
Exp/Cntr=0.3,0.1

Type RM Length L Ch R = 1 ,14079   ,492.6,484.1,479.1
XS GIS Cut Line= 4
     2189047.232      387289.6272189434.68441153  387783.2436173
2189755.30937987388341.1560085662189597.17072381388653.387246505
#Sta/Elev= 30
       0 2200.56    40.2 2219.05    60.5  2224.2    70.6 2221.43      91 2207.98
   118.1  2183.3   172.3 2124.55   182.5 2110.04   191.2 2094.57   199.8 2084.52
   208.8 2071.14   225.4 2050.35   238.4 2041.46     271 2014.49   286.6 2000.43
   293.8 1991.63   304.5 1987.82   324.9 1985.34   533.1 1985.44   544.51987.919
   552.2 1989.78     573 1991.06   589.3 1994.97     639 1995.22   668.1 1997.51
   948.1 1998.08  1184.4  2004.9  1302.4 2006.77    1440 2006.94    1621  2010.6
#Mann= 7 ,-1,0
       0      .1       0   304.5    .035       0   544.5      .1       0
 1117.52     .05       0    1341      .1       0    1371     .05       0
    1451      .1       0
Bank Sta=304.5,544.5
XS Rating Curve= 0 ,0
Exp/Cntr=0.3,0.1

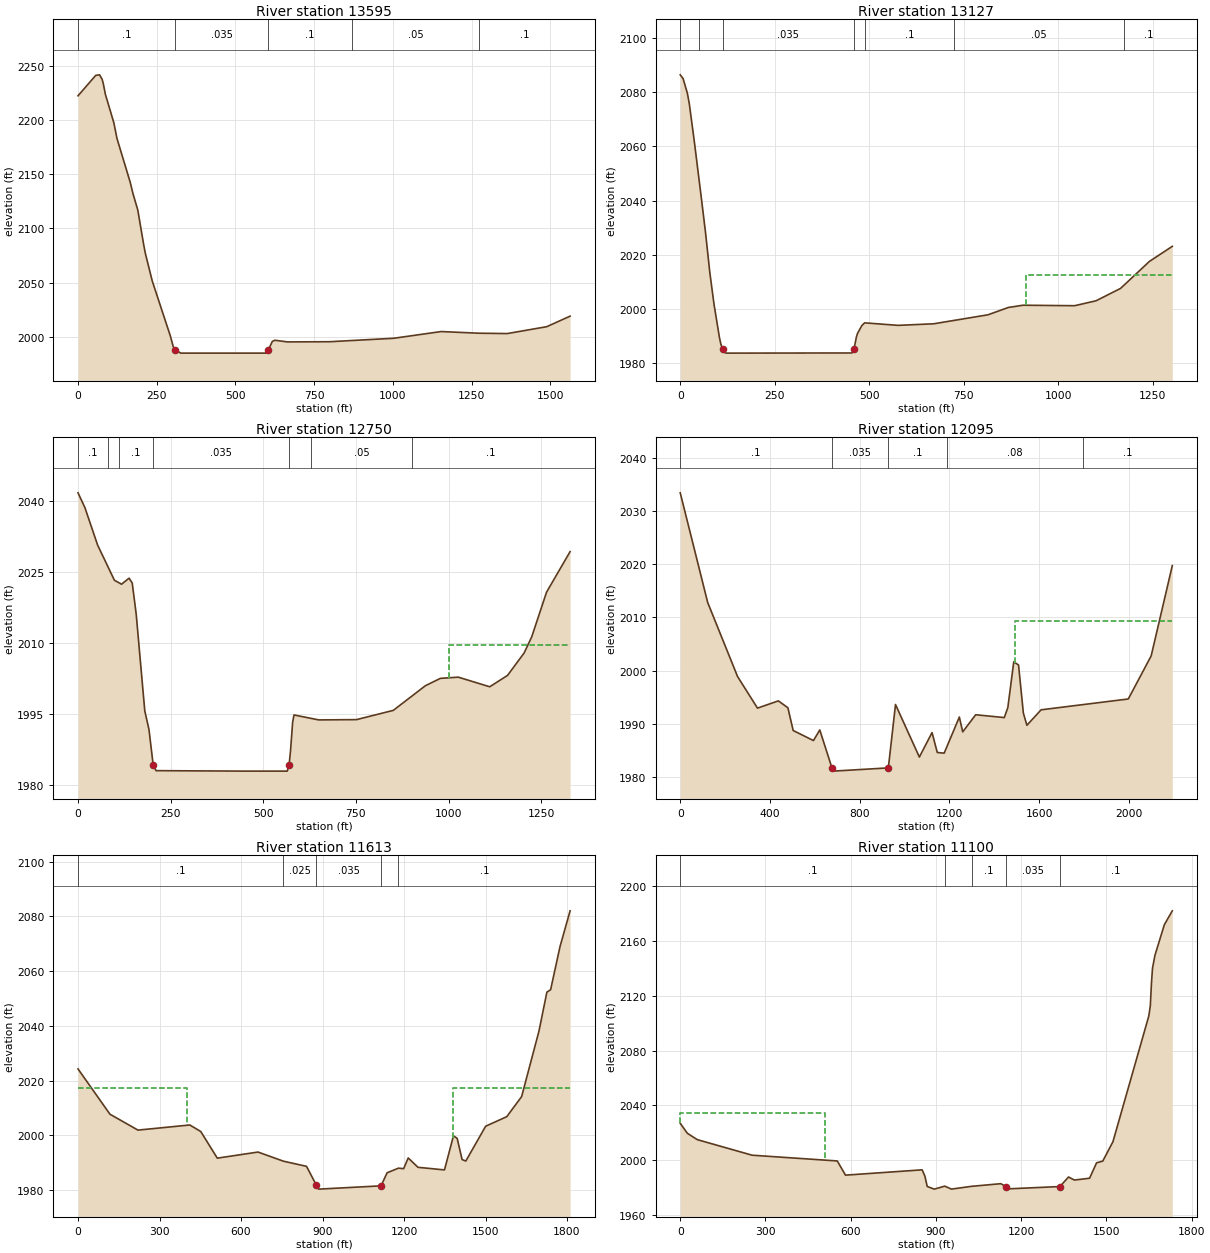
Type RM Length L Ch R = 1 ,13595   ,486.8,467.2,447.8
XS GIS Cut Line= 4
     2188651.221      387607.6182189177.16907284388208.738756997
2189391.71983624388466.5043632022189333.29016893388890.808363725
#Sta/Elev= 30
       0 2222.56    56.1  2241.4    68.3 2241.93    76.5 2237.87    80.4 2233.64
    86.8    2224   113.7 2197.69   123.7 2183.18   165.5 2142.92   174.7 2131.98
   189.8 2117.06   208.7 2084.67   214.1 2076.61   235.9  2051.3     293 2000.86
   302.3 1990.91308.58561987.875   326.3 1984.84   597.1 1984.85604.35581987.802
   616.9 1995.69   625.4 1996.73   665.1 1995.21   798.7 1995.37  1002.3 1998.56
    1153 2004.77  1274.1 2003.22  1363.2 2002.92  1488.1 2009.25  1562.4 2018.99
#Mann= 5 ,-1,0
       0      .1       0308.5856    .035       0604.3558      .1       0
  868.73     .05       0  1274.1      .1       0
Bank Sta=308.5856,604.3558
XS Rating Curve= 0 ,0
Exp/Cntr=0.3,0.1

Type RM Length L Ch R = 1 ,13127   ,364.6,377.7,389.4
XS GIS Cut Line= 4
2188398.60292985388072.1001879162188804.50825263388448.597994149
2189210.74020053388835.229228481 2189231.0369821389021.283059586
#Sta/Elev= 30
       0 2086.43     7.6 2085.03    18.9 2079.64      24 2075.76    36.9 2062.24
    55.7 2041.16      67 2028.12    78.3 2013.48    89.4 2001.75   103.8 1989.46
   107.5 1987.06112.29271985.273   116.7 1984.06   122.2 1983.78   454.5 1983.84
   459.91985.419   465.9 1989.69   468.9 1991.02   480.2  1993.9   487.7 1994.95
   576.4 1994.02   670.5  1994.6   814.1 1997.92   867.9 2000.62   906.6 2001.45
  1043.3 2001.27  1099.9 2003.09  1164.6 2007.64  1241.1 2017.61  1301.6 2023.17
#Mann= 7 ,-1,0
       0      .1       0      50    .025       0112.2927    .035       0
   459.9    .025       0     490      .1       0  723.63     .05       0
 1174.44      .1       0
#XS Ineff= 2 , 0
                          914.93         2012.71
Permanent Ineff=
       F       F
Bank Sta=112.2927,459.9
XS Rating Curve= 0 ,0
Exp/Cntr(USF)=0,0
Exp/Cntr=0.3,0.1

Type RM Length L Ch R = 1 ,12750   ,631.5,655,685.1
XS GIS Cut Line= 2
2188067.35483847388243.2397658762188980.71000934 389207.33689069
#Sta/Elev= 30
       0  2041.8    18.6 2038.67    52.9 2030.73    98.2 2023.28   117.5 2022.44
   137.8 2023.72   146.3  2022.7     157 2016.12   180.2  1995.6   191.5 1991.66
   202.8 1984.19   210.6 1982.94     449 1982.84   564.7 1982.84   569.8 1984.23
   573.5 1987.14   579.2 1993.17   582.8 1994.74   649.9 1993.69   751.5 1993.75
   850.8 1995.71   937.6 2000.94   977.9 2002.49  1026.2 2002.75  1111.1 2000.71
  1159.2 2003.12  1203.9 2007.87  1224.3 2011.26  1264.5 2020.76    1328 2029.34
#Mann= 7 ,-1,0
       0      .1       0      80     .12       0     110      .1       0
   202.8    .035       0   569.8      .1       0     630     .05       0
     900      .1       0
#XS Ineff= 2 , 0
                         1002.48         2009.55
Permanent Ineff=
       F       F
Bank Sta=202.8,569.8
XS Rating Curve= 0 ,0
Exp/Cntr(USF)=0,0
Exp/Cntr=0.3,0.1

Type RM Length L Ch R = 1 ,12095   ,418.4,482.2,526.1
XS GIS Cut Line= 4
2187645.95694832388251.8743110732187708.08857963388710.933890823
2188143.47026419389422.9712576922188733.41063055390096.880642002
#Sta/Elev= 30
       0 2033.46   122.4 2012.82   255.6 1998.88   344.4 1992.94   437.3  1994.3
   479.9 1993.01   503.4 1988.73   593.8 1986.83   622.1 1988.83675.7002 1981.76
   681.5 1981.08927.66891981.689   959.6 1993.62    1066 1983.73  1122.5 1988.34
  1145.8 1984.59  1176.5 1984.46  1244.2 1991.26  1259.2 1988.47  1317.1 1991.69
  1444.5 1991.16  1460.3 1993.03  1486.8 2001.66  1508.1 2001.05  1529.5 1992.02
  1545.3 1989.71  1608.6 1992.62  1997.3 1994.66  2099.3 2002.77  2193.5 2019.76
#Mann= 5 ,-1,0
       0      .1       0675.7002    .035       0927.6689      .1       0
 1190.13     .08       0 1794.73      .1       0
#XS Ineff= 2 , 0
                         1494.37          2009.4
Permanent Ineff=
       F       F
Bank Sta=675.7002,927.6689
XS Rating Curve= 0 ,0
Exp/Cntr=0.3,0.1

Type RM Length L Ch R = 1 ,11613   ,445.9,512.4,547.2
XS GIS Cut Line= 5
2187552.44048875388213.3678002292187331.31380301388520.793037209
2187370.59208724388774.452476313 2187499.9407139389505.623025696
2187291.05753582389885.444981755
#Sta/Elev= 30
       0 2024.24   117.6 2007.68   220.7 2001.87   411.6 2003.74   451.9 2001.35
   512.7 1991.61   662.5 1993.84   755.9 1990.51   841.2 1988.61877.78391981.666
   885.9 1980.28  1115.4 1981.48  1137.8 1986.26  1179.7 1987.95  1198.7 1987.76
  1215.5 1991.68  1251.5 1988.26    1349 1987.31    1382 1999.75  1395.7 1998.86
  1413.9 1991.09  1427.5 1990.55  1500.6 2003.29  1578.3 2006.78    1633 2014.13
  1696.9 2038.11    1726 2052.34  1739.7 2053.21  1774.5 2069.07  1811.4 2082.07
#Mann= 5 ,-1,0
       0      .1       0   755.9    .025       0877.7839    .035       0
  1115.4    .025       0  1179.7      .1       0
#XS Ineff= 2 , 0
             400 2017.24 1380.28         2017.39
Permanent Ineff=
       F       F
Bank Sta=877.7839,1115.4
XS Rating Curve= 0 ,0
Exp/Cntr=0.3,0.1

Type RM Length L Ch R = 1 ,11100   ,424.1,497,551.9
XS GIS Cut Line= 3
2187503.20371039388107.2569323322187106.25804023388448.867999621
2186827.72643754389624.568950034
#Sta/Elev= 30
       0    2027    25.1 2019.67    60.2 2015.03   253.1 2003.69   552.8 1999.49
   581.6 1989.14   851.4 1993.01   861.1 1988.42   869.3 1980.88     894 1978.94
     931 1981.11   954.4 1978.96  1025.5 1980.98  1128.3 1982.911146.5861980.768
    1153 1979.131336.2951980.824  1366.7 1987.78  1387.3 1985.56  1440.7 1986.89
  1465.4 1998.16  1487.1 1999.36  1522.9 2013.51    1649 2105.09  1654.5 2112.65
  1658.6 2129.54  1662.3 2140.31  1670.9 2149.61  1703.8 2171.83  1731.9 2181.99
#Mann= 5 ,-1,0
       0      .1       0     931     .04       0  1025.5      .1       0
1146.586    .035       01336.295      .1       0
#XS Ineff= 2 , 0
           511.1 2034.48
Permanent Ineff=
       F       F
Bank Sta=1146.586,1336.295
XS Rating Curve= 0 ,0
Exp/Cntr=0.3,0.1

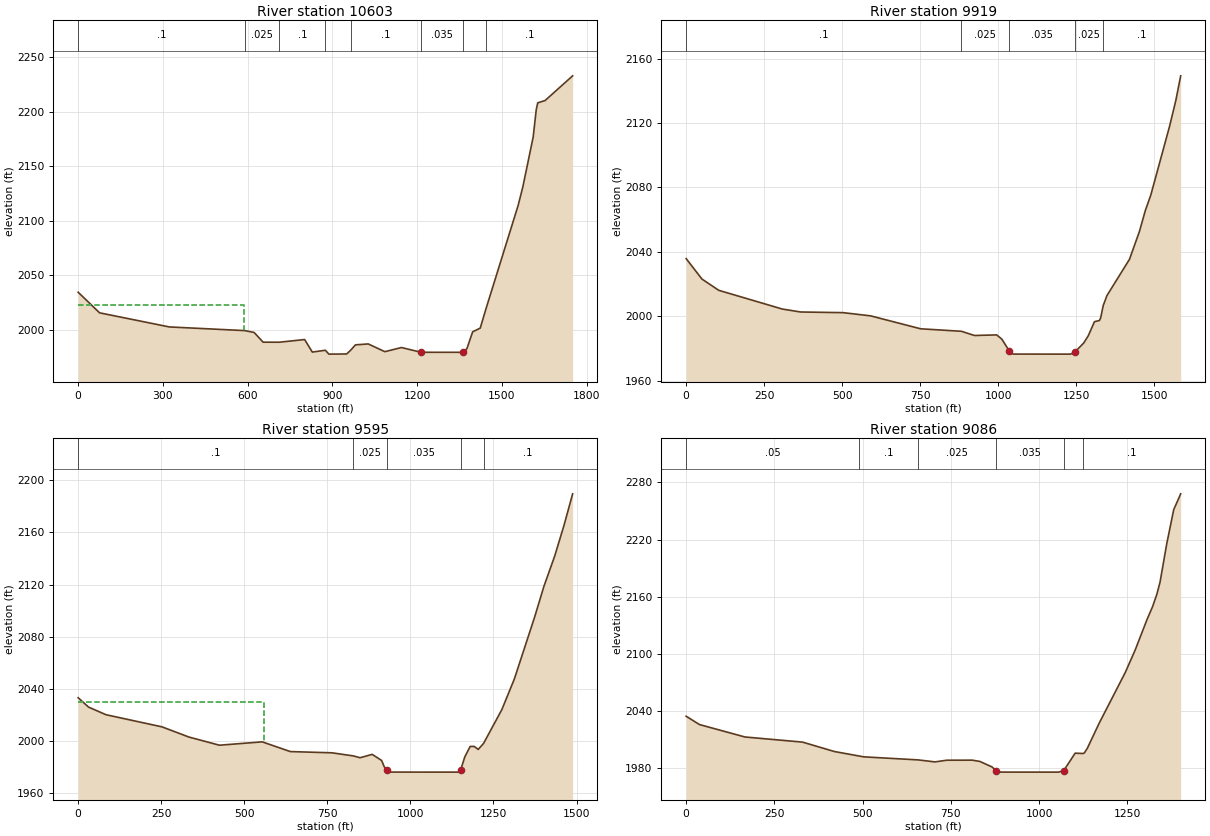
Type RM Length L Ch R = 1 ,10603   ,588.8,684.4,748.3
XS GIS Cut Line= 3
2187511.36488084388075.0552548132186925.26493143388546.128912254
      2186179.98      389210.047
#Sta/Elev= 30
       0 2034.36    75.9 2015.45   322.6  2002.5   589.1 1999.13   622.7 1997.45
   654.7 1988.49   712.1 1988.47   801.6 1990.92   828.7 1979.42   875.1 1981.08
   887.3 1977.53   950.4 1977.67   964.5 1981.12   981.5 1986.04  1026.6 1986.88
  1085.5  1979.8  1144.5 1983.581213.5321979.2241360.9231979.195  1375.9 1982.56
  1396.2    1998    1423 2001.41  1444.5 2020.11    1557 2113.86  1573.7 2130.92
  1610.5 2176.96  1621.2 2201.87  1626.6 2208.23  1652.5 2210.33  1750.1 2233.02
#Mann= 8 ,-1,0
       0      .1       0   589.1    .025       0   712.1      .1       0
   875.1     .04       0   964.5      .1       01213.532    .035       0
1360.923    .025       0  1444.5      .1       0
#XS Ineff= 2 , 0
          586.01 2022.29
Permanent Ineff=
       F       F
Bank Sta=1213.532,1360.923
XS Rating Curve= 0 ,0
Exp/Cntr=0.3,0.1

Type RM Length L Ch R = 1 ,9919    ,315.3,323.3,338.5
XS GIS Cut Line= 3
2187486.44424067388030.1802517872187027.37251513388298.057436935
2185976.33890134388240.053374363
#Sta/Elev= 30
       0 2035.78    50.6 2023.07   104.5 2016.07     308 2004.44   366.5 2002.61
   502.8  2002.2   590.8 2000.21     751 1992.17   881.7 1990.62   923.3 1988.01
   994.8 1988.36  1011.4 1985.691035.4531978.243    1047 1976.45  1231.8 1976.42
1246.3531977.959  1273.4 1983.32  1287.9 1987.77  1307.9 1996.58  1323.9 1997.33
  1327.9 1999.04  1335.9 2006.58  1347.8 2012.78  1420.1 2035.36  1452.1 2052.75
    1471 2065.79  1488.2 2075.19  1548.3 2117.89  1568.6 2134.15  1584.1  2149.4
#Mann= 5 ,-1,0
       0      .1       0   881.7    .025       01035.453    .035       0
1246.353    .025       0  1335.9      .1       0
Bank Sta=1035.453,1246.353
XS Rating Curve= 0 ,0
Exp/Cntr(USF)=0,0
Exp/Cntr=0.3,0.1

Type RM Length L Ch R = 1 ,9595    ,486.4,509.2,541.8
XS GIS Cut Line= 3
2187427.60295577387958.3968431972186894.38417048388008.567023007
     2185950.621      387877.311
#Sta/Elev= 30
       0 2033.22    31.6 2026.02    83.8 2020.22   252.5  2010.9   333.3 2003.11
   425.3 1996.83     554  1999.4   638.8 1991.95     764    1991   827.7 1988.65
   848.8 1987.23   885.1 1989.81   913.4 1985.13   921.5 1980.21930.35251978.075
   941.7 1976.22  1143.6 1976.191151.6511978.148  1163.8 1987.87  1179.9 1995.87
    1192 1995.91  1204.2  1993.6  1220.3 1998.22  1275.4 2024.19  1312.9 2047.59
  1373.8 2094.95    1402 2118.71  1434.4 2141.89  1462.6 2165.63  1488.4  2189.6
#Mann= 5 ,-1,0
       0      .1       0   827.7    .025       0930.3525    .035       0
1151.651    .025       0  1220.3      .1       0
#XS Ineff= 2 , 0
          558.73 2030.11
Permanent Ineff=
       F       F
Bank Sta=930.3525,1151.651
XS Rating Curve= 0 ,0
Exp/Cntr=0.3,0.1

Type RM Length L Ch R = 1 ,9086    ,479.2,494.3,516.3
XS GIS Cut Line= 2
2187399.49551742387789.314830813     2186093.693      387280.308
#Sta/Elev= 30
       0 2034.47    37.9 2025.71   166.7 2012.68   329.8 2007.31     420 1997.42
   503.1 1991.83   657.5 1988.62   705.2 1986.52   738.3 1988.29   810.7 1988.35
   832.1 1987.04   866.5 1981.28879.08811977.309     888 1975.81  1055.4 1975.78
1069.9881977.354  1102.4  1995.7  1124.3 1995.34  1128.4 1995.87    1137 2000.87
  1170.3 2027.02  1244.3 2080.33  1272.3 2103.83  1306.2 2136.18  1321.6 2149.37
    1334 2162.64    1343 2175.36  1361.8 2215.24  1381.7 2251.42  1401.5 2268.08
#Mann= 6 ,-1,0
       0     .05       0     490      .1       0   657.5    .025       0
879.0881    .035       01069.988     .05       0  1124.3      .1       0
Bank Sta=879.0881,1069.988
XS Rating Curve= 0 ,0
Exp/Cntr=0.3,0.1