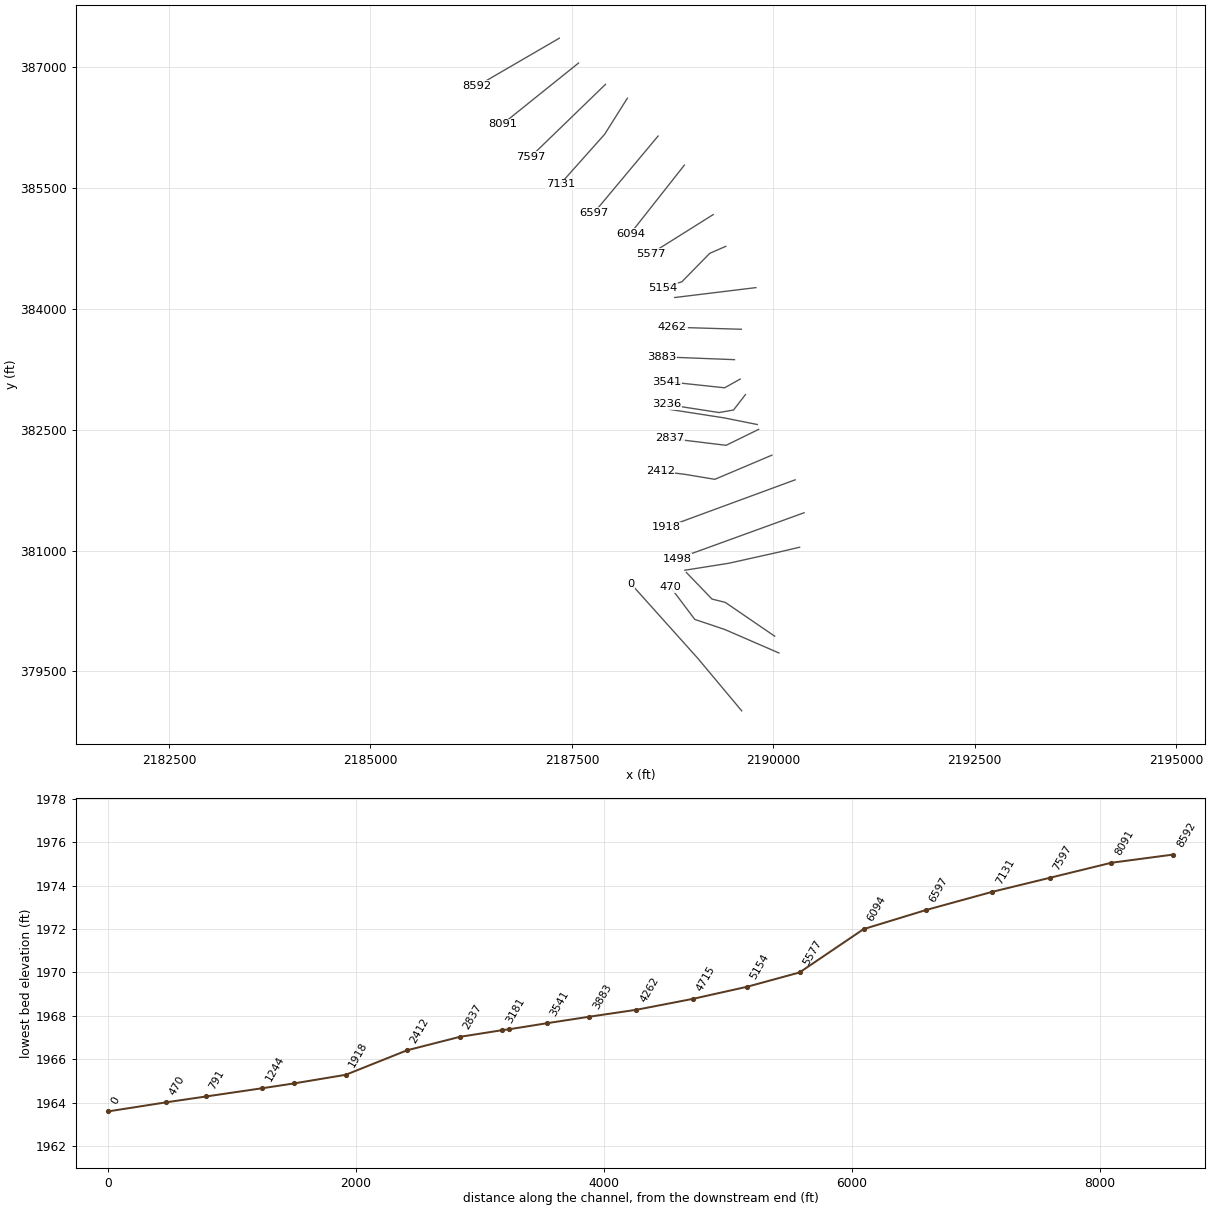
HEC-RAS study GRNBRRRV.prj: GRNBRRRV

--- GRNBRRRV.g01 (geometry) --- (continued)

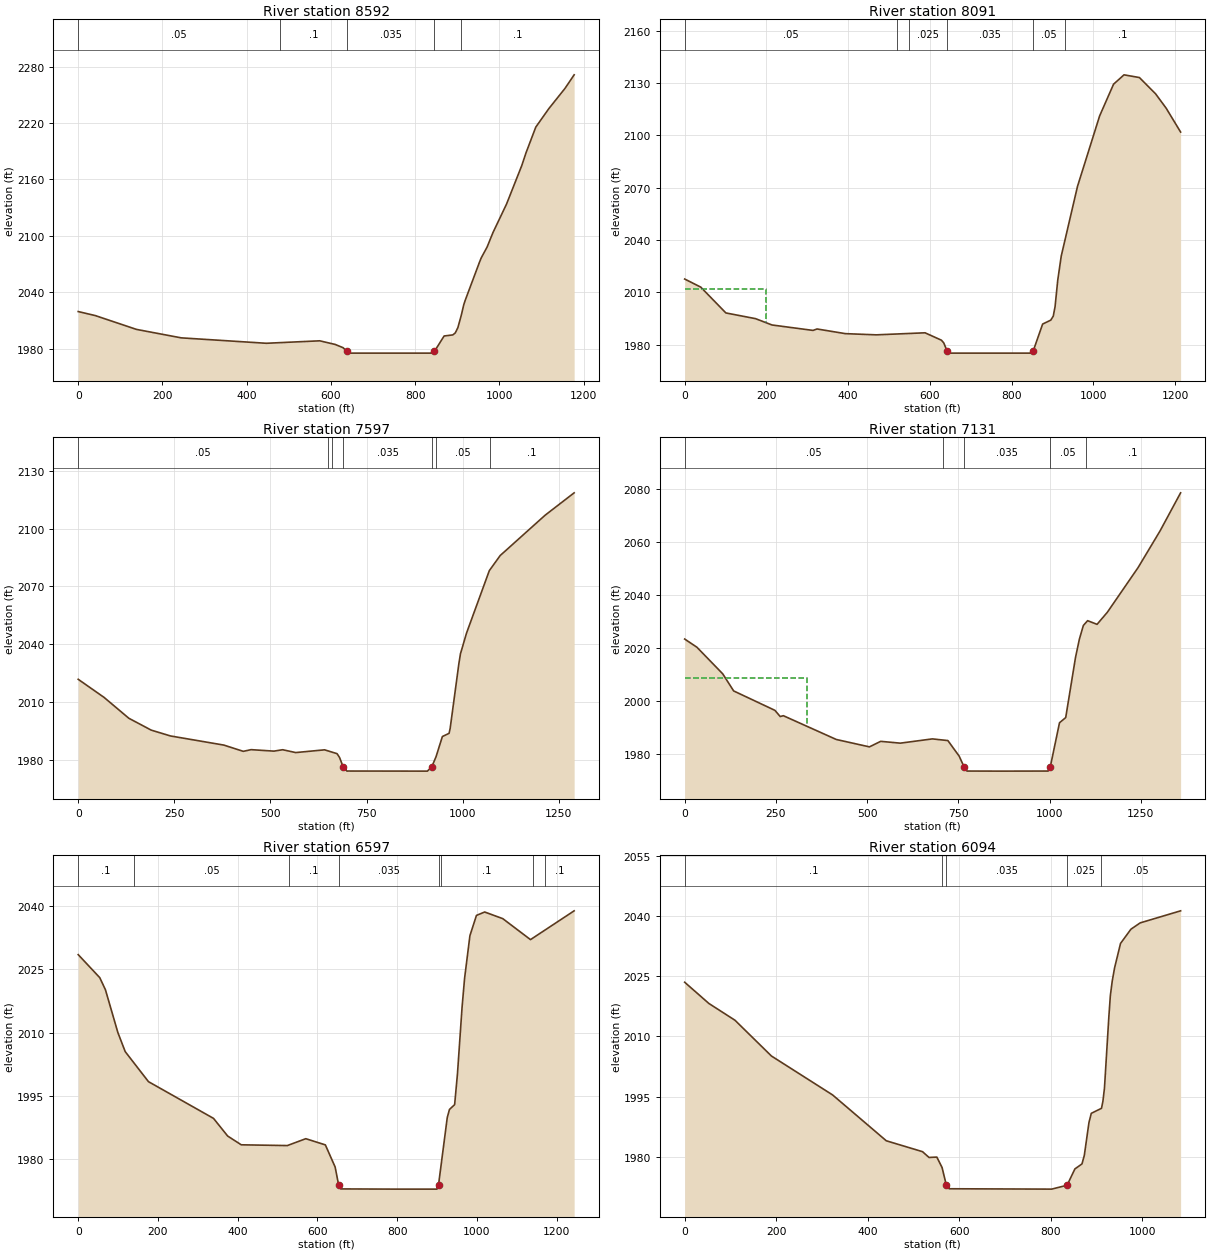
Type RM Length L Ch R = 1 ,8592    ,483.1,501,520.3
XS GIS Cut Line= 2
2187343.71407971387357.679796497     2186325.461       386765.81
#Sta/Elev= 30
       0 2019.63    40.8 2015.32   138.3 2000.67   244.7 1991.67   446.7 1985.91
   573.5 1988.53   610.2 1984.68   628.7 1981.29   638.2 1977.45   646.7 1975.44
   836.9 1975.44   846.1 1977.38     869 1993.66   889.5  1994.8   895.4 1996.88
   901.7 2002.57     910 2016.08   915.5 2026.66   918.8 2031.23   952.6 2071.65
   957.2 2076.74   971.1 2088.24   984.9 2103.47  1017.3 2133.95  1053.4  2174.8
  1063.6 2188.48  1086.7 2215.69  1117.7 2235.33  1156.1 2256.87  1177.8 2271.25
#Mann= 5 ,-1,0
       0     .05       0     480      .1       0   638.2    .035       0
   846.1     .05       0     910      .1       0
Bank Sta=638.2,846.1
XS Rating Curve= 0 ,0
Exp/Cntr=0.3,0.1

Type RM Length L Ch R = 1 ,8091    ,480.4,493.6,503.8
XS GIS Cut Line= 2
2187582.79064387387049.764284344     2186636.586      386290.077
#Sta/Elev= 30
       0 2017.58    39.3 2012.94   100.8 1998.12   173.4 1994.84   213.7 1991.21
     314 1988.09   323.8 1988.92   393.2 1986.24   468.9 1985.55   588.1 1986.72
   628.2 1982.48   633.9 1980.92   642.5 1976.01     651 1975.06   844.6 1975.06
     853 1976.47   875.8 1991.74   895.7 1993.98   901.8 1996.28   906.2 2001.67
   912.8 2016.96   921.3 2030.72   961.1 2070.73  1015.2 2111.13  1049.3 2129.36
  1074.9 2134.74  1112.6 2133.18  1152.4 2123.77  1178.1 2115.57  1213.4 2101.91
#Mann= 6 ,-1,0
       0     .05       0     520      .1       0     550    .025       0
   642.5    .035       0     853     .05       0     930      .1       0
#XS Ineff= 2 , 0
             200 2012.04
Permanent Ineff=
       F       F
Bank Sta=642.5,853
XS Rating Curve= 0 ,0
Exp/Cntr=0.3,0.1

Type RM Length L Ch R = 1 ,7597    ,454,466.1,474.2
XS GIS Cut Line= 2
2187916.54631091386784.747592994     2186989.984      385887.496
#Sta/Elev= 30
       0 2021.93    67.3 2012.55   131.6 2001.76   189.8 1995.61   239.9 1992.59
   378.9 1987.85   429.3 1984.62   449.7 1985.49   509.1 1984.73   531.8 1985.45
   565.7 1983.98   640.8  1985.4   673.2 1983.41   679.8  1981.4   689.4 1976.39
   698.7 1974.42     908 1974.37   919.3 1976.48   919.3  1976.5   930.6 1981.82
   947.1 1992.29   964.6 1993.95   967.4  1996.6     990 2030.04   994.1 2035.12
  1009.8  2045.8  1069.2 2078.22  1097.5 2086.04  1214.4 2106.93  1289.8 2118.51
#Mann= 7 ,-1,0
       0     .05       0     650      .1       0     660    .025       0
   689.4    .035       0   919.3    .025       0     930     .05       0
    1070      .1       0
Bank Sta=689.4,919.3
XS Rating Curve= 0 ,0
Exp/Cntr=0.3,0.1

Type RM Length L Ch R = 1 ,7131    ,529.9,534.8,539
XS GIS Cut Line= 3
2188188.84513058386613.5209536522187907.10938547386166.358062396
2187354.64733296385546.146538723
#Sta/Elev= 30
       0 2023.39    33.5 2020.32   104.4 2010.29   134.2 2003.88   247.3 1996.58
   261.8 1994.25   270.5 1994.56   415.5 1985.62   506.3 1982.84   537.1 1984.92
   590.9 1984.24   678.8 1985.84   721.3 1985.21   752.2 1979.37   765.8 1975.29
   773.5 1973.75   867.6 1973.72   996.1 1973.75  1001.7 1975.18  1027.2 1991.91
  1044.2 1993.86  1071.1 2016.51  1081.8 2023.42  1092.6  2028.5  1104.2  2030.3
  1130.1 2028.92  1158.4 2033.48  1242.6 2050.28  1302.7 2064.04  1359.1 2078.38
#Mann= 5 ,-1,0
       0     .05       0  708.52      .1       0   765.8    .035       0
  1001.7     .05       0 1098.52      .1       0
#XS Ineff= 2 , 0
          335.56 2008.62
Permanent Ineff=
       F       F
Bank Sta=765.8,1001.7
XS Rating Curve= 0 ,0
Exp/Cntr=0.3,0.1

Type RM Length L Ch R = 1 ,6597    ,497.8,502.8,506.3
XS GIS Cut Line= 2
2188569.82954099386143.669464673      2187771.92      385189.205
#Sta/Elev= 30
       0 2028.49    54.1 2023.03    68.3 2020.16    99.5 2010.01   117.9 2005.49
   176.2 1998.37   339.4 1989.66   374.9 1985.47     409 1983.39   524.6 1983.21
   570.9 1984.84     620 1983.37   644.5 1978.13   653.2 1973.91   658.9 1972.93
   794.6 1972.88     900 1972.88  903.881973.891   925.8 1989.86   931.3 1991.77
   944.3 1992.92   951.4 2000.26     963 2016.09   969.2 2022.84   982.6 2032.98
     999 2037.79  1019.6  2038.6    1065 2037.03  1134.6 2032.05  1244.1 2038.88
#Mann= 8 ,-1,0
       0      .1       0     140     .05       0     530      .1       0
   653.2    .035       0  903.88     .12       0     910      .1       0
    1140     .08       0    1170      .1       0
Bank Sta=653.2,903.88
XS Rating Curve= 0 ,0
Exp/Cntr=0.3,0.1

Type RM Length L Ch R = 1 ,6094    ,562,516.7,429.2
XS GIS Cut Line= 2
2188896.26979376 385783.363644242188225.07441499384931.733776977
#Sta/Elev= 30
       0 2023.48    52.9  2018.2   109.9 2014.03   189.6 2005.13   323.5 1995.43
   440.8 1984.03     520 1981.32   534.2 1979.88   551.3 1979.97   562.7  1977.4
571.88451973.083   578.3 1972.09   802.4    1972   836.1 1972.97   853.2 1977.03
   868.6 1978.27   873.7 1980.36   883.9 1988.56     889 1990.86   911.3 1992.11
   914.4 1993.85   917.8 1997.12   927.3 2014.71   930.7 2020.16   934.8 2023.78
   939.9 2027.04   952.9 2033.13   975.7 2036.68   995.9 2038.25  1084.3 2041.25
#Mann= 5 ,-1,0
       0      .1       0   562.7    .025       0571.8845    .035       0
   836.1    .025       0   911.3     .05       0
Bank Sta=571.8845,836.1
XS Rating Curve= 0 ,0
Exp/Cntr=0.3,0.1

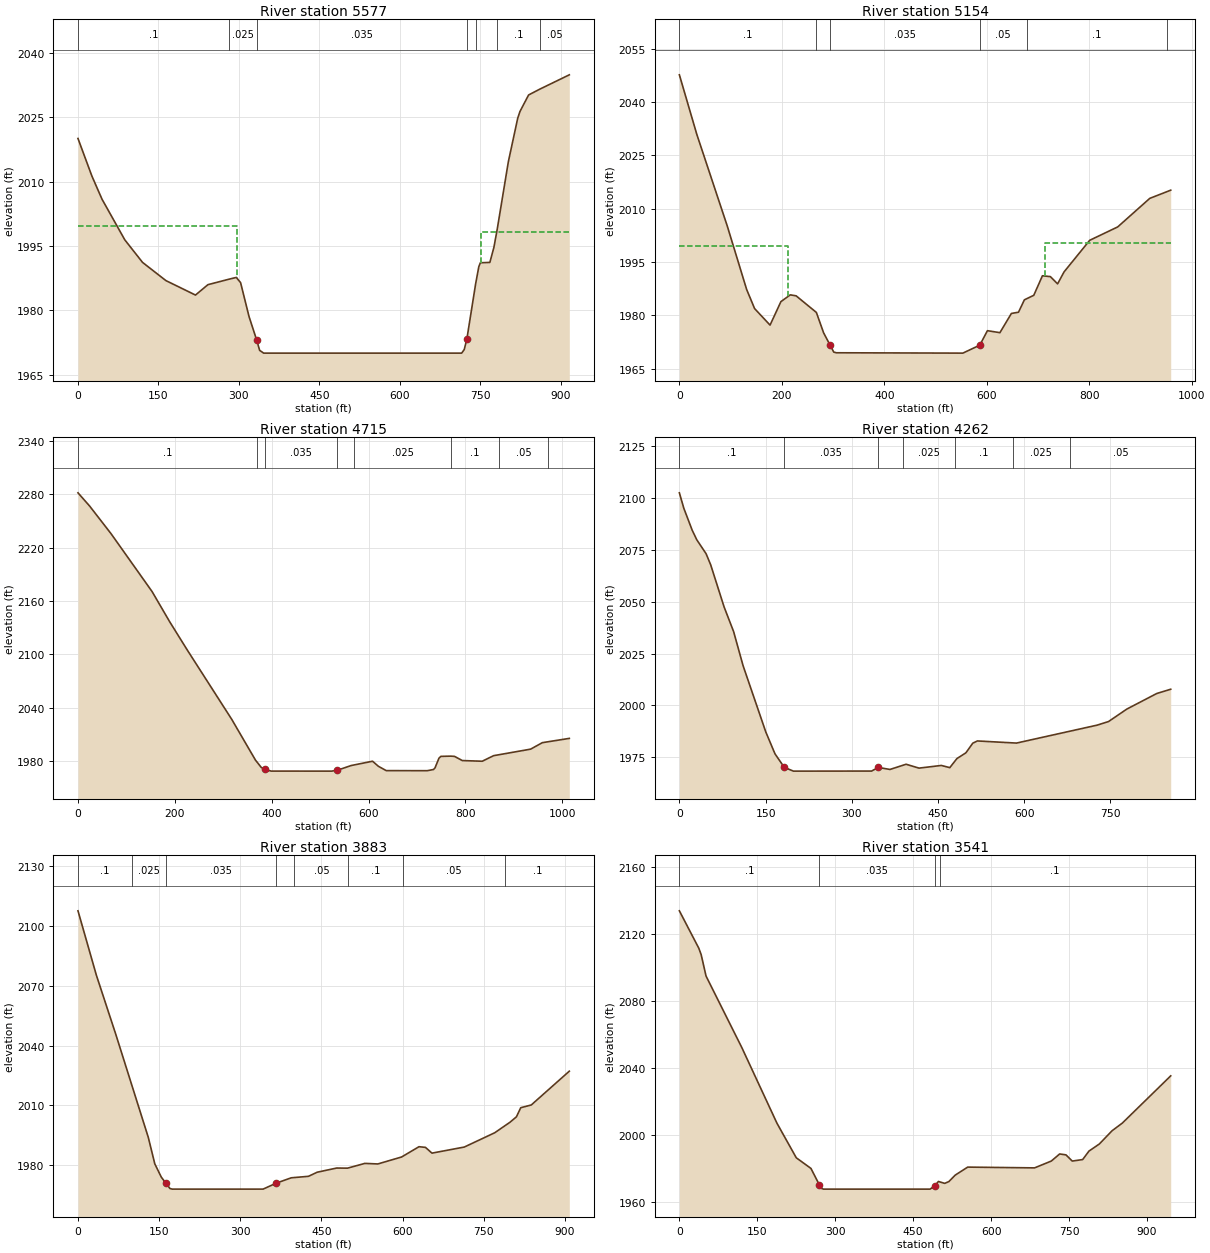
Type RM Length L Ch R = 1 ,5577    ,400.9,423.1,483
XS GIS Cut Line= 2
     2189254.123      385169.123     2188478.338       384682.45
#Sta/Elev= 30
       0 2020.05    25.9  2011.3    44.8 2005.89    87.3 1996.41   120.3 1991.16
   163.9 1986.91     219 1983.54   242.2 1985.96   280.9 1987.22   295.1 1987.65
   303.1 1986.44   318.7 1978.58   332.8 1973.15   338.6 1970.65   346.1    1970
   715.2    1970     720 1970.85   724.8 1973.25   741.2 1986.16   747.1 1990.14
     750 1991.07   767.7 1991.15   775.2 1994.63   781.4 1998.86   802.2 2014.65
   819.6 2024.75   823.9 2026.36   839.9 2030.19   860.3 2031.52   915.8 2034.89
#Mann= 7 ,-1,0
       0      .1       0   280.9    .025       0   332.8    .035       0
   724.8    .025       0   741.2     .05       0   781.4      .1       0
   860.3     .05       0
#XS Ineff= 2 , 0
          295.77 1999.64  751.55         1998.23
Permanent Ineff=
       F       F
Bank Sta=332.8,724.8
XS Rating Curve= 0 ,0
Exp/Cntr=0.3,0.1

Type RM Length L Ch R = 1 ,5154    ,505.7,438.6,366
XS GIS Cut Line= 4
2189410.80709595384775.3033766412189211.15953504384688.709253837
2188864.78304383384335.1165857222188629.05459842384262.954816719
#Sta/Elev= 30
       0  2047.7      34 2030.95    93.4 2005.17   131.3 1987.27   146.8 1981.89
     177 1977.23   198.2 1983.84   216.5 1985.75   227.9 1985.47   267.4  1980.8
   281.6 1975.04   294.2  1971.6   301.4 1969.62   306.6 1969.44   553.4 1969.34
   586.5 1971.59   601.3 1975.66   625.7  1975.1   648.1 1980.51     662 1980.86
   673.5 1984.35   691.8 1985.62   708.7 1991.12   724.2 1990.88   738.3 1988.84
   750.9 1992.21     801 2001.11   855.6 2004.87   918.2 2012.91   959.1 2015.22
#Mann= 6 ,-1,0
       0      .1       0  267.62    .025       0   294.2    .035       0
   586.5     .05       0  677.62      .1       0   952.6     .05       0
#XS Ineff= 2 , 0
          211.83 1999.45  714.37         2000.45
Permanent Ineff=
       F       F
Bank Sta=294.2,586.5
XS Rating Curve= 0 ,0
Exp/Cntr(USF)=0,0
Exp/Cntr=0.3,0.1

Type RM Length L Ch R = 1 ,4715    ,469.1,452.9,441
XS GIS Cut Line= 2
2189783.94012603384263.0252189562188776.86021646384140.151832861
#Sta/Elev= 30
       0 2281.66    23.9  2266.9    68.3  2235.7   152.9 2170.74   189.2 2136.85
   225.4 2105.18   317.5 2026.98   366.5 1981.16   378.5 1972.91   385.7 1970.88
   398.7 1968.82   523.6 1968.78   534.6  1969.6   563.9 1975.04   608.2 1979.92
   620.3 1974.21   636.5 1969.35   721.1 1969.26   734.1  1970.6   737.2 1972.42
   745.3 1983.29   749.3 1985.37     770 1985.63   777.5 1985.35   793.6 1980.66
   834.7  1979.9   858.1 1986.14   934.6 1993.49   958.8 2000.77  1014.5  2005.6
#Mann= 8 ,-1,0
       0      .1       0     370    .025       0   385.7    .035       0
   534.6      .1       0     570    .025       0     770      .1       0
     870     .05       0     970      .1       0
Bank Sta=385.7,534.6
XS Rating Curve= 0 ,0
Exp/Cntr(USF)=0,0
Exp/Cntr=0.3,0.1

Type RM Length L Ch R = 1 ,4262    ,381.9,379.4,387.8
XS GIS Cut Line= 2
2189602.54714583383746.2954551292188747.94275901383771.835356344
#Sta/Elev= 30
       0 2102.62     7.7 2095.19    22.4 2084.51    30.4  2079.9    46.4 2073.27
    54.4 2067.95    77.8 2047.55    94.4 2035.63   110.8 2019.22   150.4 1987.17
   166.4 1976.62   182.5 1970.11   198.5 1968.28   334.5 1968.31     346 1970.06
   366.5 1969.09   394.5  1971.6     417 1969.73   455.8 1971.02   470.6 1969.97
     483 1974.35   498.6 1977.12   510.6 1981.78   518.6 1982.85   586.6 1981.82
   726.7 1990.46   746.7  1992.2   778.7 1998.24   830.7 2005.75     855 2007.81
#Mann= 7 ,-1,0
       0      .1       0   182.5    .035       0     346      .1       0
     390    .025       0     480      .1       0     580    .025       0
     680     .05       0
Bank Sta=182.5,346
XS Rating Curve= 0 ,0
Exp/Cntr(USF)=0,0
Exp/Cntr=0.3,0.1

Type RM Length L Ch R = 1 ,3883    ,352,342,334.4
XS GIS Cut Line= 2
2189518.06901104383369.0907602572188610.42021401383404.453700402
#Sta/Elev= 30
       0  2107.7    33.9 2075.46    69.9 2045.69     130 1993.93     142 1980.67
     154    1974     162 1971.12     170 1968.29     174 1967.97   272.6 1967.96
   342.2 1967.97   366.2 1970.92   394.2 1973.64   426.2  1974.4   442.2 1976.45
   478.3 1978.55   498.3 1978.49   530.3 1980.88   554.3  1980.6   598.3  1984.1
   630.4 1989.26   642.4 1988.92   654.4 1986.03   714.2 1989.09   770.5 1996.28
   798.5 2001.52   810.5 2004.25   818.5 2008.83     838 2010.22   908.3 2027.18
#Mann= 8 ,-1,0
       0      .1       0     100    .025       0     162    .035       0
   366.2      .1       0     400     .05       0     500      .1       0
     600     .05       0     790      .1       0
Bank Sta=162,366.2
XS Rating Curve= 0 ,0
Exp/Cntr(USF)=0,0
Exp/Cntr=0.3,0.1

Type RM Length L Ch R = 1 ,3541    ,307.2,304.7,300.3
XS GIS Cut Line= 3
2189588.78827752383128.253359133 2189396.0457111 383019.83566552
2188675.67036909383096.932692089
#Sta/Elev= 30
       0 2133.76    37.4 2111.43      42 2107.55    51.2 2094.99    52.6 2094.02
     120 2052.26   187.8    2007     225 1986.36   253.2 1980.03   269.5 1970.16
   273.3 1968.15   277.3 1967.66   482.5 1967.66   491.2 1969.61   498.6 1972.23
   510.7 1971.09   518.7 1972.18   530.8 1976.01   554.9  1980.8   683.6 1980.34
   715.8 1984.42   731.9 1988.65     744 1988.11   756.1  1984.4   776.2 1985.31
   788.2 1990.34   808.3 1994.61   832.7 2002.49   852.6 2007.11   945.6 2035.26
#Mann= 4 ,-1,0
       0      .1       0   269.5    .035       0   491.2    .025       0
  501.14      .1       0
Bank Sta=269.5,491.2
XS Rating Curve= 0 ,0
Exp/Cntr(USF)=0,0
Exp/Cntr=0.3,0.1

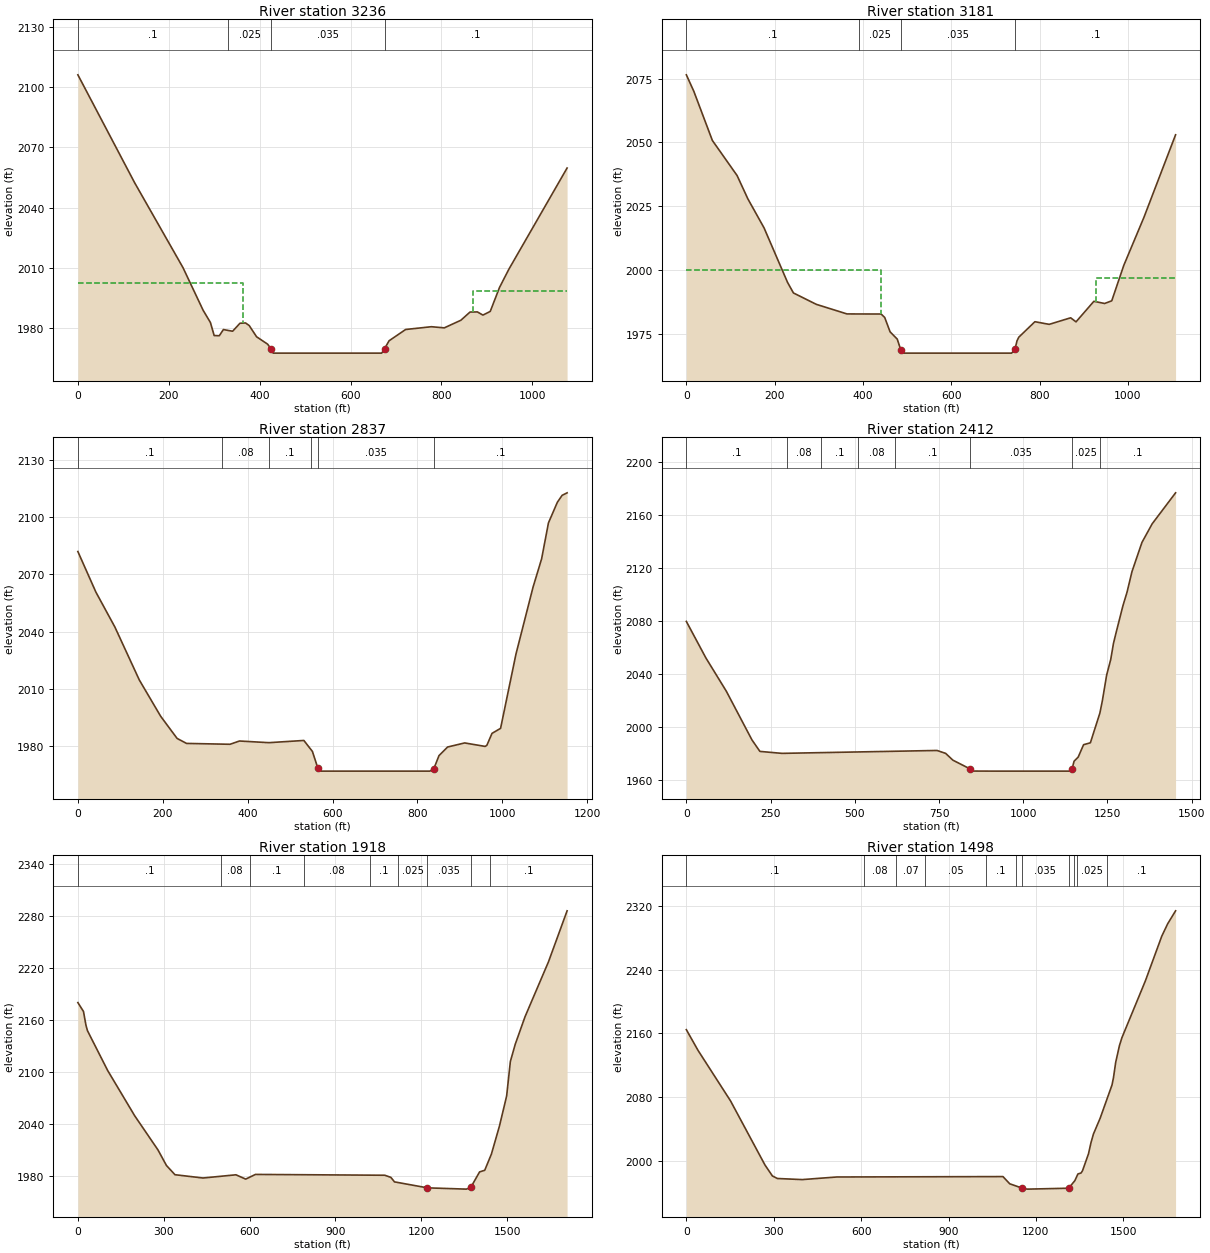
Type RM Length L Ch R = 1 ,3236    ,62.8,55.6,55.6
XS GIS Cut Line= 4
2189653.62694826382934.9124395982189506.28136433382744.345484377
2189325.53744803382712.9117598042188681.14609429382813.106756879
#Sta/Elev= 30
       0 2106.26   124.9 2052.41   231.3 2010.04   275.5 1988.82   291.7 1982.64
   299.9 1976.16   311.2 1976.06   320.2 1979.14   340.5 1978.31   356.7 1982.29
   368.9 1982.43     377 1981.15   393.2 1975.55   417.6 1971.84   424.3 1969.68
   429.8 1967.38   668.6 1967.38   674.9 1969.61   684.8 1973.55   721.2 1979.17
   777.9 1980.56   806.2 1979.99   842.7 1983.78   862.9 1987.88   879.1 1987.94
   891.3 1986.36   907.4  1988.2   927.7  2000.1   948.1 2009.14  1076.5 2059.76
#Mann= 4 ,-1,0
       0      .1       0  330.89    .025       0   424.3    .035       0
   674.9      .1       0
#XS Ineff= 2 , 0
          363.04 2002.21  869.41         1998.59
Permanent Ineff=
       F       F
Bank Sta=424.3,674.9
XS Rating Curve= 0 ,0
Exp/Cntr(USF)=0,0
Exp/Cntr=0.3,0.1

Type RM Length L Ch R = 1 ,3181    ,336.9,343.2,346.5
XS GIS Cut Line= 3
2189800.80510059382564.4813523422189391.22714694382646.396943073
2188709.40031821382752.405354606
#Sta/Elev= 30
       0 2076.54      17 2070.04    58.9 2050.79   114.9 2037.02   139.3 2027.87
     176 2016.46   229.1  1995.1   242.5 1990.95   294.3 1986.48   363.7 1982.72
     441 1982.68   449.1 1981.34   461.3  1975.7   477.5 1972.84   485.5 1968.64
   489.6 1967.34   736.5 1967.34     744 1968.79   748.6 1972.13   752.7 1973.59
   789.2 1979.67   821.5 1978.63   870.1  1981.2   882.3 1979.61   922.7 1987.67
     947 1986.82   963.2 1987.87   990.3 2001.71  1036.1 2020.64  1107.7 2053.01
#Mann= 4 ,-1,0
       0      .1       0     390    .025       0   485.5    .035       0
     744      .1       0
#XS Ineff= 2 , 0
          440.11  1999.8  928.23         1996.93
Permanent Ineff=
       F       F
Bank Sta=485.5,744
XS Rating Curve= 0 ,0
Exp/Cntr(USF)=0,0
Exp/Cntr=0.3,0.1

Type RM Length L Ch R = 1 ,2837    ,435.9,425.3,426.3
XS GIS Cut Line= 3
2189818.14739807382504.0709455472189413.94479839382306.237948146
2188716.62816445 382391.01304256
#Sta/Elev= 30
       0    2082    42.3 2060.83    87.4 2042.39   144.7 2014.77     195 1995.77
   233.8 1984.14     256 1981.54   358.5 1981.09   380.7  1982.8     450 1981.93
   532.4 1983.09   552.5 1977.35565.39061968.556   572.5 1967.03   829.4 1967.03
838.79051968.403   850.7 1975.15   870.9 1979.65   911.2 1981.79   959.5 1979.97
   963.5 1980.57   975.6  1986.8   995.8 1989.43    1032 2028.27  1072.3 2063.37
  1092.5 2078.22  1108.6 2097.02  1129.7 2107.87  1140.8 2111.44  1152.5 2112.75
#Mann= 6 ,-1,0
       0      .1       0     340     .08       0     450      .1       0
  550.02    .025       0565.3906    .035       0838.7905      .1       0
Bank Sta=565.3906,838.7905
XS Rating Curve= 0 ,0
Exp/Cntr(USF)=0,0
Exp/Cntr=0.3,0.1

Type RM Length L Ch R = 1 ,2412    ,440.9,494.3,565.2
XS GIS Cut Line= 4
2189981.34799463 382183.370109362189274.34553009381884.287514636
2188899.21755852381946.7147233462188597.12626211381983.399696695
#Sta/Elev= 30
       0 2079.38    57.7 2051.96   118.5 2026.79   194.8 1989.95   218.4  1981.3
   283.6 1979.81     744    1982   769.9 1979.79   791.2 1974.68   842.2 1968.09
   850.3 1966.46   919.3 1966.41  1138.9 1966.41 1144.95 1968.06    1151 1973.89
  1163.1 1976.96  1179.2 1986.35  1199.4 1987.79  1227.6 2010.23  1234.8 2019.28
  1247.7 2038.92  1259.8 2050.64  1267.9 2062.76  1275.9 2071.09  1296.1 2091.29
  1308.2 2101.44  1322.9 2116.98  1352.5    2139  1382.8 2153.03  1452.3 2176.42
#Mann= 8 ,-1,0
       0      .1       0     300     .08       0     400      .1       0
     510     .08       0     620      .1       0   842.2    .035       0
 1144.95    .025       0 1227.95      .1       0
Bank Sta=842.2,1144.95
XS Rating Curve= 0 ,0
Exp/Cntr(USF)=0,0
Exp/Cntr=0.3,0.1

Type RM Length L Ch R = 1 ,1918    ,421.9,420.2,419.1
XS GIS Cut Line= 2
2190270.61510625381877.8359594562188666.03324077381287.561849782
#Sta/Elev= 30
       0 2180.12    19.6 2169.92    28.2 2154.13    33.6 2147.71   104.1 2101.93
   198.5  2049.8     280 2010.41   309.5 1992.52   339.3 1981.89   437.3 1978.09
   552.4 1981.78   586.5 1976.81   620.6 1982.22  1072.4 1981.27  1093.7 1978.85
  1106.5 1973.63  1221.6 1966.75  1357.9 1965.28  1373.4 1967.42  1403.8 1985.08
  1421.9 1987.02  1445.1 2005.58  1473.1 2037.69  1496.5 2069.85  1498.6  2073.1
  1511.4 2112.25  1528.4 2132.06  1562.5  2163.7  1644.5 2226.99  1709.7 2285.83
#Mann= 9 ,-1,0
       0      .1       0     500     .08       0     600      .1       0
     790     .08       0    1020      .1       0    1120    .025       0
  1221.6    .035       0  1373.4    .025       0    1440      .1       0
Bank Sta=1221.6,1373.4
XS Rating Curve= 0 ,0
Exp/Cntr(USF)=0,0
Exp/Cntr=0.3,0.1

Type RM Length L Ch R = 1 ,1498    ,273.2,253.2,230.2
XS GIS Cut Line= 3
2190381.98765564381469.5179123462189070.26741192380993.610340928
  2188802.569403380898.428826644
#Sta/Elev= 30
       0 2164.63    40.2 2138.64   151.6 2075.47     270 1995.05   295.5 1981.37
   312.6 1978.19   397.7 1976.83   516.7 1980.09    1087 1980.59  1110.1 1971.58
  1150.8 1966.38  1171.1 1964.88  1312.5 1966.02  1333.8 1975.56  1344.3  1983.9
  1355.1 1985.11  1359.9 1987.83  1380.6 2009.18  1389.1 2023.13  1397.6 2033.97
  1420.6 2053.73  1461.3  2095.4  1466.3 2104.46    1474 2123.87  1486.8 2144.71
  1495.2 2154.51  1575.8 2225.76  1632.2 2281.87  1652.3 2297.24  1679.5 2313.54
#Mann= 11 ,-1,0
       0      .1       0     610     .08       0     720     .07       0
     820     .05       0    1030      .1       0    1130    .025       0
  1150.8    .035       0  1312.5    .025       0    1330      .1       0
    1340    .025       0 1445.38      .1       0
Bank Sta=1150.8,1312.5
XS Rating Curve= 0 ,0
Exp/Cntr(USF)=0,0
Exp/Cntr=0.3,0.1

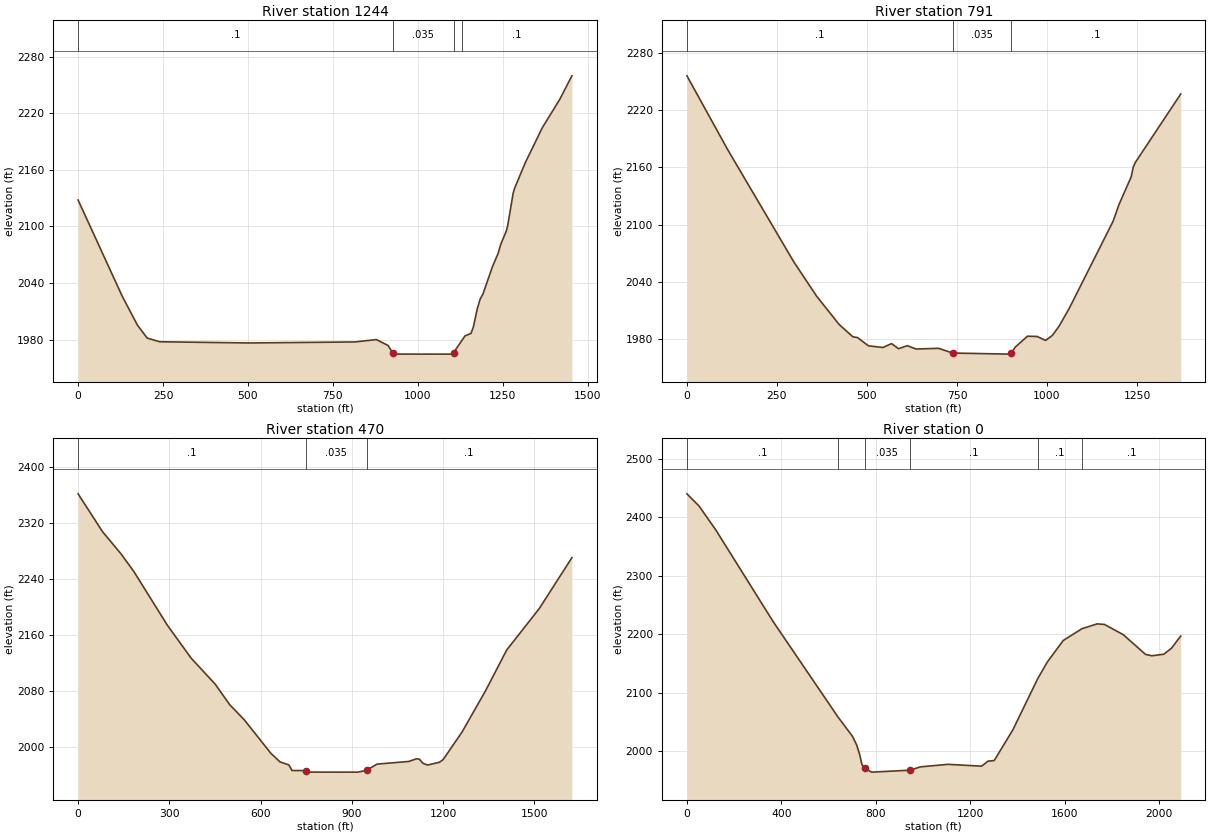
Type RM Length L Ch R = 1 ,1244    ,503.3,453.4,403.2
XS GIS Cut Line= 4
2190326.24016977381041.7591325452190059.92678717380979.141669952
2189447.58120943380842.7331221572188901.45427945380756.190125846
#Sta/Elev= 30
       0 2128.03   129.5 2026.37   174.7 1995.39   203.5 1981.69   240.4 1977.76
   502.9  1976.5   814.6 1977.57   878.3 1980.09   912.5 1973.85   926.2 1966.26
   932.7 1964.69  1098.8 1964.661105.4061966.239  1139.3 1983.99    1157 1986.71
    1164 1993.72  1175.7 2013.31  1183.8 2023.02    1192 2028.31  1219.9  2057.3
  1236.5 2071.31  1244.8 2081.42  1260.8 2095.07  1264.8 2100.68    1281 2135.33
  1285.1 2140.35    1317 2167.88  1366.7 2204.64  1418.1 2234.71  1453.9 2259.71
#Mann= 4 ,-1,0
       0      .1       0   926.2    .035       01105.406    .025       0
 1130.93      .1       0
Bank Sta=926.2,1105.406
XS Rating Curve= 0 ,0
Exp/Cntr(USF)=0,0
Exp/Cntr=0.3,0.1

Type RM Length L Ch R = 1 ,791     ,322.7,321.5,315.5
XS GIS Cut Line= 4
2190017.29895993379937.7621972422189403.66220708380357.363613219
2189238.73217074380398.5961223042188920.99930662 380728.45619498
#Sta/Elev= 30
       0 2255.69   112.8 2178.64   296.8  2060.9   359.9  2025.1   422.9 1995.27
   460.8 1982.45   473.8  1981.6     504 1972.99   544.1 1971.23   568.3  1975.3
   587.7 1969.94   611.9 1973.14   636.2 1969.63   699.1 1970.36   737.9 1965.41
   895.4 1964.28   901.1 1965.26   911.9 1971.68   945.9 1983.06   972.5 1982.76
   996.2 1978.65  1015.1 1983.94  1033.6 1993.55  1061.4 2011.92  1183.6  2103.4
  1199.9 2120.83  1233.9    2150  1239.5 2159.96  1244.6 2164.55  1371.4 2236.67
#Mann= 3 ,-1,0
       0      .1       0   737.9    .035       0   901.1      .1       0
Bank Sta=737.9,901.1
XS Rating Curve= 0 ,0
Exp/Cntr(USF)=0,0
Exp/Cntr=0.3,0.1

Type RM Length L Ch R = 1 ,470     ,469.5,469.5,469.5
XS GIS Cut Line= 4
 2190069.6733119379729.4808543492189397.45386727380020.974241842
 2189025.6510771380145.8999793392188725.23442265380544.472570402
#Sta/Elev= 30
       0 2361.02    80.1 2307.19   140.8 2275.55   183.4 2250.17   293.7  2173.5
   371.9 2126.57   450.7 2089.59   498.7 2060.19   546.6 2038.63   633.8 1990.96
   664.3 1978.52     693 1974.38   703.6 1966.35   749.7  1966.2   759.4 1964.03
   920.2 1964.01   948.6  1966.6     983 1975.42  1087.6 1979.23  1112.9 1983.05
  1122.4 1982.53    1134 1976.72  1149.1  1974.1  1188.3 1978.06  1200.5 1981.88
  1262.6 2021.13  1339.7 2079.78  1409.5 2138.16  1516.8 2197.41    1624  2269.9
#Mann= 3 ,-1,0
       0      .1       0   749.7    .035       0   948.6      .1       0
Bank Sta=749.7,948.6
XS Rating Curve= 0 ,0
Exp/Cntr(USF)=0,0
Exp/Cntr=0.3,0.1

Type RM Length L Ch R = 1 ,0       ,,,
XS GIS Cut Line= 3
     2189607.863      379011.495     2189061.209      379664.832
      2188233.66      380587.405
#Sta/Elev= 30
       0 2440.45    51.3 2419.55   122.4 2378.49     364  2222.2  639.782058.025
   701.1 2024.95     719  2009.9   731.4 1994.09     741 1976.47   752.3 1970.24
   781.9 1963.59   944.2 1966.86   988.2 1972.58  1105.7 1976.93  1248.3 1973.82
  1274.7 1982.37  1301.2 1983.43  1379.9 2035.72 1485.722123.865  1525.9 2152.05
  1593.6 2189.13 1673.022209.377  1737.6 2217.65  1768.3 2216.63  1847.7 2199.15
  1942.1 2165.35  1968.8 2162.97  2019.6  2165.6  2052.3 2176.03  2091.2 2196.73
#Mann= 6 ,-1,0
       0      .1       0  639.78      .1       0   752.3    .035       0
   944.2      .1       0 1485.72      .1       0 1673.02      .1       0
Bank Sta=752.3,944.2
XS Rating Curve= 0 ,0
Exp/Cntr=0.3,0.1
LCMann Table=0

Chan Stop Cuts=-1
Use User Specified Reach Order=0
Composite Channel Slope=5